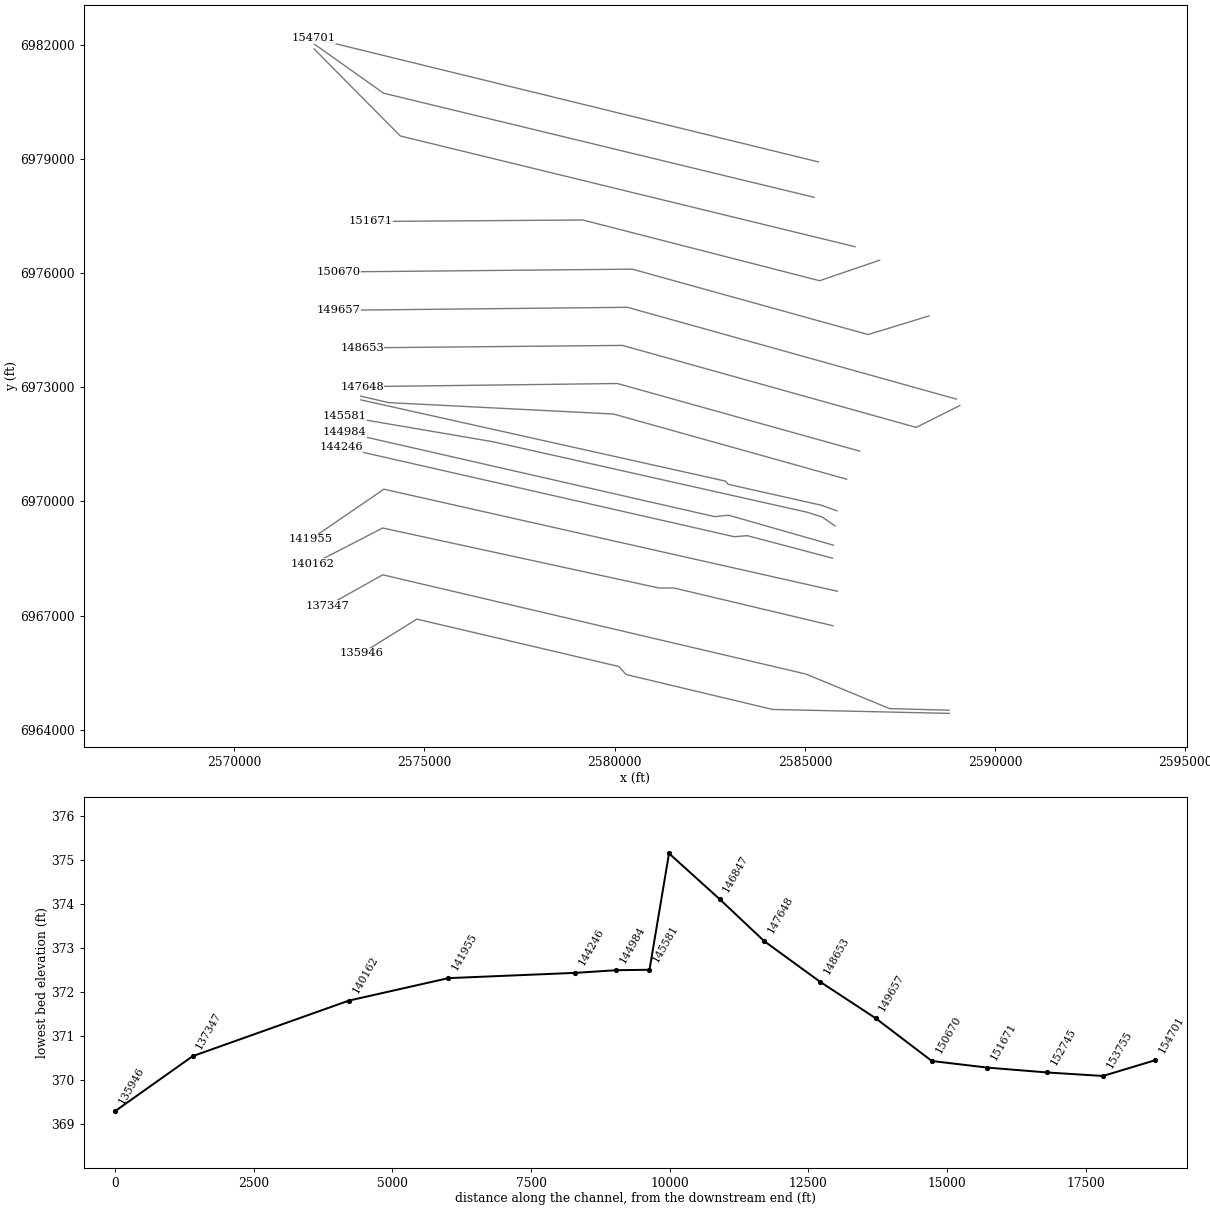
HEC-RAS study EF_FEMA.prj: East_Fork_FEMA

--- EF_FEMA.g06 (geometry) --- (continued)

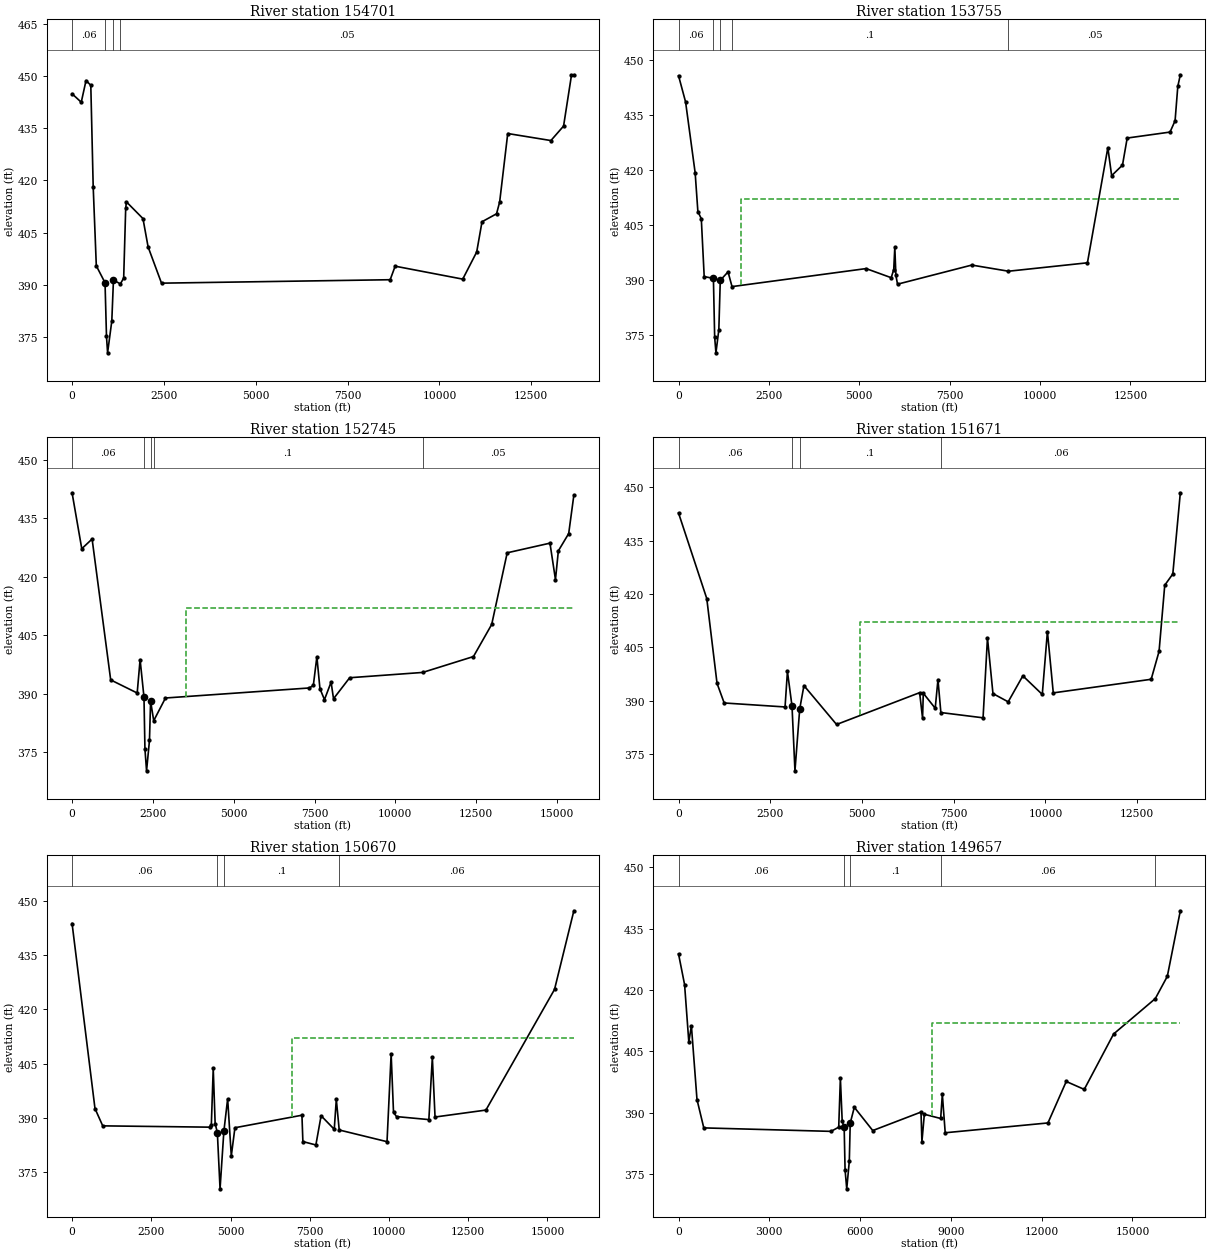
Type RM Length L Ch R = 1 ,154701  ,937.26,946.43,948.61
XS GIS Cut Line= 2
2585354.29849239 6978923.58382242572086.937231886982170.80633056
#Sta/Elev= 30
       0  444.89  249.98  442.46  379.97   448.7  509.96  447.32  574.96  418.21
  659.95  395.45 897.217390.5938937.0933375.1683967.0006370.44921081.645379.5984
1126.506391.3665  1314.9  390.26 1404.89  391.93 1459.89  412.01 1479.89  413.83
 1929.85  409.03 2069.84  400.88 2434.82  390.47 8659.31  391.46 8794.31  395.35
10634.31  391.63 11014.3  399.42 11159.3  408.12 11554.3   410.4 11639.3  413.79
 11859.3  433.4713034.29  431.4513379.29  435.6113594.29  450.2313659.29  450.35
#Mann= 4 ,-1 , 0
       0     .06       0 897.217    .045       01126.506     .06       0
  1314.9     .05       0
#XS Ineff= 2 , 0
       0                 1479.89       0  413.83
Permanent Ineff=
       F       F
Bank Sta=897.217,1126.506
XS Rating Curve= 0 ,0
Exp/Cntr=0.3,0.1

Type RM Length L Ch R = 1 ,153755  ,1052.34,1009.42,1006.82
XS GIS Cut Line= 3
2585243.187166056977993.028268812573927.973576056980729.49556489
2572100.826311726982024.97296081
#Sta/Elev= 30
       0  445.78  194.94  438.61  459.86  419.25  534.83  408.69  629.81  406.71
  709.78  390.91   964.7  390.43  999.69  374.35 1034.68  370.09 1114.66   376.4
 1154.64  389.89 1369.58   392.2 1479.51  388.18  5188.4   393.1  5883.2  390.61
 5953.18  392.83 5983.17  398.95 6013.16  391.22 6058.15  388.84 8112.55  394.06
 9127.44  392.3811311.57  394.6811876.46  426.1311981.46  418.4812281.45  421.36
12411.45  428.7513596.43  430.3813736.43  433.4813811.43  442.8513881.43  446.03
#Mann= 5 ,-1 , 0
       0     .06       0   964.7    .045       0 1154.64     .05       0
 1479.51      .1       0 9127.44     .05       0
#XS Ineff= 2 , 0
       0                  1734.4       0     412
Permanent Ineff=
       F       F
Bank Sta=964.7,1154.64
XS Rating Curve= 0 ,0
Exp/Cntr=0.3,0.1

Type RM Length L Ch R = 1 ,152745  ,1165.53,1074.7,1037.42
XS GIS Cut Line= 3
2586319.576089386976694.417348982574367.48253955 6979605.0115934
2572100.826311726981893.02834281
#Sta/Elev= 30
       0  441.55  299.91  427.19  619.82  429.68 1194.65  393.51  2014.4  390.15
 2104.38  398.72 2224.47  389.09 2254.33  375.77 2304.32  370.17 2394.29  377.98
 2429.28  388.05  2525.7  383.04 2889.15  388.87 7332.82  391.44 7462.78  392.08
 7572.75  399.47 7667.72  391.26 7807.68  388.45 8012.62  392.94  8087.6  388.68
 8587.47  394.0710845.06  395.4312416.44  399.5112980.67  407.7513460.01  426.14
 14783.2  428.6214952.97  419.2615042.85  426.6515362.41  431.0815522.19  440.94
#Mann= 5 ,-1 , 0
       0     .06       0 2224.47    .045       0 2429.28     .06       0
  2525.7      .1       010845.06     .05       0
#XS Ineff= 2 , 0
       0                  3523.6       0     412
Permanent Ineff=
       F       F
Bank Sta=2224.47,2429.28
XS Rating Curve= 0 ,0
Exp/Cntr=0.3,0.1

Type RM Length L Ch R = 1 ,151671  ,1085.86,1001.11,949.34
XS GIS Cut Line= 4
2586965.409443396976340.250734482585385.772838896975801.26296732
2579165.243285226977396.906101482573578.862725726977357.53216448
#Sta/Elev= 30
       0  442.77  769.57  418.72 1049.41  394.88  1244.3  389.36 2903.46  388.24
 2968.43  398.23 3093.37  388.47 3173.33  370.28 3303.26   387.7 3418.21  394.25
 4307.77  383.31 6571.67  392.26 6651.64  385.07 6671.63   392.1 6996.47  387.88
 7071.43  395.93  7150.7  386.67 8300.81  385.19 8420.74  407.65 8570.66     392
 8985.41  389.68 9385.18  396.99 9914.87  391.7610054.79  409.4510214.69   392.2
12883.13  396.02   13098  403.8713252.91  422.4713472.78  425.6413677.66  448.46
#Mann= 4 ,-1 , 0
       0     .06       0 3093.37    .045       0 3303.26      .1       0
  7150.7     .06       0
#XS Ineff= 2 , 0
       0                  4952.2       0     412
Permanent Ineff=
       F       F
Bank Sta=3093.37,3303.26
XS Rating Curve= 0 ,0
Exp/Cntr=0.3,0.1

Type RM Length L Ch R = 1 ,150670  ,1057.76,1012.4,1039.62
XS GIS Cut Line= 4
2588263.847135226974877.056154312586661.814578136974386.35306747
2580463.907026476976105.09700531 2572739.71512586976031.91736165
#Sta/Elev= 30
       0  443.73  723.06  392.61   967.4  387.83 4344.17  387.47 4394.14  388.12
 4454.11  403.69 4514.08  388.48 4584.04  385.96    4669  370.43 4788.94  386.28
 4908.88  395.31 5023.82  379.53 5138.76  387.31 7252.68  390.77 7282.66  383.49
 7692.46  382.55 7857.37  390.62 8272.24  386.88 8337.24  395.17 8428.73  386.69
 9937.24  383.4610067.24  407.6910142.24  391.5310237.24  390.3911257.24  389.56
11367.24  406.7511452.24  390.2713057.24  392.1915222.24  425.5215832.24  447.25
#Mann= 4 ,-1 , 0
       0     .06       0 4584.04    .045       0 4788.94      .1       0
 8428.73     .06       0
#XS Ineff= 2 , 0
       0                  6946.5       0     412
Permanent Ineff=
       F       F
Bank Sta=4584.04,4788.94
XS Rating Curve= 0 ,0
Exp/Cntr=0.3,0.1

Type RM Length L Ch R = 1 ,149657  ,1009.92,1004,1081.52
XS GIS Cut Line= 3
2588984.099959816972689.38139582 2580336.69993186975102.62689739
 2572732.50844736975024.63295889
#Sta/Elev= 30
       0  428.83  199.95  421.33  339.92   407.3   424.9  411.28  609.85  393.23
   834.8   386.3 5038.77  385.45 5293.71  386.48  5348.7  398.47 5408.69  387.94
 5473.67  386.44 5503.66  376.04 5558.65   371.4 5643.63  378.16 5673.62  387.45
 5808.59  391.34 6418.45  385.65 8013.07  390.17 8043.06   382.9 8123.04  389.63
 8662.84   388.6 8717.92   394.5  8812.9  385.1112207.87  387.5112812.87  397.65
13407.87  395.7114377.87  409.2615756.35  417.9116152.87  423.3516582.87  439.38
#Mann= 5 ,-1 , 0
       0     .06       0 5473.67    .045       0 5673.62      .1       0
 8662.84     .06       015756.35      .1       0
#XS Ineff= 2 , 0
       0                  8359.9       0     412
Permanent Ineff=
       F       F
Bank Sta=5473.67,5673.62
XS Rating Curve= 0 ,0
Exp/Cntr=0.3,0.1

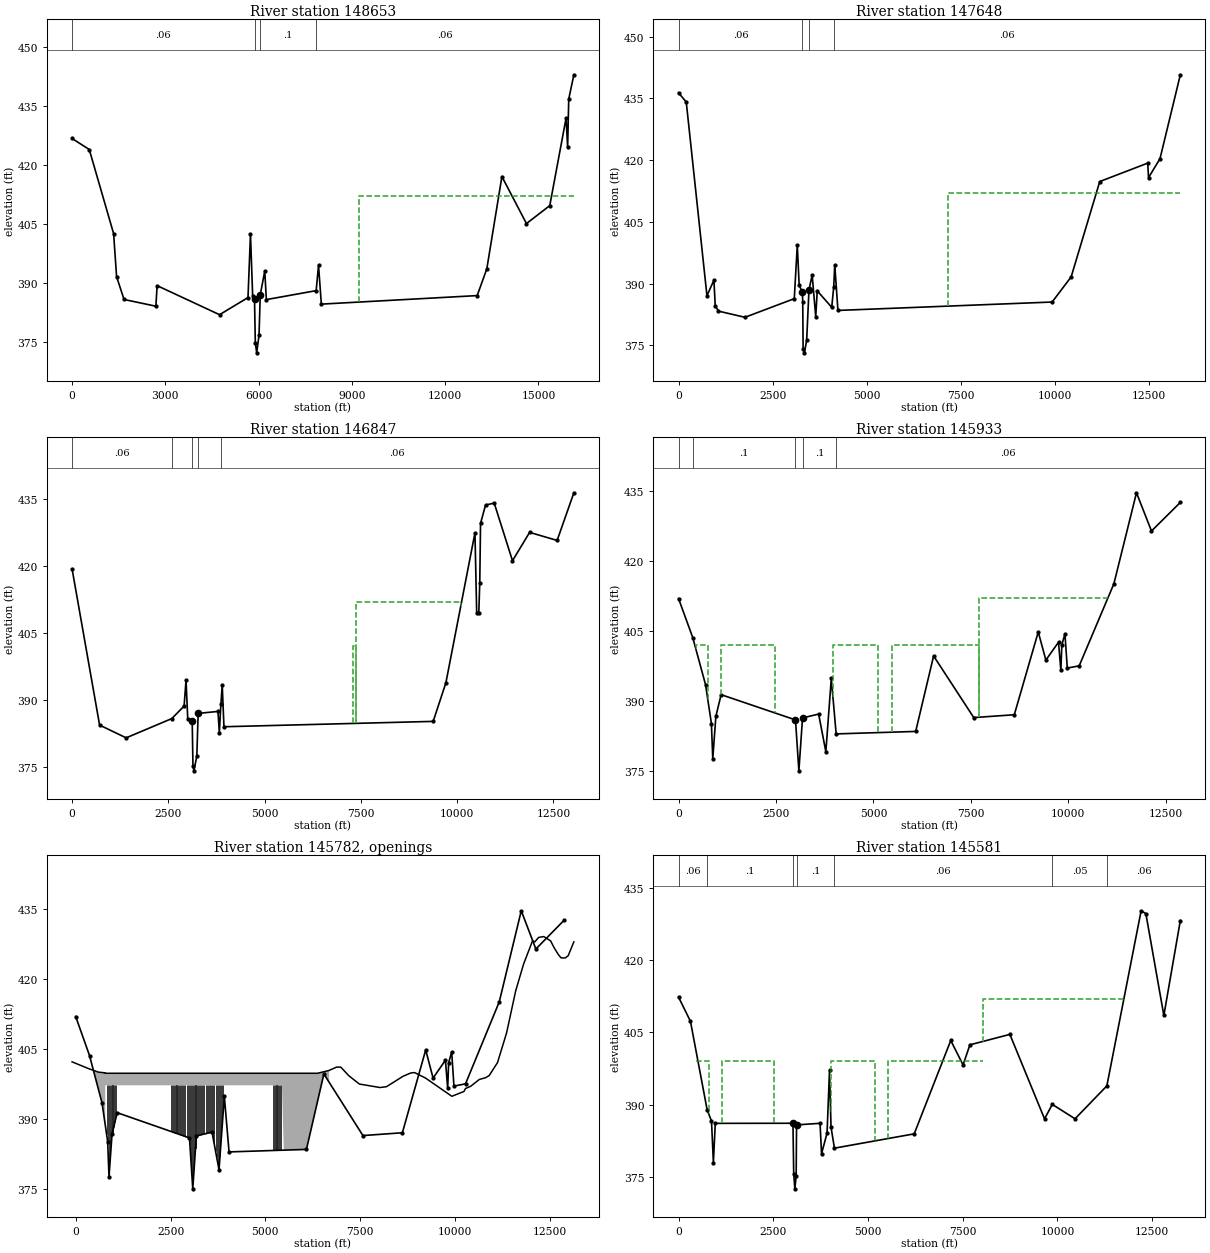
Type RM Length L Ch R = 1 ,148653  ,1000.74,1004.94,1084.16
XS GIS Cut Line= 4
2589071.138827736972520.285277312587925.119466226971946.70243497
2580205.059118976974101.153506652573361.84872405 6974037.2195794
#Sta/Elev= 30
       0  426.75  553.51  423.94 1336.51  402.54 1431.45  391.62 1671.31   385.8
 2695.67  384.09 2735.65  389.32 4744.41  381.93 5658.88  386.29 5738.83  402.48
 5808.79   386.7 5868.75  385.85 5893.74  374.79 5938.71  372.23 6013.67  376.74
 6053.65  387.01 6198.56  393.04 6248.53  385.77 7851.74  388.05 7927.55   394.5
 8017.49  384.6213031.01  386.7913340.95  393.6113825.86  417.0614615.71  405.11
15365.56  409.6715890.46  431.9515940.45  424.5115975.44  436.7616140.41  442.95
#Mann= 4 ,-1 , 0
       0     .06       0 5868.75    .045       0 6053.65      .1       0
 7851.74     .06       0
#XS Ineff= 2 , 0
       0                  9216.3       0     412
Permanent Ineff=
       F       F
Bank Sta=5868.75,6053.65
XS Rating Curve= 0 ,0
Exp/Cntr=0.3,0.1

Type RM Length L Ch R = 1 ,147648  ,805.98,801.2,859.08
XS GIS Cut Line= 3
2586440.930505476971322.368709892580073.418306146973099.68011589
2573361.848724056973017.25442773
#Sta/Elev= 30
       0  436.36  204.87  434.13  754.53  387.03  939.42  390.81  974.39  384.63
 1059.34  383.29 1763.91  381.79  3073.1  386.32 3153.05  399.31 3203.02  389.57
 3287.97   387.9 3297.96  385.48 3307.96  374.09 3342.93  373.15  3402.9  376.31
 3462.86  388.41 3547.81  392.06 3642.75  381.94 3682.73  388.22 4067.49  384.22
 4120.89  389.24 4147.44  394.56 4232.39  383.46 9919.55   385.510424.35  391.61
11184.06  414.7912458.56  419.2712478.55  415.7412783.43  420.3413323.22  440.74
#Mann= 4 ,-1 , 0
       0     .06       0 3287.97    .045       0 3462.86      .1       0
 4120.89     .06       0
#XS Ineff= 2 , 0
       0                  7149.6       0     412
Permanent Ineff=
       F       F
Bank Sta=3287.97,3462.86
XS Rating Curve= 0 ,0
Exp/Cntr=0.3,0.1

Type RM Length L Ch R = 1 ,146847  ,934.05,914.27,1027.43
XS GIS Cut Line= 4
2586097.721218146970585.740918062579968.105852726972298.50160015
2574066.767917896972597.507563812573327.126352556972767.68832581
#Sta/Elev= 30
       0  419.35  714.93  384.35 1404.87  381.49 2589.77  385.81 2909.74  388.61
 2959.74  394.41 3004.73  385.65 3119.73  385.27 3139.72  375.23 3164.72   374.1
 3239.72  377.39 3274.71  386.97 3789.67  387.41 3824.67  382.64 3864.67  388.97
 3899.66  393.32 3944.66  383.98 9378.84  385.18 9708.77  393.8310463.63  427.41
10508.62  409.4910563.61  409.54 10588.6  416.25 10608.6  429.5410738.57  433.65
10963.53  434.0911438.44  421.1711883.35  427.5312597.83  425.7213032.23   436.4
#Mann= 5 ,-1 , 0
       0     .06       0 2589.77      .1       0 3119.73    .045       0
 3274.71      .1       0 3864.67     .06       0
#XS Ineff= 2 ,-1
  7284.1    7363     402    7363   10096     412
Permanent Ineff=
       F       F
Bank Sta=3119.73,3274.71
XS Rating Curve= 0 ,0
Exp/Cntr=0.5,0.3

Type RM Length L Ch R = 1 ,145933  ,262.87,352.09,328.09
BEGIN DESCRIPTION:
US Bridge
END DESCRIPTION:
XS GIS Cut Line= 5
2585841.90053555 6969754.94861642585428.098541636969901.74228606
2582984.088337816970451.351751152582912.465449566970534.64817248
 2573329.29662386972670.03202505
#Sta/Elev= 30
       0  411.95  364.23  403.62  693.56  393.52  843.27  385.25   878.2  377.75
  958.04  386.81 1092.77  391.41    3000  386.02    3087  375.14  3180.6  386.45
 3593.87  387.26 3778.84  379.23 3918.81  394.89  4043.4  383.03 6083.39  383.56
  6543.3  399.68  7573.1  386.52  8612.9  387.12 9227.78  404.81 9422.74   398.8
 9747.68  402.62 9807.67  396.58 9832.66  402.06 9912.65   404.4 9972.63  397.09
10277.57  397.57 11167.4  415.0911747.29  434.5412132.21  426.3712872.07  432.48
#Mann= 5 ,-1 , 0
       0     .06       0  364.23      .1       0    3000    .045       0
  3180.6      .1       0  4043.4     .06       0
#XS Ineff= 5 ,-1
     441     759     402    1094    2465     402  3960.1    5115     402
    5488  7714.1     402  7714.1   11024     412
Permanent Ineff=
       F       F       F       F       F
Bank Sta=3000,3180.6
XS Rating Curve= 0 ,0
Exp/Cntr=0.5,0.3

Type RM Length L Ch R = 4 ,145782  ,,,
BEGIN DESCRIPTION:
HWY 80 - bridge deck outside surveyed area is cut from LiDAR of road; verified hills that road cuts through
END DESCRIPTION:
Node Name=HWY 80
Bridge Culvert--1,0,-1,-1, 0
Deck Dist Width WeirC Skew NumUp NumDn MinLoCord MaxHiCord MaxSubmerge Is_Ogee
129,125,2.6,0, 65, 65, , , 0.98, 0, 0,0,,
  -95.49  332.46  601.71  776.48  779.34  779.34 1074.51 1074.51 1081.06 1305.75
 1480.52 1670.26 1894.95 2495.53 2495.53    3919    3919  4102.7 4322.48 4692.11
 4911.89 5011.79 5016.78 5081.72 5165.44 5165.44 5438.44 5438.44 5486.31 5985.81
 6170.62 6375.42 6680.11 6879.91  6989.8 7199.59  7479.3 8023.76 8193.58 8633.14
 8837.93 8932.84 9222.57 9917.1210236.9210276.89 10416.810641.6610806.5510901.49
11121.3511361.1911601.0411810.9112045.7312100.6412205.4812340.27   1252012619.84
12734.6712799.57 12909.412984.2813134.05
  402.27  400.84  400.07  399.92  399.83  399.83  399.83  399.83  399.83  399.83
  399.83  399.83  399.83  399.83  399.83  399.83  399.83  399.83  399.83  399.83
  399.83  399.83  399.83  399.83  399.83  399.83  399.83  399.83  399.83  399.83
  399.83  399.83  400.43  401.15  401.14  399.31  397.53  396.78  396.96   399.2
   399.9  399.98  398.81  394.91  395.94  396.57  397.07  398.51  398.88  399.34
  402.11  408.48  417.46  423.21  428.15  427.87  428.85  429.03  428.12  426.56
  425.08  424.47  424.47  424.94   427.9
                                          397.26  397.26
                                  397.26  397.26
                                          397.26  397.26
 -690.28  -33.49  394.46  663.71  688.48  831.34  831.34 1126.51 1126.51 1143.06
 1367.75 1542.52 1732.26 1956.95 2556.38 2556.38 3983.94 3983.94  4164.7 4384.48
 4754.11 4973.89 5078.78 5143.72 5227.44 5227.44 5500.44 5500.44 5548.31 6047.81
 6232.62 6437.42 6742.11 6941.91  7051.8 7261.59  7541.3 8085.76 8255.58 8695.14
 8899.93 8994.84 9284.57 9979.1210298.9210338.89 10478.810703.6610868.5510963.49
11183.3511423.1911663.0411872.9112107.7312162.6412267.4812402.27   1258212681.84
12796.6712861.57 12971.413046.2813196.05
  404.49  402.27  400.84  400.07  399.92  399.83  399.83  399.83  399.83  399.83
  399.83  399.83  399.83  399.83  399.83  399.83  399.83  399.83  399.83  399.83
  399.83  399.83  399.83  399.83  399.83  399.83  399.83  399.83  399.83  399.83
  399.83  399.83  400.43  401.15  401.14  399.31  397.53  396.78  396.96   399.2
   399.9  399.98  398.81  394.91  395.94  396.57  397.07  398.51  398.88  399.34
  402.11  408.48  417.46  423.21  428.15  427.87  428.85  429.03  428.12  426.56
  425.08  424.47  424.47  424.94   427.9
                                                  397.26  397.26
                                          397.26  397.26
                                          397.26  397.26
Pier Skew, UpSta & Num, DnSta & Num=  ,813.74, 2 ,855.74, 2 , 0 , 0 , 0 ,,
     1.5     1.5
       0     399
     1.5     1.5
       0     399
Pier Skew, UpSta & Num, DnSta & Num=  ,844.99, 2 ,886.99, 2 , 0 , 0 , 0 ,,
     1.5     1.5
       0     399
     1.5     1.5
       0     399
Pier Skew, UpSta & Num, DnSta & Num=  ,876.24, 2 ,918.24, 2 , 0 , 0 , 0 ,,
     1.5     1.5
       0     399
     1.5     1.5
       0     399
Pier Skew, UpSta & Num, DnSta & Num=  ,907.49, 2 ,949.49, 2 , 0 , 0 , 0 ,,
     1.5     1.5
       0     399
     1.5     1.5
       0     399
Pier Skew, UpSta & Num, DnSta & Num=  ,938.74, 2 ,980.74, 2 , 0 , 0 , 0 ,,
     1.5     1.5
       0     399
     1.5     1.5
       0     399
Pier Skew, UpSta & Num, DnSta & Num=  ,969.99, 2 ,1011.99, 2 , 0 , 0 , 0 ,,
     1.5     1.5
       0     399
     1.5     1.5
       0     399
Pier Skew, UpSta & Num, DnSta & Num=  ,1001.24, 2 ,1043.24, 2 , 0 , 0 , 0 ,,
     1.5     1.5
       0     399
     1.5     1.5
       0     399
Pier Skew, UpSta & Num, DnSta & Num=  ,1032.49, 2 ,1074.49, 2 , 0 , 0 , 0 ,,
     1.5     1.5
       0     399
     1.5     1.5
       0     399
Pier Skew, UpSta & Num, DnSta & Num=  ,1063.74, 2 ,1105.74, 2 , 0 , 0 , 0 ,,
     1.5     1.5
       0     399
     1.5     1.5
       0     399
Pier Skew, UpSta & Num, DnSta & Num=  ,2511, 2 ,2573, 2 , 0 , 0 , 0 ,,
     1.5     1.5
       0     399
     1.5     1.5
       0     399
Pier Skew, UpSta & Num, DnSta & Num=  ,2540.43, 2 ,2602.43, 2 , 0 , 0 , 0 ,,
     1.5     1.5
       0     399
     1.5     1.5
       0     399
Pier Skew, UpSta & Num, DnSta & Num=  ,2569.86, 2 ,2631.86, 2 , 0 , 0 , 0 ,,
     1.5     1.5
       0     399
     1.5     1.5
       0     399
Pier Skew, UpSta & Num, DnSta & Num=  ,2599.29, 2 ,2661.29, 2 , 0 , 0 , 0 ,,
     1.5     1.5
       0     399
     1.5     1.5
       0     399
Pier Skew, UpSta & Num, DnSta & Num=  ,2628.72, 2 ,2690.72, 2 , 0 , 0 , 0 ,,
     1.5     1.5
       0     399
     1.5     1.5
       0     399
Pier Skew, UpSta & Num, DnSta & Num=  ,2658.15, 2 ,2720.15, 2 , 0 , 0 , 0 ,,
     1.5     1.5
       0     399
     1.5     1.5
       0     399
Pier Skew, UpSta & Num, DnSta & Num=  ,2687.58, 2 ,2749.58, 2 , 0 , 0 , 0 ,,
     1.5     1.5
       0     399
     1.5     1.5
       0     399
Pier Skew, UpSta & Num, DnSta & Num=  ,2717.01, 2 ,2779.01, 2 , 0 , 0 , 0 ,,
     1.5     1.5
       0     399
     1.5     1.5
       0     399
Pier Skew, UpSta & Num, DnSta & Num=  ,2746.44, 2 ,2808.44, 2 , 0 , 0 , 0 ,,
     1.5     1.5
       0     399
     1.5     1.5
       0     399
Pier Skew, UpSta & Num, DnSta & Num=  ,2775.87, 2 ,2837.87, 2 , 0 , 0 , 0 ,,
     1.5     1.5
       0     399
     1.5     1.5
       0     399
Pier Skew, UpSta & Num, DnSta & Num=  ,2805.3, 2 ,2867.3, 2 , 0 , 0 , 0 ,,
     1.5     1.5
       0     399
     1.5     1.5
       0     399
Pier Skew, UpSta & Num, DnSta & Num=  ,2834.73, 2 ,2896.73, 2 , 0 , 0 , 0 ,,
     1.5     1.5
       0     399
     1.5     1.5
       0     399
Pier Skew, UpSta & Num, DnSta & Num=  ,2864.16, 2 ,2926.16, 2 , 0 , 0 , 0 ,,
     1.5     1.5
       0     399
     1.5     1.5
       0     399
Pier Skew, UpSta & Num, DnSta & Num=  ,2893.59, 2 ,2955.59, 2 , 0 , 0 , 0 ,,
     1.5     1.5
       0     399
     1.5     1.5
       0     399
Pier Skew, UpSta & Num, DnSta & Num=  ,2923.02, 2 ,2985.02, 2 , 0 , 0 , 0 ,,
     1.5     1.5
       0     399
     1.5     1.5
       0     399
Pier Skew, UpSta & Num, DnSta & Num=  ,2952.45, 2 ,3014.45, 2 , 0 , 0 , 0 ,,
     1.5     1.5
       0     399
     1.5     1.5
       0     399
Pier Skew, UpSta & Num, DnSta & Num=  ,2981.88, 2 ,3043.88, 2 , 0 , 0 , 0 ,,
     1.5     1.5
       0     399
     1.5     1.5
       0     399
Pier Skew, UpSta & Num, DnSta & Num=  ,3011.31, 2 ,3073.31, 2 , 0 , 0 , 0 ,,
     1.5     1.5
       0     399
     1.5     1.5
       0     399
Pier Skew, UpSta & Num, DnSta & Num=  ,3040.74, 2 ,3102.74, 2 , 0 , 0 , 0 ,,
     1.5     1.5
       0     399
     1.5     1.5
       0     399
Pier Skew, UpSta & Num, DnSta & Num=  ,3070.17, 2 ,3132.17, 2 , 0 , 0 , 0 ,,
     1.5     1.5
       0     399
     1.5     1.5
       0     399
Pier Skew, UpSta & Num, DnSta & Num=  ,3099.6, 2 ,3161.6, 2 , 0 , 0 , 0 ,,
     1.5     1.5
       0     399
     1.5     1.5
       0     399
Pier Skew, UpSta & Num, DnSta & Num=  ,3129.03, 2 ,3191.03, 2 , 0 , 0 , 0 ,,
     1.5     1.5
       0     399
     1.5     1.5
       0     399
Pier Skew, UpSta & Num, DnSta & Num=  ,3158.46, 2 ,3220.46, 2 , 0 , 0 , 0 ,,
     1.5     1.5
       0     399
     1.5     1.5
       0     399
Pier Skew, UpSta & Num, DnSta & Num=  ,3187.89, 2 ,3249.89, 2 , 0 , 0 , 0 ,,
     1.5     1.5
       0     399
     1.5     1.5
       0     399
Pier Skew, UpSta & Num, DnSta & Num=  ,3217.32, 2 ,3279.32, 2 , 0 , 0 , 0 ,,
     1.5     1.5
       0     399
     1.5     1.5
       0     399
Pier Skew, UpSta & Num, DnSta & Num=  ,3246.75, 2 ,3308.75, 2 , 0 , 0 , 0 ,,
     1.5     1.5
       0     399
     1.5     1.5
       0     399
Pier Skew, UpSta & Num, DnSta & Num=  ,3276.18, 2 ,3338.18, 2 , 0 , 0 , 0 ,,
     1.5     1.5
       0     399
     1.5     1.5
       0     399
Pier Skew, UpSta & Num, DnSta & Num=  ,3305.61, 2 ,3367.61, 2 , 0 , 0 , 0 ,,
     1.5     1.5
       0     399
     1.5     1.5
       0     399
Pier Skew, UpSta & Num, DnSta & Num=  ,3335.04, 2 ,3397.04, 2 , 0 , 0 , 0 ,,
     1.5     1.5
       0     399
     1.5     1.5
       0     399
Pier Skew, UpSta & Num, DnSta & Num=  ,3364.47, 2 ,3426.47, 2 , 0 , 0 , 0 ,,
     1.5     1.5
       0     399
     1.5     1.5
       0     399
Pier Skew, UpSta & Num, DnSta & Num=  ,3393.9, 2 ,3455.9, 2 , 0 , 0 , 0 ,,
     1.5     1.5
       0     399
     1.5     1.5
       0     399
Pier Skew, UpSta & Num, DnSta & Num=  ,3423.33, 2 ,3485.33, 2 , 0 , 0 , 0 ,,
     1.5     1.5
       0     399
     1.5     1.5
       0     399
Pier Skew, UpSta & Num, DnSta & Num=  ,3452.76, 2 ,3514.76, 2 , 0 , 0 , 0 ,,
     1.5     1.5
       0     399
     1.5     1.5
       0     399
Pier Skew, UpSta & Num, DnSta & Num=  ,3482.19, 2 ,3544.19, 2 , 0 , 0 , 0 ,,
     1.5     1.5
       0     399
     1.5     1.5
       0     399
Pier Skew, UpSta & Num, DnSta & Num=  ,3511.62, 2 ,3573.62, 2 , 0 , 0 , 0 ,,
     1.5     1.5
       0     399
     1.5     1.5
       0     399
Pier Skew, UpSta & Num, DnSta & Num=  ,3541.05, 2 ,3603.05, 2 , 0 , 0 , 0 ,,
     1.5     1.5
       0     399
     1.5     1.5
       0     399
Pier Skew, UpSta & Num, DnSta & Num=  ,3570.48, 2 ,3632.48, 2 , 0 , 0 , 0 ,,
     1.5     1.5
       0     399
     1.5     1.5
       0     399
Pier Skew, UpSta & Num, DnSta & Num=  ,3599.91, 2 ,3661.91, 2 , 0 , 0 , 0 ,,
     1.5     1.5
       0     399
     1.5     1.5
       0     399
Pier Skew, UpSta & Num, DnSta & Num=  ,3629.34, 2 ,3691.34, 2 , 0 , 0 , 0 ,,
     1.5     1.5
       0     399
     1.5     1.5
       0     399
Pier Skew, UpSta & Num, DnSta & Num=  ,3658.77, 2 ,3720.77, 2 , 0 , 0 , 0 ,,
     1.5     1.5
       0     399
     1.5     1.5
       0     399
Pier Skew, UpSta & Num, DnSta & Num=  ,3688.2, 2 ,3750.2, 2 , 0 , 0 , 0 ,,
     1.5     1.5
       0     399
     1.5     1.5
       0     399
Pier Skew, UpSta & Num, DnSta & Num=  ,3717.63, 2 ,3779.63, 2 , 0 , 0 , 0 ,,
     1.5     1.5
       0     399
     1.5     1.5
       0     399
Pier Skew, UpSta & Num, DnSta & Num=  ,3747.06, 2 ,3809.06, 2 , 0 , 0 , 0 ,,
     1.5     1.5
       0     399
     1.5     1.5
       0     399
Pier Skew, UpSta & Num, DnSta & Num=  ,3776.49, 2 ,3838.49, 2 , 0 , 0 , 0 ,,
     1.5     1.5
       0     399
     1.5     1.5
       0     399
Pier Skew, UpSta & Num, DnSta & Num=  ,3805.92, 2 ,3867.92, 2 , 0 , 0 , 0 ,,
     1.5     1.5
       0     399
     1.5     1.5
       0     399
Pier Skew, UpSta & Num, DnSta & Num=  ,3835.35, 2 ,3897.35, 2 , 0 , 0 , 0 ,,
     1.5     1.5
       0     399
     1.5     1.5
       0     399
Pier Skew, UpSta & Num, DnSta & Num=  ,3864.78, 2 ,3926.78, 2 , 0 , 0 , 0 ,,
     1.5     1.5
       0     399
     1.5     1.5
       0     399
Pier Skew, UpSta & Num, DnSta & Num=  ,3894.21, 2 ,3956.21, 2 , 0 , 0 , 0 ,,
     1.5     1.5
       0     399
     1.5     1.5
       0     399
Pier Skew, UpSta & Num, DnSta & Num=  ,5199.84, 2 ,5261.84, 2 , 0 , 0 , 0 ,,
     1.5     1.5
       0     399
     1.5     1.5
       0     399
Pier Skew, UpSta & Num, DnSta & Num=  ,5231.09, 2 ,5293.09, 2 , 0 , 0 , 0 ,,
     1.5     1.5
       0     399
     1.5     1.5
       0     399
Pier Skew, UpSta & Num, DnSta & Num=  ,5262.34, 2 ,5324.34, 2 , 0 , 0 , 0 ,,
     1.5     1.5
       0     399
     1.5     1.5
       0     399
Pier Skew, UpSta & Num, DnSta & Num=  ,5293.59, 2 ,5355.59, 2 , 0 , 0 , 0 ,,
     1.5     1.5
       0     399
     1.5     1.5
       0     399
Pier Skew, UpSta & Num, DnSta & Num=  ,5324.84, 2 ,5386.84, 2 , 0 , 0 , 0 ,,
     1.5     1.5
       0     399
     1.5     1.5
       0     399
Pier Skew, UpSta & Num, DnSta & Num=  ,5356.09, 2 ,5418.09, 2 , 0 , 0 , 0 ,,
     1.5     1.5
       0     399
     1.5     1.5
       0     399
Pier Skew, UpSta & Num, DnSta & Num=  ,5387.34, 2 ,5449.34, 2 , 0 , 0 , 0 ,,
     1.5     1.5
       0     399
     1.5     1.5
       0     399
Pier Skew, UpSta & Num, DnSta & Num=  ,5419, 2 ,5481, 2 , 0 , 0 , 0 ,,
     1.5     1.5
       0     399
     1.5     1.5
       0     399
Abutment Skew #Up #Dn= , 2 , 2
  779.34  810.69
  397.26     382
  831.34  862.69
  397.26     380
Abutment Skew #Up #Dn= , 2 , 2
 1064.49 1074.51
     378  397.26
 1116.49 1126.51
     378  397.26
Abutment Skew #Up #Dn= , 2 , 2
 2495.53 2528.59
  397.26  378.99
 2556.38 2590.59
  397.26  383.75
Abutment Skew #Up #Dn= , 2 , 2
    3869    3919
  384.32  397.26
 3952.18 3983.94
  384.32  397.26
Abutment Skew #Up #Dn= , 2 , 2
 5165.44    5229
  397.26   381.4
 5227.445297.699
  397.26     380
Abutment Skew #Up #Dn= , 2 , 2
 5389.79 5438.44
     382  397.26
5440.345 5500.44
     380  397.26
BR Coef=-1 , 0 , 0 ,, 0 ,,,0.8,-1,,0,
WSPro=,,,, 1 ,,,, 0 ,,,, 0 ,,,,-1 ,-1 ,-1 , 0 , 0 , 0 , 0 , 0
BC Mult= 3 ,0,2488,0,2550
BC Mult= 3 ,1083,5158,1130,5220
BC Mult= 3 ,3946,12872.07,4008,13242.49
BR U #Sta/Elev= 472
       0  411.95   39.92  411.64   54.88  411.17   84.82  410.93  119.75  410.22
  134.71  409.42  159.66  409.08  169.64  409.14  219.53  407.19  244.48   406.5
  274.42  406.06  364.23  403.62  409.13  402.24  439.07  401.21  454.04  400.12
  478.99  399.44  488.97   398.7  533.88  397.54  583.78  396.71  603.74  395.75
  618.71  395.39  633.68  395.35  643.66  394.68   673.6  394.18  693.56  393.52
  703.54  392.64  713.53  390.92  723.51  389.74  738.48  390.26  758.44  390.07
  768.42   389.5  783.39  387.24  798.36  385.91  818.32  384.79   828.3  385.22
  843.27  385.25  848.26  384.78  858.24  378.97  863.23  377.95   878.2  377.75
  893.17  378.23  899.91  378.78  918.12  378.95  923.11  380.13  933.09   383.6
  938.08  384.61  958.04  386.81  992.97  386.78 1007.94  386.39 1032.89  386.38
 1052.85  387.55  1077.8  390.71 1092.77  391.41 1112.74  391.42 1152.66  390.43
 1172.62  390.26  1182.6  390.47 1197.57  390.14 1217.53  390.33 1237.49  390.04
 1267.43  390.33 1297.37  389.95 1342.28  390.39 1357.25  389.92  1382.2  389.97
 1417.13  389.65 1427.11  389.94 1491.99  389.91 1591.79  389.07 1611.75  388.99
 1626.72   388.5 1651.67  388.44 1671.63  388.65 1681.61   388.1 1711.55  388.21
 1741.49  387.76 1806.36  387.28 1816.34   387.8 1826.32  387.09 1841.29   386.9
 1881.22  387.07  1891.2  386.68 1921.14  386.52 1946.09  386.88 1966.05  386.51
 1976.03  386.95    1991  386.73 1995.99  387.17 2010.96  386.68 2025.93   386.9
 2035.91   386.5 2070.84  386.47  2090.8  386.85 2100.78  386.77 2135.71     387
 2155.67  386.49 2170.64  387.09 2210.56  386.95 2225.53   387.3  2240.5  387.14
 2270.44  387.39 2280.42  386.99 2300.38  387.02 2345.29  386.45 2355.27  386.61
 2370.24  386.12 2380.22   386.4  2395.2  385.89 2475.04  386.83 2514.96  386.76
 2529.93  387.13 2549.89  387.16 2589.81   387.5 2624.74  387.95 2709.57  388.22
 2839.31  388.34 2909.17  388.08 2928.61   387.7  2944.1  387.28 2979.06  386.81
 2984.05  386.52    3000  386.02    3060  377.23    3087  375.14    3135  377.85
    3144  381.15  3173.2   384.2  3180.6  386.45 3265.85  388.66  3292.6   388.4
 3368.91  388.57 3378.91  388.95  3398.9  388.48  3413.9  388.59 3448.89  386.79
 3478.89  387.36 3488.89  386.99 3518.88  387.42 3543.88  387.29 3548.88  386.74
 3560.43  387.54 3593.87  387.26 3628.86  386.22 3678.85  385.59 3708.85  382.93
 3733.84  381.32 3738.84  381.76 3763.84  379.14 3778.84  379.23 3788.83  381.98
 3803.83  383.46 3813.83  383.94 3833.83  386.68 3853.82  388.21 3878.82  392.75
 3893.82  394.47 3918.81  394.89 3933.81  393.57 3953.81  390.35  3978.8  387.01
  4043.4  383.03 4073.79  382.54 4083.78  382.58 4108.78  382.03 4148.77   382.2
 4163.77  381.79 4183.76   381.7 4218.76  381.95 4228.76  381.62 4243.75  382.16
 4258.75  381.97 4288.74  382.35 4298.74  382.83 4323.74  382.52 4343.73   382.8
 4358.73  382.24 4378.73  382.83 4418.72   383.1 4443.71  383.13 4463.71  382.57
 4483.71  383.05  4508.7  382.74  4533.7  382.85 4558.69  382.32 4603.68  382.79
 4638.68  382.58 4648.67  382.94 4713.66  382.77 4753.65  382.17 4768.65  382.58
 4823.64  382.86 4863.63  382.61 4873.63  382.36 4918.62  382.76 4963.61  382.59
  5038.6  382.49  5048.6   382.2 5093.59  382.02 5123.58  382.17 5133.58  381.95
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BR U #Mann= 5
       0     .06  364.23      .1    3000    .045  3180.6      .1  4043.4     .06
BR D #Sta/Elev= 490
       0  412.32   39.92   412.4   69.86  411.97   79.84  411.47  114.78  411.12
  144.72  410.36  214.58  409.41  269.47  408.14  314.39   407.3  364.29     405
  414.19  402.42  429.03  401.38  503.21  397.45     523  396.89  537.84  395.57
  562.56  394.49  597.18  392.57  661.48  389.96  681.26  390.02  715.88  389.02
  755.45  388.89  829.74  387.59  849.74  387.47  869.74  386.59  894.74  384.34
  904.74  382.28  919.74  377.97  939.74  380.79  944.74  380.31  959.73  385.01
  969.73   386.1 1049.73  385.96 1074.72   385.3 1104.72  385.17 1124.72  384.64
 1149.72  385.52 1179.72  385.65 1199.71  385.23 1234.71  385.46 1259.71  385.49
  1319.7  386.04  1329.7  385.41  1344.7   385.4  1419.7  386.29 1459.69  386.44
 1479.69  385.93 1494.69  386.31 1514.69  386.14 1534.69  386.62 1544.68  386.06
 1579.68  386.54 1619.68  386.31 1624.68  385.98 1679.67  386.09 1689.67  385.78
 1719.67  386.52 1749.67  385.73 1779.66  386.45 1809.66   385.6 1834.66  386.39
 1844.66  386.07 1889.76  385.85 1904.65  386.72 1919.65  386.79 1929.65  385.86
 1974.65  386.76 1984.65  386.43 2069.64  386.39 2079.64  385.95 2094.64  386.63
 2204.63     387 2234.62  387.31 2274.62  386.43 2289.62  385.48 2304.62  385.96
 2354.61  386.72 2369.61  386.04  2429.6  386.01  2449.6   385.7  2479.6     387
  2504.6  387.22  2514.6  386.46 2539.59  386.34 2554.59  384.73 2569.59   385.1
 2584.59  386.83 2604.59  387.25 2614.59  386.94 2629.58  387.48 2644.58  386.73
 2674.58  387.23 2684.58   386.6 2714.58  387.36 2734.57  387.05 2759.57  387.58
 2769.57     387 2779.57  387.89 2794.57  387.76 2814.57  388.41 2849.56  388.67
 2864.56  388.41 2899.56  388.91 2934.55   388.5 2964.55  388.69 2969.55  388.24
 2999.55  387.75 3019.55  386.12 3024.55  384.79 3034.55  377.64 3039.54  375.64
 3059.54  372.63 3069.54   372.5 3099.54   374.4 3104.54  375.23 3109.54   379.5
 3114.54  385.78 3124.54  387.45 3144.53  386.85 3164.53  386.84 3179.53  385.26
 3184.53  385.97 3214.53   387.4 3229.53  387.25 3269.52   388.5 3289.52  388.75
 3299.52  388.21 3339.52  388.17 3359.51  388.56 3389.51  388.61 3399.51  388.22
 3424.51  388.62  3444.5  387.66  3454.5  387.86  3484.5  387.21  3519.5  387.42
  3544.5  387.17 3554.49  386.21 3599.49  386.86 3654.48  386.74 3679.48  385.81
 3734.48  386.11 3749.47  380.99 3764.47  380.74 3774.47   379.8 3789.47  380.65
 3799.47  383.41 3804.47  383.74 3824.47  382.93 3829.47  383.55 3854.46  384.42
 3864.46   384.3 3874.46  382.82 3884.46  382.44 3919.46  384.09 3934.46  386.67
 3954.45  392.59 3969.45  396.47 3984.45  397.12 3989.45  396.47 4004.45  391.34
 4014.45   388.9 4024.45  385.29 4044.45  383.22 4064.44  383.81 4084.44  380.69
 4114.44  380.95 4134.44  381.89 4154.44  381.04 4179.43  382.26 4199.43  382.64
 4204.43  381.72 4214.43  382.01 4224.43  380.54 4234.43  381.52 4249.43  381.17
 4264.42  381.73 4274.42  380.52 4294.42  381.36 4328.25  381.38 4354.42  381.61
 4359.42  382.08 4369.41  381.05 4389.41  380.62 4394.41  381.55 4409.41  380.77
 4419.41   381.5 4439.41  380.92  4494.4     381  4504.4  381.54  4514.4  380.79
  4529.4  380.63  4549.4  381.62  4564.4   381.2 4599.39  381.05 4609.39  381.44
 4629.39  381.06 4644.39  381.97 4659.39  381.06 4679.38  381.65 4689.38  381.18
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BR D #Mann= 7
       0     .06  755.45      .1 3019.55    .045 3114.54      .1 4114.44     .06
 9863.81     .0511303.25     .06
BC Design=,, 0 ,, 0 ,,,,,,
BC Use User HTab Curves=0
BC User HTab FreeFlow(D)= 0

Type RM Length L Ch R = 1 ,145581  ,610.33,596.36,709.2
BEGIN DESCRIPTION:
DS Bridge
END DESCRIPTION:
XS GIS Cut Line= 5
2585793.847482066969356.22303589 2585453.44560386969592.18844323
2585067.069408066969715.433275482576798.406155396971570.90200548
2572906.119648646972233.83440664
#Sta/Elev= 30
       0  412.32  314.39   407.3  755.45  388.89  869.74  386.59  919.74  377.97
  969.73   386.1 3019.55  386.12 3039.54  375.64 3069.54   372.5 3104.54  375.23
 3114.54  385.78 3734.48  386.11 3774.47   379.8 3919.46  384.09 3984.45  397.12
 4024.45  385.29 4114.44  380.95 6219.23  383.92 7184.14  403.31 7509.11  398.23
 7689.09  402.41 8744.04  404.58 9658.89  387.04 9863.81  390.0410463.58  387.05
11303.25  393.88 12207.9  430.2512332.85  429.6712807.66  408.5113242.49  428.22
#Mann= 7 ,-1 , 0
       0     .06       0  755.45      .1       0 3019.55    .045       0
 3114.54      .1       0 4114.44     .06       0 9863.81     .05       0
11303.25     .06       0
#XS Ineff= 5 ,-1
     473     800     399    1156    2526     399    4014    5197     399
    5530  8021.8     399  8021.8   11810     412
Permanent Ineff=
       F       F       F       F       F
Bank Sta=3019.55,3114.54
XS Rating Curve= 0 ,0
Exp/Cntr=0.5,0.3

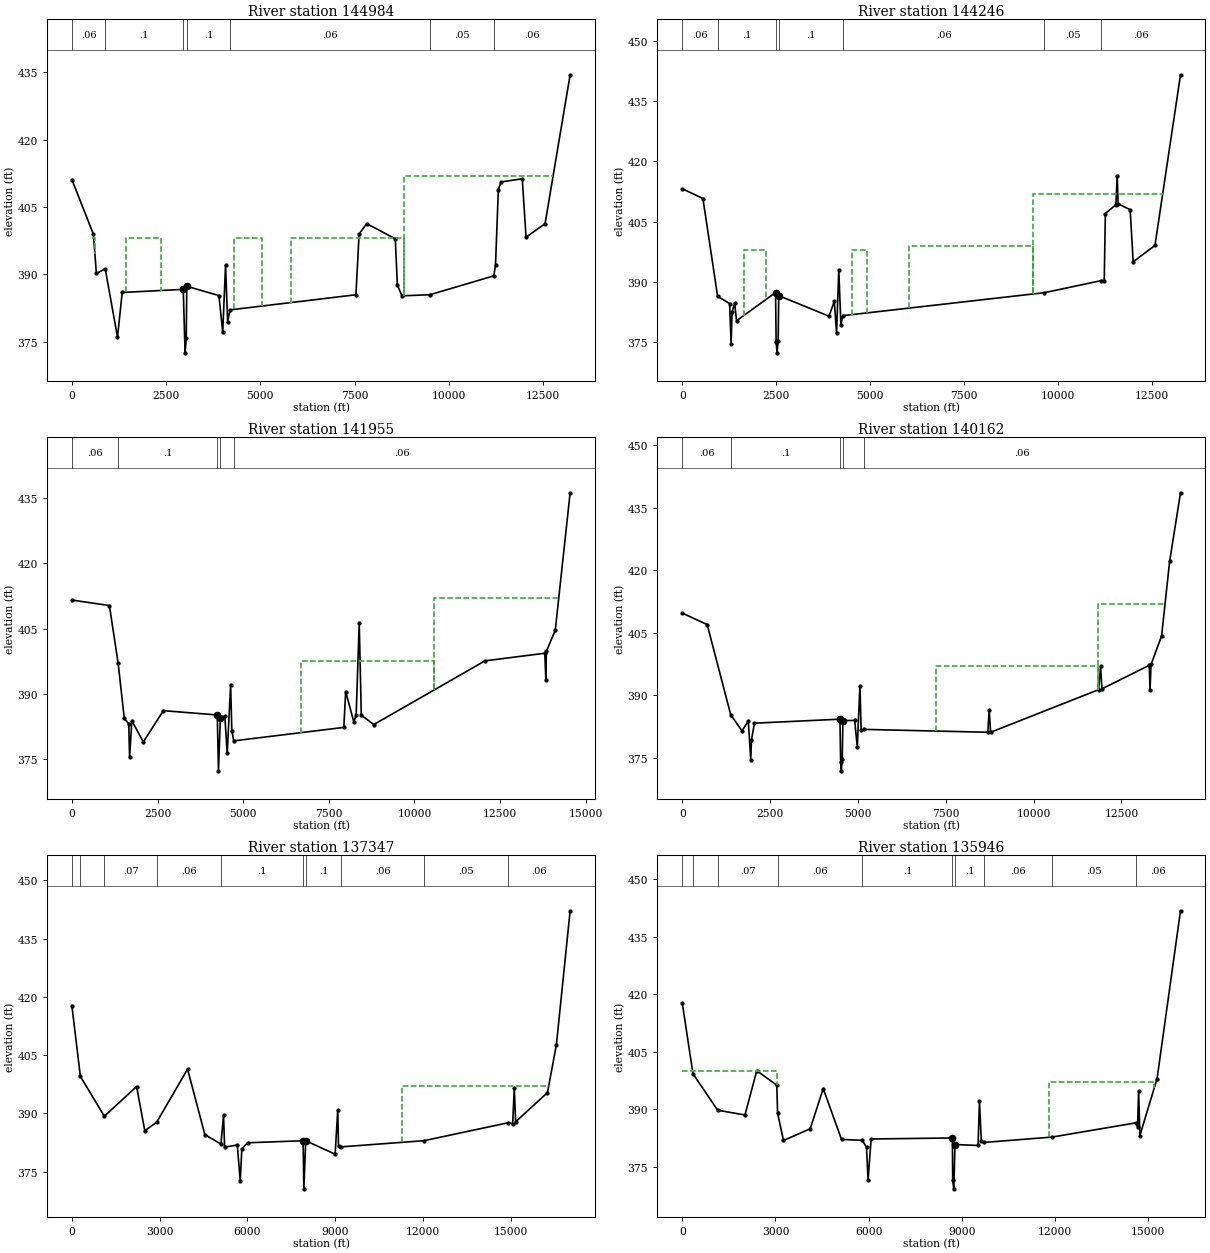
Type RM Length L Ch R = 1 ,144984  ,396.08,738.67,487.7
XS GIS Cut Line= 4
2585748.316733236968851.845435722582994.018764146969639.33008122
2582629.083470396969601.311456472572893.098677316971821.50780348
#Sta/Elev= 30
       0  411.09  569.93  398.94  649.92  390.18   884.9  391.19 1209.86  375.98
 1334.85  385.94  2953.9  386.63 3003.49  372.49 3033.24  375.81 3048.11  387.32
 3901.29  385.25 4001.25  377.06 4076.21  392.04 4131.19  379.45 4196.16  382.06
  7534.7  385.43 7619.66  398.96 7819.58  401.28 8579.26   397.9 8634.24  387.61
 8754.19  385.19  9498.9  385.4411193.24  389.6411238.22  392.1311313.19  408.86
11388.17  410.5711947.95  411.2712047.91  398.2512552.71  401.2713217.45  434.44
#Mann= 7 ,-1 , 0
       0     .06       0   884.9      .1       0  2953.9    .045       0
 3048.11      .1       0 4196.16     .06       0  9498.9     .05       0
11193.24     .06       0
#XS Ineff= 5 ,-1
     528   611.3     398  1428.2  2359.7     398  4297.5  5041.2     398
  5808.9  8805.9     398  8805.9   12770     412
Permanent Ineff=
       F       F       F       F       F
Bank Sta=2953.9,3048.11
XS Rating Curve= 0 ,0
Exp/Cntr=0.3,0.1

Type RM Length L Ch R = 1 ,144246  ,996.8,2290.6,970.11
XS GIS Cut Line= 4
2585725.855820136968509.505897312583488.458392056969101.31147222
2583143.202848976969073.846960232572810.633291056971422.20217164
#Sta/Elev= 30
       0  413.23  549.84  410.78  939.73  386.51 1259.64  384.67 1299.63  374.65
 1324.62  382.62  1394.6   384.7 1444.59   380.4 2482.57  387.42 2497.41  375.16
 2522.15  372.43 2551.84  375.36 2566.69  386.64 3905.24  381.54 4045.19  385.24
 4105.17  377.35 4165.15  393.05 4220.12  379.34 4270.11  381.67 9633.08  387.38
11147.49  390.3811227.46  390.3611257.45  407.0611537.34  409.2511572.32  416.42
11597.31  409.4611917.19  408.0211997.16  395.0712576.93  399.1113256.67  441.54
#Mann= 7 ,-1 , 0
       0     .06       0  939.73      .1       0 2482.57    .045       0
 2566.69      .1       0 4270.11     .06       0 9633.08     .05       0
11147.49     .06       0
#XS Ineff= 4 ,-1
  1637.5    2216     398  4508.2  4926.6     398  6032.3  9319.9     399
  9319.9   12820     412
Permanent Ineff=
       F       F       F       F
Bank Sta=2482.57,2566.69
XS Rating Curve= 0 ,0
Exp/Cntr=0.3,0.1

Type RM Length L Ch R = 1 ,141955  ,997.8,1793.45,1018.19
XS GIS Cut Line= 3
 2585852.56882136967641.064064652573936.548690146970322.70896381
2572012.022355476969004.66763665
#Sta/Elev= 30
       0  411.58 1094.92  410.32  1349.9  397.09 1529.88  384.36 1659.87  383.15
 1684.87  375.39 1749.86  383.86 2084.84  378.93 2669.78  386.15 4244.63  385.16
 4279.62  372.31 4334.62  384.35 4464.61   384.9  4534.6  376.33 4634.59  392.05
 4669.59  381.57 4724.58   379.2 7939.27   382.3 7994.27  390.55 8229.25   383.6
 8299.25  385.05 8389.25  406.32 8449.25  385.11 8814.25  382.9512059.25   397.6
13807.68  399.3513837.65  393.1513852.64  399.7914112.38  404.6114546.96  436.25
#Mann= 5 ,-1 , 0
       0     .06       0  1349.9      .1       0 4244.63    .045       0
 4334.62      .1       0 4724.58     .06       0
#XS Ineff= 2 ,-1
  6686.1 10563.9   397.5 10563.9   14208     412
Permanent Ineff=
       F       F
Bank Sta=4244.63,4334.62
XS Rating Curve= 0 ,0
Exp/Cntr=0.3,0.1

Type RM Length L Ch R = 1 ,140162  ,1496.25,2814.66,1304.27
XS GIS Cut Line= 5
2585738.813799476966733.948096722581561.374975896967726.31159756
2581163.291126396967726.364090892573903.996589886969302.74381214
2572072.786341556968357.96617414
#Sta/Elev= 30
       0   409.7  709.78  406.93 1379.58  385.26 1699.48   381.4 1879.43  383.74
 1949.41   374.5  1969.4  379.22 2054.38  383.25 4487.77  384.21 4507.68   373.9
 4527.58   371.8 4552.46  374.66 4572.37  383.88 4906.75   383.9 4981.73  377.53
 5056.72  392.16 5091.71  381.67 5171.69  381.76 8695.97  381.07 8735.97  386.49
 8775.96  381.0611850.36   391.311905.35  396.8811945.34  391.4913292.78  397.16
13312.74  391.2113342.67  397.3613642.03  404.1713871.53  422.1214180.87   438.6
#Mann= 5 ,-1 , 0
       0     .06       0 1379.58      .1       0 4487.77    .045       0
 4572.37      .1       0 5171.69     .06       0
#XS Ineff= 2 ,-1
  7209.3 11820.9     397 11820.9   13745     412
Permanent Ineff=
       F       F
Bank Sta=4487.77,4572.37
XS Rating Curve= 0 ,0
Exp/Cntr=0.3,0.1

Type RM Length L Ch R = 1 ,137347  ,1140.97,1400.58,978.45
BEGIN DESCRIPTION:
LOB IFA station 3953.68: flow contraction due to natural high ground
END DESCRIPTION:
XS GIS Cut Line= 5
2588787.69779356 6964514.75043542587225.197637726964556.41701873
2585029.793892066965464.120911972573906.166861136968072.27514447
2572454.730787636967259.87585065
#Sta/Elev= 30
       0  417.72  289.64  399.51 1108.62  389.24 2211.87   396.9 2491.35   385.5
  2900.6  387.74 3953.68  401.38 4543.44  384.52 5093.21  382.07 5183.18  389.58
 5218.16  381.28 5652.98  381.84 5752.94  372.55 5807.92  380.84 6002.84  382.41
 7902.06  382.93 7927.05  370.54 7992.02  382.94 8996.63  379.46 9086.59  390.92
 9111.58  381.48 9211.54  381.3612030.44  382.9414919.31  387.5815064.25  387.34
15119.23  396.5615164.22   387.816253.27  395.3416557.95  407.6617027.45  442.18
#Mann= 10 ,-1 , 0
       0     .07       0  289.64     .06       0 1108.62     .07       0
  2900.6     .06       0 5093.21      .1       0 7902.06    .045       0
 7992.02      .1       0 9211.54     .06       012030.44     .05       0
14919.31     .06       0
#XS Ineff= 2 ,-1
       0 3953.68  401.38 11285.9   16316     397
Permanent Ineff=
       F       F
Bank Sta=7902.06,7992.02
XS Rating Curve= 0 ,0
Exp/Cntr=0.3,0.1

Type RM Length L Ch R = 1 ,135946  ,940.19,1679.57,1522.42
BEGIN DESCRIPTION:
LOB IFA station 4539.01: flow contraction due to natural high ground
END DESCRIPTION:
XS GIS Cut Line= 6
2588792.906116476964431.417268722584150.093551736964534.61555314
2580302.000198056965452.483468062580109.291593976965663.42103831
2574802.434097476966908.357196732573353.168295226966005.53551157
#Sta/Elev= 30
       0  417.71  344.92  399.25 1139.74  389.77 2019.54  388.52 2399.46  400.06
 3044.33  396.28 3069.32  389.04 3259.28  381.88  4119.1  384.93 4539.01  395.41
  5128.5  382.15 5797.82  381.93 5932.68  380.11 5982.63  371.58 6082.53  382.27
 8698.51  382.54 8708.36   371.5 8742.84  369.29 8782.25  380.83 9525.19  380.58
 9570.15  392.06 9630.11  381.72 9715.04  381.3711908.33  382.7714611.02  386.48
14660.95  385.3914695.89  394.8314735.83  383.18   15290  398.0216043.86   441.7
#Mann= 10 ,-1 , 0
       0     .07       0  344.92     .06       0 1139.74     .07       0
 3069.32     .06       0 5797.82      .1       0 8698.51    .045       0
 8782.25      .1       0 9715.04     .06       011908.33     .05       0
14611.02     .06       0
#XS Ineff= 3 ,-1
       0 3044.33     400 3044.33 4539.01  395.41 11795.9   15196     397
Permanent Ineff=
       F       F       F
Bank Sta=8698.51,8782.25
XS Rating Curve= 0 ,0
Exp/Cntr=0.3,0.1