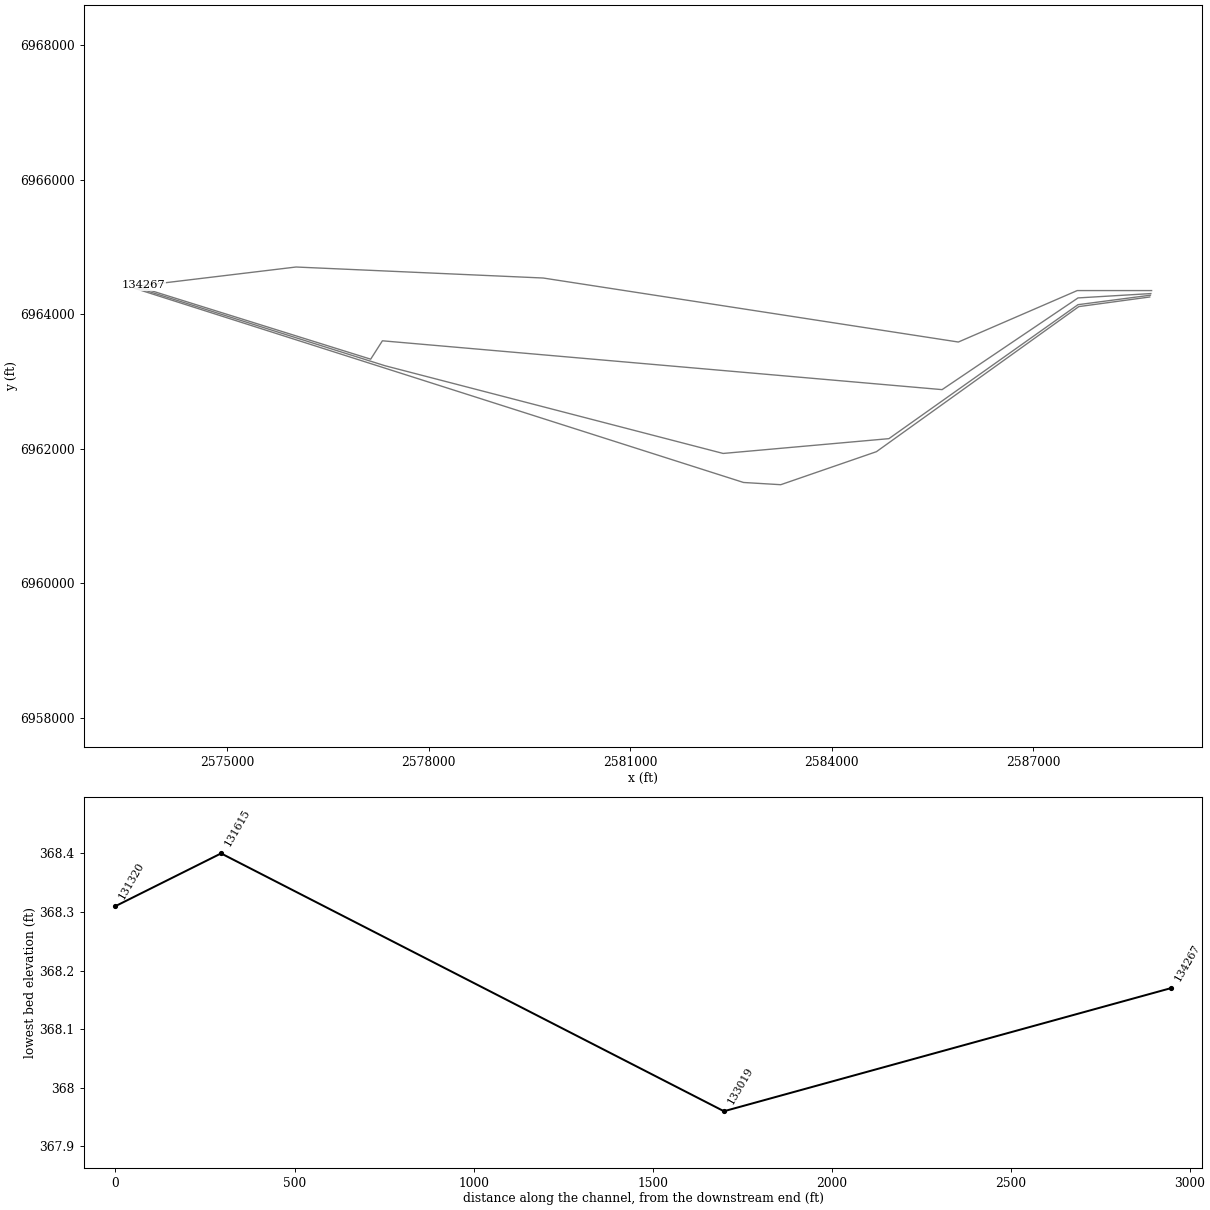
HEC-RAS study EF_FEMA.prj: East_Fork_FEMA

--- EF_FEMA.g06 (geometry) --- (continued)

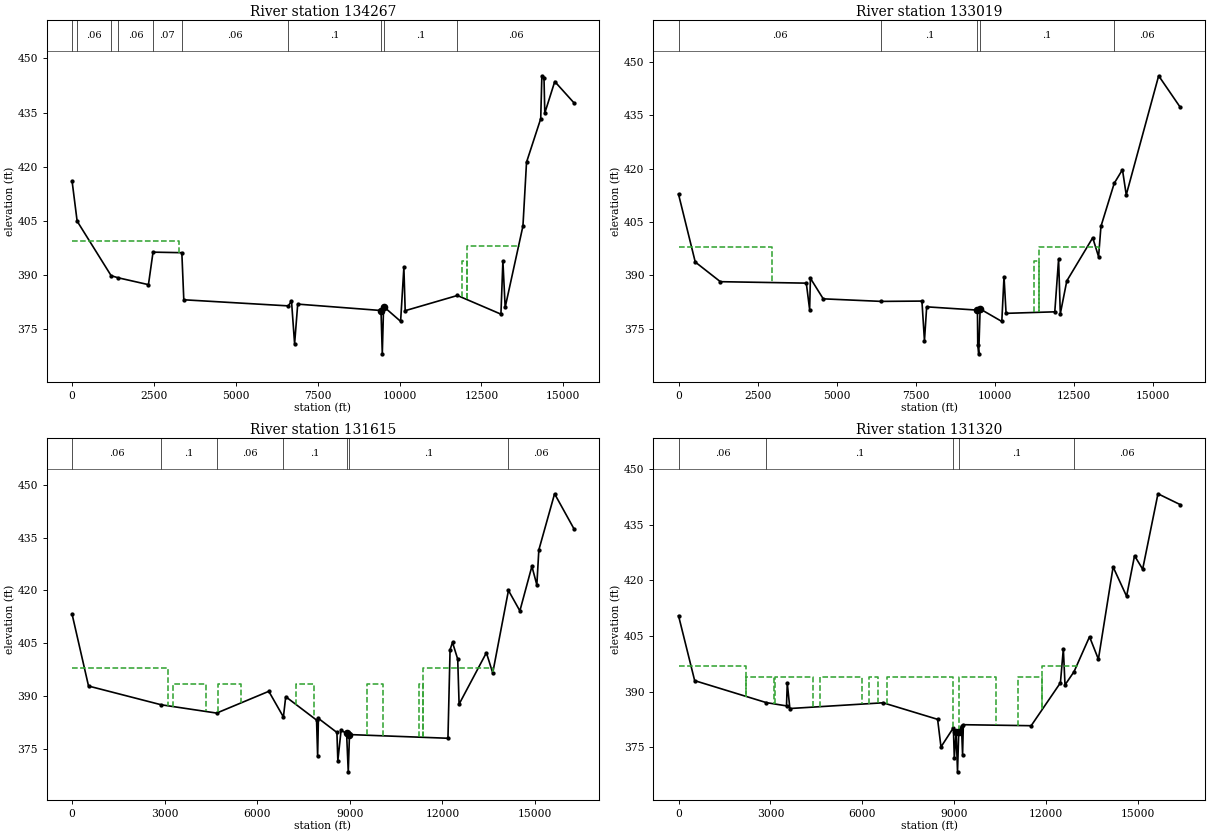
Type RM Length L Ch R = 1 ,134267  ,945.86,1247.61,984.8
BEGIN DESCRIPTION:
LOB IFA station 3271.67: flow contraction due to natural high ground
END DESCRIPTION:
XS GIS Cut Line= 6
2588765.04134281 6964353.29209692587657.48942405 6964353.2920969
2585886.656023476963587.667315812579703.193652886964540.00497806
2576021.786645646964703.762524562573752.039544726964430.88282098
#Sta/Elev= 30
       0  416.04  154.66  404.91 1192.52  389.82 1402.44  389.24 2332.08  387.33
 2472.03  396.33 3351.63  396.18 3411.59  383.14 6604.72  381.45 6699.67  382.82
 6794.61  370.95 6889.55  381.94 9432.35  380.17 9472.12  368.17  9511.9  381.27
10031.17  377.1710131.13   392.110171.11  380.1211765.49  384.33 13094.6  379.16
13154.33  393.8813224.02  381.0613766.57  403.5613876.08  421.2414309.42  433.28
14344.31  445.1714409.11  444.6914434.03  434.8614738.08  443.5815321.25  437.71
#Mann= 10 ,-1 , 0
       0     .07       0  154.66     .06       0 1192.52     .07       0
 1402.44     .06       0 2472.03     .07       0 3351.63     .06       0
 6604.72      .1       0 9432.35    .045       0  9511.9      .1       0
11765.49     .06       0
#XS Ineff= 3 ,-1
       0 3271.67   399.5 11907.712051.15     39412051.15   13675     398
Permanent Ineff=
       F       F       F
Bank Sta=9432.35,9511.9
XS Rating Curve= 0 ,0
Exp/Cntr=0.3,0.1

Type RM Length L Ch R = 1 ,133019  ,1384.23,1404.04,669.16
XS GIS Cut Line= 6
2588754.190642716964308.587461892587669.034348476964243.83037356
2585644.468515726962879.449572152577308.228298476963605.97731856
2577133.749316726963332.53987332 2573698.65415286964403.53904365
#Sta/Elev= 30
       0  412.81  528.58  393.76 1321.74  388.24 4037.95  387.83 4142.85  380.42
 4167.82   389.2 4572.66  383.42 6407.22   382.7 7691.92  382.79  7771.9  371.67
 7841.88  381.17 9446.45  380.25 9456.44  370.33 9486.43  367.96 9531.42  380.58
10216.23  377.0610286.21  389.6410351.19  379.3411890.76  379.77 12010.6  394.56
12065.49  379.23 12270.1  388.4513089.62  400.5913274.52  395.2613349.47  403.79
13769.23   415.914029.07  419.72   14149  412.64 15173.4  446.11   15858  437.22
#Mann= 5 ,-1 , 0
       0     .06       0 6407.22      .1       0 9446.45    .045       0
 9531.42      .1       013769.23     .06       0
#XS Ineff= 3 ,-1
       0    2945     398 11247.311390.75     39411390.75   13291     398
Permanent Ineff=
       F       F       F
Bank Sta=9446.45,9531.42
XS Rating Curve= 0 ,0
Exp/Cntr=0.3,0.1

Type RM Length L Ch R = 1 ,131615  ,369.03,295,387.25
XS GIS Cut Line= 6
 2588747.15948886964284.194794152587668.760726976964143.37617815
2584852.372658976962150.103589892582383.203056636961929.92128748
2577347.612734146963234.825829892573662.195892396964391.82023506
#Sta/Elev= 30
       0  413.26  533.43   392.8 2888.33  387.47 4683.03  385.11 6372.96   391.3
  6846.4     384 6921.16  389.77 7920.21  383.12 7955.18   372.8 7980.17   383.6
  8579.8   379.6 8609.78  371.55 8714.72   380.2 8893.24  379.32 8947.46   368.4
 8986.89     37912176.84  377.9512245.58  403.1412324.14  405.2112492.83  400.45
 12537.8  387.6513422.28  402.2713627.16  396.5214136.86  419.9914506.64  414.18
14896.42  426.8615056.32  421.5615121.28  431.5215630.99  447.4816255.62  437.57
#Mann= 7 ,-1 , 0
       0     .06       0 2888.33      .1       0 4683.03     .06       0
  6846.4      .1       0 8893.24    .045       0 8986.89      .1       0
14136.86     .06       0
#XS Ineff= 7 ,-1
       0  3102.4     398  3278.5  4337.6   393.5  4728.8    5473   393.5
  7256.4  7839.6   393.5  9555.7 10058.1   393.5   1123111374.45   393.5
11374.45   13635     398
Permanent Ineff=
       F       F       F       F       F       F       F
Bank Sta=8893.24,8986.89
XS Rating Curve= 0 ,0
Exp/Cntr=0.5,0.3

Type RM Length L Ch R = 1 ,131320  ,172.92,142.52,224.66
BEGIN DESCRIPTION:
US Bridge
END DESCRIPTION:
XS GIS Cut Line= 6
2588737.414429566964257.794584482587680.556963226964114.56554022
2584666.667977886961956.290001142583241.320762986961464.97044572
2582687.501332556961497.956600232573617.924983556964386.61191215
#Sta/Elev= 30
       0  410.48  526.75  392.94 2864.51  387.01 3524.75  386.12 3549.73  392.26
 3634.65  385.41 6678.04  386.96 8457.71  382.49 8567.68  375.03 8972.61   380.2
  9002.6  372.04 9062.59  379.12 9107.58  368.31 9148.43  379.19 9237.55  380.64
 9272.55   372.9 9297.54  381.0411512.11  380.7712466.92  392.36 12561.9  401.53
12616.89  391.7912911.93  395.3713416.74  404.7913706.68  398.7314186.59  423.64
 14626.5  415.7314886.45  426.68 15151.4  423.05 15651.3  443.4116381.16  440.47
#Mann= 5 ,-1 , 0
       0     .06       0 2864.51      .1       0 8972.61    .045       0
 9148.43      .1       012911.93     .06       0
#XS Ineff= 9 ,-1
       0    2215     397    2215    3121     394    3163    4396     394
    4630    6005     394 6209.61    6503     394 6792.79    8960     394
    9165   10375     394   11085   11880     394   11880   13035     397
Permanent Ineff=
       F       F       F       F       F       F       F       F       F
Bank Sta=9062.59,9148.43
XS Rating Curve= 0 ,0
Exp/Cntr=0.5,0.3