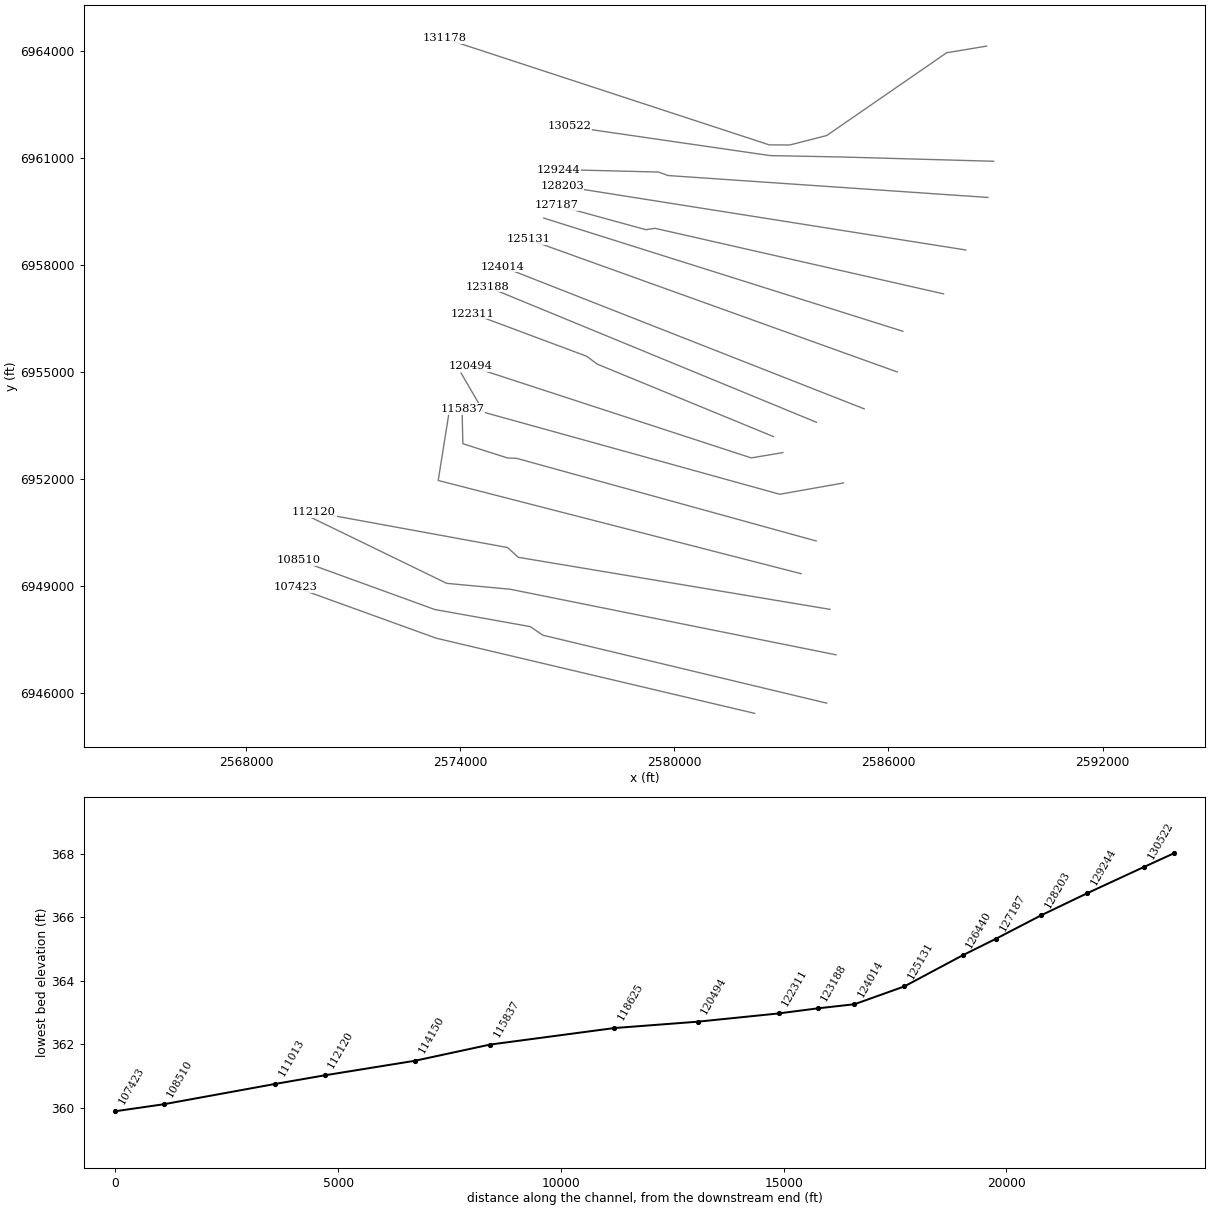
HEC-RAS study EF_FEMA.prj: East_Fork_FEMA

--- EF_FEMA.g06 (geometry) --- (continued)

Type RM Length L Ch R = 4 ,131240  ,,,
BEGIN DESCRIPTION:
Railroad Bridge - bridge deck outside surveyed area is cut from LiDAR of road
END DESCRIPTION:
Node Name=Railroad Bridge
Bridge Culvert--1,0,-1,-1, 0
Deck Dist Width WeirC Skew NumUp NumDn MinLoCord MaxHiCord MaxSubmerge Is_Ogee
80,15,2.6,0, 95, 95, , , 0.98, 0, 0,0,,
       0  259.61 399.298 543.738 716.297 859.676 988.6681068.0431241.5991410.504
1520.0191694.2542077.9462337.0112770.3863009.7563309.437 3579.15 3878.834162.129
4167.096 4384.754400.5334400.533    4420    4420 4508.58    4628    4628  4640.4
4648.8484782.3954955.4725078.8055236.6725365.5135494.4025632.3715769.9255888.922
5968.253  6009.5  6020.36022.794 6022.97    6050    6050 6108.41 6109.12 6197.82
 6198.94    6205    6205 6210.19 6211.826349.977  6492.3 6513.37 6518.36 6681.04
 6783.52 6785.71 6810.066813.5216902.5357080.6167453.7967985.4688260.4628480.457
 8970.96 8970.96 8971.12 9057.41 9147.36 9152.91 9152.919419.7079708.87210062.85
10362.03   10380   1108011129.5411502.7612000.6712500.19 13004.713504.0214002.82
14501.6415000.7215504.7816003.8516423.07
   422.9  417.09 414.533  412.92 410.678 409.014  406.83 404.276 403.763 401.548
 400.654 397.339 396.435 395.513 394.409 393.724  393.75 392.925 392.651 392.419
 392.423   392.8   392.8   392.8   392.8   392.8  393.13  392.93  392.93  392.93
  392.93 392.794 392.531 392.346 392.563 392.305 391.779  391.93 392.654  392.93
  392.93  392.93  392.93  392.93  392.93  392.93  392.93  392.91  392.91  392.91
  392.91  392.91  392.91  392.95     393  393.45  393.45  393.84  393.84  393.84
  393.84  393.46  393.46  393.35   393.2   393.1 392.785 392.185 392.159 392.575
 392.814 392.814 392.814 392.814 392.814 392.814 392.814 392.814 392.292 392.321
 392.485 392.485 392.485 392.485 393.112 396.772 401.172 406.391 412.651 418.383
 425.237 430.523 436.601 441.731 441.195
                          389.64  389.64  389.64  389.64  389.64
                                  389.45  389.45   389.5   389.5  389.47  389.47
                                                          388.63   388.8  388.85
  388.85  388.77
          384.96   385.6  385.53  385.54   385.5
         387.485 387.485
       0  259.61 399.298 543.738 716.297 859.676 988.6681068.0431241.5991410.504
1520.0191694.2542077.9462337.0112770.3863009.7563309.437 3579.15 3878.834162.129
4167.096 4384.754400.5334400.533    4420    4420 4508.58    4628    4628  4640.4
4648.8484782.3954955.4725078.8055236.6725365.5135494.4025632.3715769.9255888.922
5968.253  6009.5 6020.546022.794 6022.97    6050    6050 6108.41 6109.12 6197.82
 6198.96    6205    6205 6210.19 6211.826349.977  6492.3 6513.37 6515.16 6681.04
 6784.36 6785.71 6810.066813.5216902.5357080.6167453.7967985.4688260.4628480.457
 8977.96 8977.96 8978.28 9066.58 9160.15 9160.15 9160.159419.7079708.87210062.85
10362.03   10380   1108011129.5411502.7612000.6712500.19 13004.713504.0214002.82
14501.6415000.7215504.7816003.8516423.07
   422.9  417.09 414.533  412.92 410.678 409.014  406.83 404.276 403.763 401.548
 400.654 397.339 396.435 395.513 394.409 393.724  393.75 392.925 392.651 392.419
 392.423   392.8   392.8   392.8   392.8   392.8  393.13  392.93  392.93  392.93
  392.93 392.794 392.531 392.346 392.563 392.305 391.779  391.93 392.654  392.93
  392.93  392.93  392.93  392.93  392.93  392.93  392.93  392.91  392.91  392.91
  392.91  392.91  392.91  392.95     393  393.45  393.45  393.84  393.84  393.84
  393.84  393.46  393.46  393.35   393.2   393.1 392.785 392.185 392.159 392.575
 392.814 392.814 392.814 392.814 392.814 392.814 392.814 392.814 392.292 392.321
 392.485 392.485 392.485 392.485 393.112 396.772 401.172 406.391 412.651 418.383
 425.237 430.523 436.601 441.731 441.195
                          389.64  389.64  389.64  389.64  389.64
                                  389.45  389.45   389.5   389.5  389.47  389.47
                                                          388.63  388.75  388.85
  388.84  388.77
          384.96  385.59  385.53   385.5  385.04
         387.485 387.485
Pier Skew, UpSta & Num, DnSta & Num=  ,4413.92, 2 ,4414.11, 2 , 0 , 0 , 0 ,,
    1.17    1.17
       0     390
    1.17    1.17
       0     390
Pier Skew, UpSta & Num, DnSta & Num=  ,4426.47, 2 ,4426.47, 2 , 0 , 0 , 0 ,,
    1.17    1.17
       0     390
    1.17    1.17
       0     390
Pier Skew, UpSta & Num, DnSta & Num=  ,4439.57, 2 ,4439.27, 2 , 0 , 0 , 0 ,,
    1.17    1.17
       0     390
    1.17    1.17
       0     390
Pier Skew, UpSta & Num, DnSta & Num=  ,4452.31, 2 ,4451.86, 2 , 0 , 0 , 0 ,,
    1.17    1.17
       0     390
    1.17    1.17
       0     390
Pier Skew, UpSta & Num, DnSta & Num=  ,4464.62, 2 ,4464.53, 2 , 0 , 0 , 0 ,,
    1.17    1.17
       0     390
    1.17    1.17
       0     390
Pier Skew, UpSta & Num, DnSta & Num=  ,4478.09, 2 ,4477.15, 2 , 0 , 0 , 0 ,,
    1.17    1.17
       0     390
    1.17    1.17
       0     390
Pier Skew, UpSta & Num, DnSta & Num=  ,4490.45, 2 ,4489.85, 2 , 0 , 0 , 0 ,,
    1.17    1.17
       0     390
    1.17    1.17
       0     390
Pier Skew, UpSta & Num, DnSta & Num=  ,4502.66, 2 ,4502.62, 2 , 0 , 0 , 0 ,,
    1.17    1.17
       0     390
    1.17    1.17
       0     390
Pier Skew, UpSta & Num, DnSta & Num=  ,4515.11, 2 ,4515.22, 2 , 0 , 0 , 0 ,,
    1.17    1.17
       0     390
    1.17    1.17
       0     390
Pier Skew, UpSta & Num, DnSta & Num=  ,4527.63, 2 ,4527.63, 2 , 0 , 0 , 0 ,,
    1.17    1.17
       0     390
    1.17    1.17
       0     390
Pier Skew, UpSta & Num, DnSta & Num=  ,4540.47, 2 ,4540.65, 2 , 0 , 0 , 0 ,,
    1.17    1.17
       0     390
    1.17    1.17
       0     390
Pier Skew, UpSta & Num, DnSta & Num=  ,4553.04, 2 ,4552.85, 2 , 0 , 0 , 0 ,,
    1.17    1.17
       0     390
    1.17    1.17
       0     390
Pier Skew, UpSta & Num, DnSta & Num=  ,4565.84, 2 ,4565.77, 2 , 0 , 0 , 0 ,,
    1.17    1.17
       0     390
    1.17    1.17
       0     390
Pier Skew, UpSta & Num, DnSta & Num=  ,4578.16, 2 ,4578.48, 2 , 0 , 0 , 0 ,,
    1.17    1.17
       0     390
    1.17    1.17
       0     390
Pier Skew, UpSta & Num, DnSta & Num=  ,4591.06, 2 ,4591.46, 2 , 0 , 0 , 0 ,,
    1.17    1.17
       0     390
    1.17    1.17
       0     390
Pier Skew, UpSta & Num, DnSta & Num=  ,4603.62, 2 ,4603.8, 2 , 0 , 0 , 0 ,,
    1.17    1.17
       0     390
    1.17    1.17
       0     390
Pier Skew, UpSta & Num, DnSta & Num=  ,4615.86, 2 ,4616.14, 2 , 0 , 0 , 0 ,,
    1.17    1.17
       0     390
    1.17    1.17
       0     390
Pier Skew, UpSta & Num, DnSta & Num=  ,6021.68, 2 ,6021.68, 2 , 0 , 0 , 0 ,,
    1.17    1.17
       0     390
    1.17    1.17
       0     390
Pier Skew, UpSta & Num, DnSta & Num=  ,6034.36, 2 ,6034.17, 2 , 0 , 0 , 0 ,,
    1.17    1.17
       0     390
    1.17    1.17
       0     390
Pier Skew, UpSta & Num, DnSta & Num=  ,6047.17, 2 ,6046.78, 2 , 0 , 0 , 0 ,,
    1.17    1.17
       0     390
    1.17    1.17
       0     390
Pier Skew, UpSta & Num, DnSta & Num=  ,6059.45, 2 ,6059.33, 2 , 0 , 0 , 0 ,,
    1.17    1.17
       0     390
    1.17    1.17
       0     390
Pier Skew, UpSta & Num, DnSta & Num=  ,6072.35, 2 ,6071.94, 2 , 0 , 0 , 0 ,,
    1.17    1.17
       0     390
    1.17    1.17
       0     390
Pier Skew, UpSta & Num, DnSta & Num=  ,6084.75, 2 ,6084.56, 2 , 0 , 0 , 0 ,,
    1.17    1.17
       0     390
    1.17    1.17
       0     390
Pier Skew, UpSta & Num, DnSta & Num=  ,6098.03, 2 ,6098.13, 2 , 0 , 0 , 0 ,,
    1.17    1.17
       0     390
    1.17    1.17
       0     390
Pier Skew, UpSta & Num, DnSta & Num=  ,6110.17, 2 ,6110.34, 2 , 0 , 0 , 0 ,,
    1.17    1.17
       0     390
    1.17    1.17
       0     390
Pier Skew, UpSta & Num, DnSta & Num=  ,6122.38, 2 ,6122.56, 2 , 0 , 0 , 0 ,,
    1.17    1.17
       0     390
    1.17    1.17
       0     390
Pier Skew, UpSta & Num, DnSta & Num=  ,6135.45, 2 ,6135.35, 2 , 0 , 0 , 0 ,,
    1.17    1.17
       0     390
    1.17    1.17
       0     390
Pier Skew, UpSta & Num, DnSta & Num=  ,6148.05, 2 ,6147.81, 2 , 0 , 0 , 0 ,,
    1.17    1.17
       0     390
    1.17    1.17
       0     390
Pier Skew, UpSta & Num, DnSta & Num=  ,6160.7, 2 ,6160.62, 2 , 0 , 0 , 0 ,,
    1.17    1.17
       0     390
    1.17    1.17
       0     390
Pier Skew, UpSta & Num, DnSta & Num=  ,6172.97, 2 ,6173.33, 2 , 0 , 0 , 0 ,,
    1.17    1.17
       0     390
    1.17    1.17
       0     390
Pier Skew, UpSta & Num, DnSta & Num=  ,6185.68, 2 ,6185.9, 2 , 0 , 0 , 0 ,,
    1.17    1.17
       0     390
    1.17    1.17
       0     390
Pier Skew, UpSta & Num, DnSta & Num=  ,6198.77, 2 ,6198.77, 2 , 0 , 0 , 0 ,,
    1.17    1.17
       0     390
    1.17    1.17
       0     390
Pier Skew, UpSta & Num, DnSta & Num=  ,6543.86, 2 ,6543.25, 2 , 0 , 0 , 0 ,,
    1.17    1.17
       0     390
    1.17    1.17
       0     390
Pier Skew, UpSta & Num, DnSta & Num=  ,6575.73, 2 ,6575.24, 2 , 0 , 0 , 0 ,,
    1.17    1.17
       0     390
    1.17    1.17
       0     390
Pier Skew, UpSta & Num, DnSta & Num=  ,6607.76, 2 ,6607.64, 2 , 0 , 0 , 0 ,,
    1.17    1.17
       0     390
    1.17    1.17
       0     390
Pier Skew, UpSta & Num, DnSta & Num=  ,6639.44, 2 ,6639.92, 2 , 0 , 0 , 0 ,,
    1.17    1.17
       0     390
    1.17    1.17
       0     390
Pier Skew, UpSta & Num, DnSta & Num=  ,6672.23, 2 ,6671.18, 2 , 0 , 0 , 0 ,,
    1.17    1.17
       0     390
    1.17    1.17
       0     390
Pier Skew, UpSta & Num, DnSta & Num=  ,6703.67, 2 ,6703.67, 2 , 0 , 0 , 0 ,,
    1.17    1.17
       0     390
    1.17    1.17
       0     390
Pier Skew, UpSta & Num, DnSta & Num=  ,6731.56, 2 ,6732.04, 2 , 0 , 0 , 0 ,,
    1.17    1.17
       0     390
    1.17    1.17
       0     390
Pier Skew, UpSta & Num, DnSta & Num=  ,6759.42, 2 ,6759.74, 2 , 0 , 0 , 0 ,,
    1.17    1.17
       0     390
    1.17    1.17
       0     390
Pier Skew, UpSta & Num, DnSta & Num=  ,9026.85, 4 ,9033.85, 4 , 3 , 3 , 0 ,,
       2       2       3       3
       0  383.03  383.03     388
       2       2       3       3
       0  383.03  383.03     388
Pier Skew, UpSta & Num, DnSta & Num=  ,9029.85, 4 ,9036.85, 4 , 3 , 3 , 0 ,,
       2       2       3       3
       0  383.03  383.03     388
       2       2       3       3
       0  383.03  383.03     388
Pier Skew, UpSta & Num, DnSta & Num=  ,9088.39, 4 ,9095.39, 4 , 3 , 3 , 0 ,,
       2       2       3       3
       0  383.03  383.03     388
       2       2       3       3
       0  383.03  383.03     388
Pier Skew, UpSta & Num, DnSta & Num=  ,9091.39, 4 ,9091.39, 4 , 3 , 3 , 0 ,,
       2       2       3       3
       0  383.03  383.03     388
       2       2       3       3
       0  383.03  383.03     388
Pier Skew, UpSta & Num, DnSta & Num=  ,10410, 2 ,10410, 2 , 0 , 0 , 0 ,,
    1.17    1.17
       0     390
    1.17    1.17
       0     390
Pier Skew, UpSta & Num, DnSta & Num=  ,10440, 2 ,10440, 2 , 0 , 0 , 0 ,,
    1.17    1.17
       0     390
    1.17    1.17
       0     390
Pier Skew, UpSta & Num, DnSta & Num=  ,10470, 2 ,10470, 2 , 0 , 0 , 0 ,,
    1.17    1.17
       0     390
    1.17    1.17
       0     390
Pier Skew, UpSta & Num, DnSta & Num=  ,10500, 2 ,10500, 2 , 0 , 0 , 0 ,,
    1.17    1.17
       0     390
    1.17    1.17
       0     390
Pier Skew, UpSta & Num, DnSta & Num=  ,10530, 2 ,10530, 2 , 0 , 0 , 0 ,,
    1.17    1.17
       0     390
    1.17    1.17
       0     390
Pier Skew, UpSta & Num, DnSta & Num=  ,10560, 2 ,10560, 2 , 0 , 0 , 0 ,,
    1.17    1.17
       0     390
    1.17    1.17
       0     390
Pier Skew, UpSta & Num, DnSta & Num=  ,10590, 2 ,10590, 2 , 0 , 0 , 0 ,,
    1.17    1.17
       0     390
    1.17    1.17
       0     390
Pier Skew, UpSta & Num, DnSta & Num=  ,10620, 2 ,10620, 2 , 0 , 0 , 0 ,,
    1.17    1.17
       0     390
    1.17    1.17
       0     390
Pier Skew, UpSta & Num, DnSta & Num=  ,10650, 2 ,10650, 2 , 0 , 0 , 0 ,,
    1.17    1.17
       0     390
    1.17    1.17
       0     390
Pier Skew, UpSta & Num, DnSta & Num=  ,10680, 2 ,10680, 2 , 0 , 0 , 0 ,,
    1.17    1.17
       0     390
    1.17    1.17
       0     390
Pier Skew, UpSta & Num, DnSta & Num=  ,10710, 2 ,10710, 2 , 0 , 0 , 0 ,,
    1.17    1.17
       0     390
    1.17    1.17
       0     390
Pier Skew, UpSta & Num, DnSta & Num=  ,10740, 2 ,10740, 2 , 0 , 0 , 0 ,,
    1.17    1.17
       0     390
    1.17    1.17
       0     390
Pier Skew, UpSta & Num, DnSta & Num=  ,10770, 2 ,10770, 2 , 0 , 0 , 0 ,,
    1.17    1.17
       0     390
    1.17    1.17
       0     390
Pier Skew, UpSta & Num, DnSta & Num=  ,10800, 2 ,10800, 2 , 0 , 0 , 0 ,,
    1.17    1.17
       0     390
    1.17    1.17
       0     390
Pier Skew, UpSta & Num, DnSta & Num=  ,10830, 2 ,10830, 2 , 0 , 0 , 0 ,,
    1.17    1.17
       0     390
    1.17    1.17
       0     390
Pier Skew, UpSta & Num, DnSta & Num=  ,10860, 2 ,10860, 2 , 0 , 0 , 0 ,,
    1.17    1.17
       0     390
    1.17    1.17
       0     390
Pier Skew, UpSta & Num, DnSta & Num=  ,10890, 2 ,10890, 2 , 0 , 0 , 0 ,,
    1.17    1.17
       0     390
    1.17    1.17
       0     390
Pier Skew, UpSta & Num, DnSta & Num=  ,10920, 2 ,10920, 2 , 0 , 0 , 0 ,,
    1.17    1.17
       0     390
    1.17    1.17
       0     390
Pier Skew, UpSta & Num, DnSta & Num=  ,10950, 2 ,10950, 2 , 0 , 0 , 0 ,,
    1.17    1.17
       0     390
    1.17    1.17
       0     390
Pier Skew, UpSta & Num, DnSta & Num=  ,10980, 2 ,10980, 2 , 0 , 0 , 0 ,,
    1.17    1.17
       0     390
    1.17    1.17
       0     390
Pier Skew, UpSta & Num, DnSta & Num=  ,11010, 2 ,11010, 2 , 0 , 0 , 0 ,,
    1.17    1.17
       0     390
    1.17    1.17
       0     390
Pier Skew, UpSta & Num, DnSta & Num=  ,11040, 2 ,11040, 2 , 0 , 0 , 0 ,,
    1.17    1.17
       0     390
    1.17    1.17
       0     390
Pier Skew, UpSta & Num, DnSta & Num=  ,11070, 2 ,11070, 2 , 0 , 0 , 0 ,,
    1.17    1.17
       0     390
    1.17    1.17
       0     390
BR Coef=-1 , 0 , 0 ,, 0 ,,,0.8,-1,,0,
WSPro=,,,, 1 ,,,, 0 ,,,, 0 ,,,,-1 ,-1 ,-1 , 0 , 0 , 0 , 0 , 0
Culvert=1,4.33,,53,0.024,0.9,1,2,3,385.27,3129.96,385.47,3128.57,Culvert #1  , 0 ,80
 3129.96 3128.57
BC Culvert Barrel=1,,0
Culvert Bottom n=0.024
Culvert=1,4.33,,53,0.024,0.9,1,2,3,385.43,3141.9,385.38,3140.19,Culvert #2  , 0 ,80
  3141.9 3140.19
BC Culvert Barrel=1,,0
Culvert Bottom n=0.024
Culvert=1,4.33,,53,0.024,0.9,1,2,3,385.32,3154.7,385.25,3152.19,Culvert #3  , 0 ,80
  3154.7 3152.19
BC Culvert Barrel=1,,0
Culvert Bottom n=0.024
BC Mult= 2 ,0,4396,0,4396
BC Mult= 3 ,3160,6005,3160,6005
BC Mult= 3 ,4630,6503,4630,6503
BC Mult= 3 ,6210,8960,6210,8970
BC Mult= 3 ,6795,10375,6795,10375
BC Mult= 3 ,9165,16381.16,9170,16466.12
BR U #Sta/Elev= 490
       0  410.48   44.72   408.2   84.48  405.69  159.02  401.84  293.19  397.81
   357.8  397.39  377.67  395.85  387.61  396.58  452.21  396.45     487  395.62
  501.91  393.84  516.82  394.06  526.75  392.94   606.4  392.52  646.23  393.51
  696.02  392.07  715.94  392.46  755.77  392.29  805.55  391.22  855.34  391.39
  920.06   390.4  969.85  390.73 1024.62  389.86 1029.59  390.38 1069.42   390.8
 1089.33  390.51 1154.03  390.51 1193.85  388.67 1278.45     390 1303.34  389.33
 1318.27  390.32 1338.17  389.83 1368.04   390.1 1387.94   389.4 1422.78  390.53
 1452.64  389.42 1472.55  389.66 1512.36  388.79 1542.22  389.42 1582.04  389.47
 1616.88  388.69 1666.65  388.33 1731.45   388.7 1746.44  388.09 1766.42  388.72
 1781.41  388.23  1891.3  387.58 1966.23  388.01 1986.21  387.47 2031.17  387.99
 2076.13  387.58 2111.09  387.73 2131.07  386.84 2161.05  387.76 2196.01  387.28
 2235.97  387.72 2245.97  387.25 2360.86   387.5 2380.84  387.01 2445.78  386.69
  2525.7   387.1 2670.56  386.76 2710.52  387.35  2735.5   386.9 2765.47  387.18
 2864.51  387.01 2895.35  386.63 2920.32  389.11 2935.31  389.64 2955.29  387.07
 2975.27  386.04 3015.24  386.48 3040.21  387.25 3085.17  386.17 3120.14  386.59
 3125.13  385.27  3155.1  385.32 3190.07  386.91 3250.01   386.3 3269.99  387.47
 3334.93  387.62 3384.88   387.1 3399.87  387.44 3449.82  386.67  3469.8  387.15
 3524.75  386.12 3549.73  392.26 3569.71   390.6  3579.7  386.86 3599.68  386.36
 3614.67  387.06 3634.65  385.41  3684.6  386.25 3779.51  386.16  3789.5  386.55
 3834.46  385.77 3874.42  386.37 3909.39  386.23 3924.37  387.23 3949.35  387.23
 3959.34  386.43 4024.28  386.39 4034.27  385.56 4089.22  384.96  4109.2  386.08
 4129.18  385.09 4144.16  385.87 4159.15  385.01 4184.12  385.65 4244.07  384.12
 4299.01   384.5 4363.95  383.91 4388.93  384.79  4423.9  384.39 4448.87  385.19
 4578.75     386 4603.72  385.48 4648.68  385.29 4663.67  384.53 4688.64  385.67
 4698.63  384.89 4743.59  383.71 4798.43  384.38 4813.31  383.82 4833.15  384.62
 4877.78  384.52  4887.7  385.33 4912.49  385.33 4927.37  384.45 4942.25   385.1
 5011.68  384.69 5056.31  385.06 5076.15  384.43 5205.09  384.51 5215.01  386.29
 5234.85  385.96 5254.68  383.77 5269.56  383.44 5329.38  385.11 5354.31  384.48
 5409.14  384.36 5424.09  383.73    5454  384.88 5478.93  383.44 5493.88   384.3
 5563.67  384.71 5583.61  384.31 5603.55  385.28 5623.49   384.1 5678.32  384.95
 5708.23  383.59 5738.14  383.79 5758.08  384.68 5802.94  382.55 5812.91  383.67
  5837.8  383.59 5847.71  384.59 5882.36   383.1 5897.22   383.6 5946.73  383.04
 5971.49  384.58 5986.34  383.79    6021  384.35  6050.7  383.48 6075.46  383.66
 6110.12  386.37 6149.73  384.44 6179.43   384.9 6194.29  383.73 6238.85  384.98
 6258.65  383.27 6278.46  383.81 6293.31  382.89 6323.16  383.01 6343.15  384.47
 6368.15  383.73 6413.13     385 6428.13  383.52 6453.12  383.28  6518.1  386.12
 6583.07  386.53 6608.07  387.08 6643.05  386.15 6678.04  386.96 6703.03  386.27
 6728.03   383.3 6758.02   382.9 6788.01  383.29 6832.99   382.6 6872.98  382.65
 6912.97  383.22 6927.97   382.8 6977.96   383.4 7007.96  382.71 7022.95  383.48
 7052.95  382.69 7107.94  382.71 7122.94   381.8 7147.93  382.35 7187.93  382.13
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BR U #Mann= 5
       0     .06 2864.51      .1 8972.61     .04 9147.57      .112911.93     .06
BR U Banks=8972.61,9147.57
BR D #Sta/Elev= 490
       0  410.02    19.9  407.97   34.82  407.36   74.62  404.12   99.49  401.65
  114.42  401.94  134.32  400.81  179.09  399.64  189.04   398.3  228.84  396.38
  238.79  396.84  293.51  395.39  308.43  394.56  328.33  394.71  358.18  394.07
  407.93  393.74  417.88  394.68  442.75  394.45  462.65  393.54   492.5  394.16
  537.27  392.11  562.15  393.97  582.04  391.95  616.85  393.62  676.52  392.67
  721.27  392.93  741.16   392.2  756.07  392.51  825.69  391.95  885.36  390.55
  905.25  390.65  920.16  389.81  954.97  389.42  989.78  389.71  999.72  389.07
 1074.31   389.6 1089.23  388.49 1158.85  388.84 1168.81  388.31 1183.74  389.22
 1218.57  388.69  1233.5  389.13 1243.45  388.09 1278.29  387.86 1323.08  388.24
 1352.94  387.49 1362.89     388 1387.77  387.13  1402.7  387.94 1512.19  387.79
 1522.14  388.21    1552  387.28 1591.81  388.26 1666.51  387.94 1701.45  386.87
 1726.41  387.61 1746.38  387.18 1781.32   387.6 1801.29  387.04 1821.26  387.72
 1851.21  387.21 1906.12  387.75 1961.03  387.05 1976.01  387.54 2145.74  387.62
 2180.68  387.09 2225.61  387.52 2285.52  387.68  2355.4  387.18 2385.36  387.82
 2440.27  387.23 2555.09  387.43 2580.05  387.21 2595.02  387.86 2644.94  388.11
 2714.83  387.89 2739.79  387.57 2789.71  387.91 2858.58  386.81 2904.53  387.69
 2929.49  386.92 2979.41  386.82 3034.32  385.42 3079.25  386.52  3114.2  386.01
 3134.17  385.25 3204.06  387.13 3234.01  387.12 3263.96   385.8 3288.92  386.54
  3298.9  385.89 3318.87  386.51 3388.76  385.69 3403.74  386.23 3433.69  385.21
 3458.65  386.53 3473.63  389.25  3488.6  390.14 3523.55  385.74 3533.53  386.28
 3568.48  385.94 3593.44   386.9 3653.34  387.12  3678.3  386.36 3703.26  387.87
 3748.19  387.06 3768.16  387.97 3798.11  387.21 3823.07  387.89 3877.98  386.51
 3937.89  386.98 3947.87  386.29 3977.82  386.93 4012.77  386.63 4022.75  386.01
 4047.71  386.91 4072.67  386.59 4092.64  385.37 4162.53  386.26 4187.49  385.51
 4202.47     386 4312.29  386.82 4332.26  385.97 4357.22  385.98 4372.19  386.68
 4407.14  385.88  4432.1   386.2 4467.04  384.82    4492  384.51 4511.97  385.05
 4531.94  384.31 4546.91  385.21 4591.84  384.96 4606.81  385.85  4676.7  385.77
 4716.64  384.69 4746.61  385.26  4766.6  384.78  4796.6  385.56 4806.59  386.36
 4836.59  385.47 4886.57  385.59 4921.56  384.39 4951.56   385.8 4986.55  385.73
 4996.55  384.96 5051.53  385.52 5071.53  384.89 5091.52   385.5 5106.52  384.71
 5146.51  384.96 5156.51  384.03  5186.5  385.11 5216.49  385.38 5281.12   384.3
 5300.98     385 5335.72  384.47 5390.32  385.21 5434.99  384.32 5494.55  384.85
  5514.4  384.15 5564.04  384.69 5578.93  384.15  5623.6  384.86 5658.34  383.35
 5707.98  385.21 5722.87  384.28 5777.47  384.77 5867.12  383.96 5897.05  384.56
    5922     384 5936.97  384.43 5976.88  383.82 6001.83  384.77 6051.72  384.78
 6071.68  384.44 6191.42  384.19 6211.38  384.68 6236.32  383.83 6276.24  383.98
 6301.18  383.65 6311.15  384.37 6395.91  384.67 6415.86  384.38 6430.81  384.97
 6465.72  385.25 6515.57  384.71 6530.53  383.83 6580.39  383.63 6620.28  382.52
 6650.19  383.61 6719.99  383.38 6754.89  383.71 6789.79  383.54 6839.65   382.1
 6849.62  381.43  6889.5  381.91 6919.38  383.46 6949.25  383.11 6969.17   382.3
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BR D #Mann= 5
       0     .06 2858.58      .1 8977.57     .04 9162.53      .111375.92     .06
BC Design=,, 0 ,, 0 ,,,,,,
BC Use User HTab Curves=0
BC User HTab FreeFlow(D)= 0

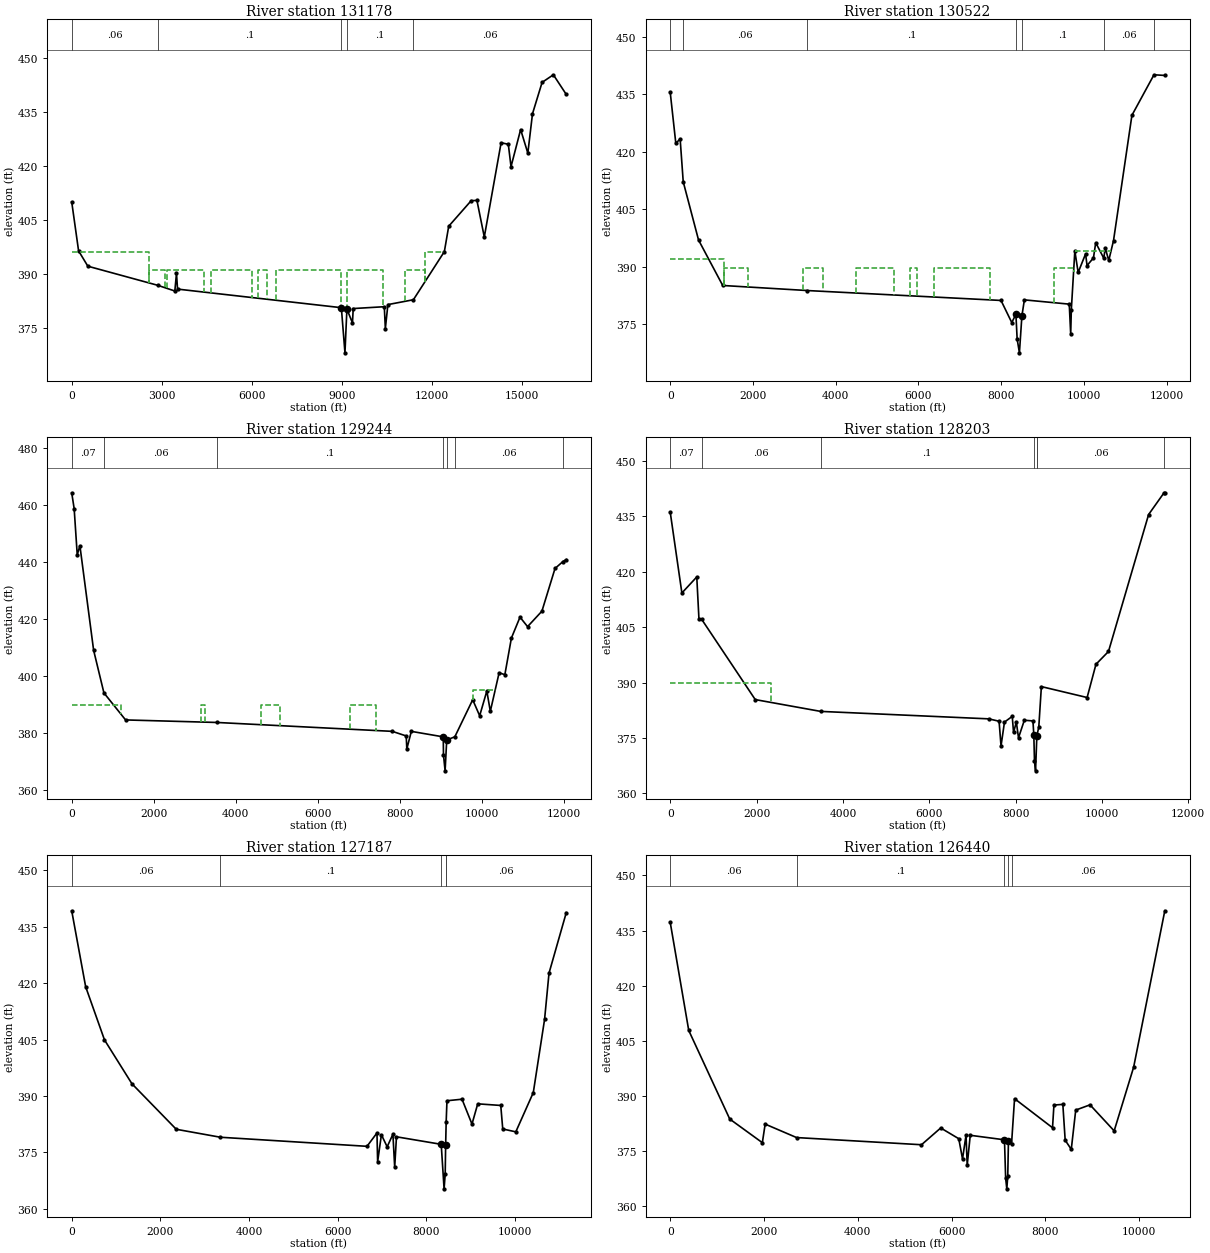
Type RM Length L Ch R = 1 ,131178  ,422.59,655.81,1080.74
BEGIN DESCRIPTION:
DS Bridge
END DESCRIPTION:
XS GIS Cut Line= 6
2588751.538417066964138.107815982587631.747021476963951.91002564
2584272.805904726961633.116434892583239.819781726961368.35974656
2582661.477762556961371.614661312573552.820783056964356.23008314
#Sta/Elev= 30
       0  410.02  228.84  396.38  537.27  392.11 2858.58  386.81 3433.69  385.21
  3488.6  390.14 3523.55  385.74 8977.57  380.57 9097.55  368.01 9162.53  380.19
  9347.5  376.33 9372.49  380.3310407.29  380.8410442.28  374.7810527.27  381.43
11375.92  382.78 12406.9  396.1712551.87  403.2313301.73  410.3513491.69   410.4
13736.64  400.2414296.53  426.4614536.48  426.0214626.47  419.81 14946.4  430.12
15186.36  423.5615341.33  434.5215661.26  443.2516036.19  445.3616466.12  439.89
#Mann= 5 ,-1 , 0
       0     .06       0 2858.58      .1       0 8977.57    .045       0
 9162.53      .1       011375.92     .06       0
#XS Ineff= 9 ,-1
       0    2570     396    2570    3120     391    3156    4397     391
    4630    6005     391 6205.54    6500     391    6790    8970     391
    9170   10375     391   11100   11760     391   11760   12400     396
Permanent Ineff=
       F       F       F       F       F       F       F       F       F
Bank Sta=8977.57,9162.53
XS Rating Curve= 0 ,0
Exp/Cntr=0.5,0.3

Type RM Length L Ch R = 1 ,130522  ,825.93,1278.14,964.51
XS GIS Cut Line= 4
2588948.37726222 6960912.01551492584693.881178056961031.34434448
2582688.672918146961070.406602312577053.341669146961888.04440273
#Sta/Elev= 30
       0  435.45  134.88  422.19  239.78  423.32  314.15  412.16  684.38  396.99
 1268.86  385.14 3316.13  383.82  7996.6  381.24 8256.57  375.48 8356.56  377.63
 8386.56  371.21 8441.55  367.59 8501.54  377.22 8561.53  381.39  9646.4  380.28
 9681.39  372.43 9696.39  378.83 9781.38  394.15 9861.37  388.5310041.35  393.38
10076.34  390.3310231.32  392.3210286.32  396.2910480.97  392.2410516.29  394.91
10601.28  391.6510716.26  396.8311161.21  429.4811694.34  440.0411956.11  439.87
#Mann= 7 ,-1 , 0
       0     .07       0  314.15     .06       0 3316.13      .1       0
 8356.56    .045       0 8501.54      .1       010480.97     .06       0
11694.34     .05       0
#XS Ineff= 8 ,-1
       0    1300     392    1300    1887  389.75    3199    3704  389.75
 4487.91  5401.7  389.75 5803.14 5954.81  389.75 6370.56 7740.43  389.75
 9288.19    9751  389.75 9781.38   10656  394.15
Permanent Ineff=
       F       F       F       F       F       F       F       F
Bank Sta=8356.56,8501.54
XS Rating Curve= 0 ,0
Exp/Cntr=0.3,0.1

Type RM Length L Ch R = 1 ,129244  ,922.95,1040.29,819.79
XS GIS Cut Line= 4
2588788.655140716959898.126794652579823.828582216960512.30896522
2579563.252331726960609.753324152576761.67492963 6960679.7108614
#Sta/Elev= 30
       0  464.15   59.97   458.6  134.94  442.42  199.91  445.61  534.75  408.98
  786.12  394.05 1314.39  384.59  3547.4   383.7  7821.4  380.59 8161.24  378.98
 8176.23  374.44 8286.19  380.58  9065.4  378.66 9070.37  372.34 9110.11  366.76
 9149.85  377.56 9347.56  378.69 9783.65  391.66  9953.5  386.0510128.34  394.73
10213.27   387.610428.07  401.1110567.95  400.4410727.81  413.2710937.62  420.59
11122.45  417.2711472.14  422.6811791.86  437.64 11985.7  440.0712066.61  440.76
#Mann= 7 ,-1 , 0
       0     .07       0  786.12     .06       0  3547.4      .1       0
  9065.4    .045       0 9149.85      .1       0 9347.56     .06       0
 11985.7     .05       0
#XS Ineff= 5 ,-1
       0    1198  389.75    3164    3250  389.75 4620.21 5073.91  389.75
 6790.06 7416.27  389.75 9783.65   10358     395
Permanent Ineff=
       F       F       F       F       F
Bank Sta=9065.4,9149.85
XS Rating Curve= 0 ,0
Exp/Cntr=0.3,0.1

Type RM Length L Ch R = 1 ,128203  ,892.87,1016.38,812.95
BEGIN DESCRIPTION:
ROB IFA station 8596.96: flow contraction due to natural high ground
END DESCRIPTION:
XS GIS Cut Line= 2
 2588170.59961836958425.904673472576855.425070236960216.16946565
#Sta/Elev= 30
       0  436.16   269.9  414.26  614.78  418.61  664.76  407.33  729.43   407.1
  1969.3  385.37 3483.63  382.17  7377.4  380.15 7617.32   379.5  7662.3   372.8
 7742.28  379.27 7922.21  380.82  7952.2  376.48 8017.18  379.28 8067.16  375.01
 8202.12  379.77 8402.04  379.59 8422.03   375.7 8437.02  368.85 8462.01  366.06
    8492  375.48 8493.34  375.63 8536.99  377.92 8596.96  388.89 9656.55  385.93
 9861.47  394.9410151.35  398.4111080.99  435.5311438.12  441.4211455.84  441.42
#Mann= 7 ,-1 , 0
       0     .07       0  729.43     .06       0 3483.63      .1       0
 8422.03    .045       0    8492      .1       0 8493.34     .06       0
11438.12     .05       0
#XS Ineff= 2 , 0
       0    2340  389.75 8596.96       0  388.89
Permanent Ineff=
       F       T
Bank Sta=8422.03,8492
XS Rating Curve= 0 ,0
Exp/Cntr=0.3,0.1

Type RM Length L Ch R = 1 ,127187  ,819.79,746.62,581.31
BEGIN DESCRIPTION:
ROB IFA station 8466.4: flow contraction due to natural high ground
END DESCRIPTION:
XS GIS Cut Line= 4
2587545.599555976957196.737840472579465.025494056959032.61343381
2579203.009285816958995.16993915 2576688.75840886959684.91921581
#Sta/Elev= 30
       0  439.28  314.87  419.07  739.69  404.93 1359.43  393.26 2359.01  381.16
 3356.73  379.04 6662.25  376.63 6887.16  380.18 6902.15  372.52 6987.12  379.71
 7117.07   376.5 7247.02  379.84    7287  371.07 7326.99  379.16 8336.55  377.16
 8401.48  365.32 8426.45  369.23 8436.44  376.85 8448.63  383.17  8466.4  388.75
    8806  389.16 9030.74  382.54 9160.59  387.93 9679.98   387.5 9724.92  381.24
10019.58  380.4810414.12  390.9210668.82   410.4 10768.7  422.6911158.24  438.79
#Mann= 5 ,-1 , 0
       0     .06       0 3356.73      .1       0 8336.55    .045       0
 8436.44      .1       0 8448.63     .06       0
#XS Ineff= 2 , 0
       0                  8466.4       0  388.75
Permanent Ineff=
       F       T
Bank Sta=8336.55,8436.44
XS Rating Curve= 0 ,0
Exp/Cntr=0.3,0.1

Type RM Length L Ch R = 1 ,126440  ,923.46,1309.01,801.58
BEGIN DESCRIPTION:
ROB IFA station 7344.91: flow contraction due to natural high ground
END DESCRIPTION:
XS GIS Cut Line= 2
2586406.710757646956148.126748732576345.008440146959320.33595547
#Sta/Elev= 30
       0  437.24     395  407.86 1269.99  383.77 1964.98  377.35 2024.98   382.4
 2695.31  378.74 5359.95  376.79 5769.94  381.35 6154.93  378.43 6234.93  372.93
 6309.93  379.39 6334.93  371.23 6399.93  379.36 7129.92  378.13 7154.92  367.67
 7179.91   364.8 7199.91  368.28 7214.91  377.93 7280.83  377.04 7344.91  389.32
  8154.9  381.41  8184.9  387.58  8374.9  387.76  8424.9  378.03  8554.9  375.53
  8649.9  386.21  8954.9  387.64  9469.9  380.56  9884.9  397.86 10549.9   440.4
#Mann= 5 ,-1 , 0
       0     .06       0 2695.31      .1       0 7129.92    .045       0
 7214.91      .1       0 7280.83     .06       0
#XS Ineff= 2 , 0
                         7344.91           388.5
Permanent Ineff=
       F       T
Bank Sta=7129.92,7214.91
XS Rating Curve= 0 ,0
Exp/Cntr=0.3,0.1

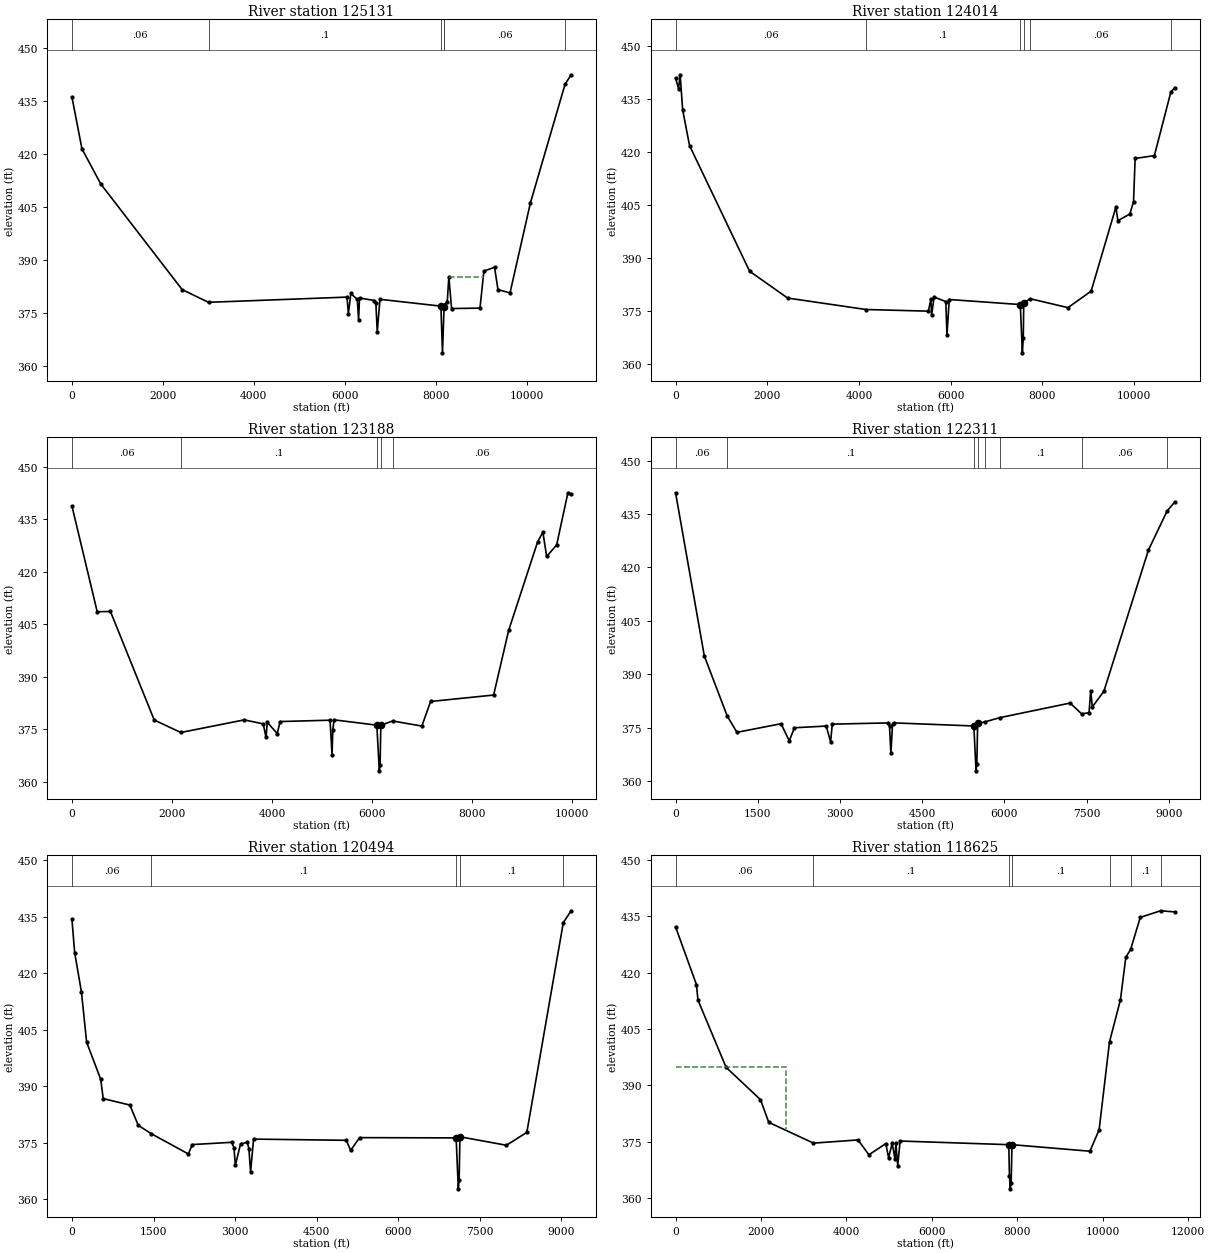
Type RM Length L Ch R = 1 ,125131  ,1133.11,1117.46,1046.76
BEGIN DESCRIPTION:
ROB IFA station 8286.9-9291.5: flow contraction due to natural high ground
END DESCRIPTION:
XS GIS Cut Line= 2
2586246.98830806 6955009.23795042575917.924976726958721.37750773
#Sta/Elev= 30
       0  436.06  219.92  421.44  634.76  411.49 2424.08  381.67  3002.6  378.09
 6047.73  379.56 6077.72  374.87  6132.7  380.58 6272.65  378.91 6302.63  373.14
 6322.63  379.32 6647.51   378.6  6682.5  377.78 6712.48  369.79 6772.46  378.94
 8111.96  377.01 8146.95  363.82 8181.94  376.83 8190.79  377.41 8251.91  378.21
  8286.9  385.35 8346.87  376.33 8971.63  376.45  9056.6  386.88  9291.5     388
 9366.48   381.7 9631.37  380.73 10081.2  406.22 10842.5   439.710975.85  442.35
#Mann= 6 ,-1 , 0
       0     .06       0  3002.6      .1       0 8111.96    .045       0
 8181.94      .1       0 8190.79     .06       0 10842.5     .05       0
#XS Ineff= 3 ,-1
  8286.9    9041  385.35  9056.6    9285  386.88  9291.5    9816     388
Permanent Ineff=
       T       T       T
Bank Sta=8111.96,8181.94
XS Rating Curve= 0 ,0
Exp/Cntr=0.3,0.1

Type RM Length L Ch R = 1 ,124014  ,767.51,826.3,723.53
XS GIS Cut Line= 2
2585323.37729439 6953974.51561042575188.758456056957955.75272664
#Sta/Elev= 30
       0  440.91   64.99  437.86   99.99  441.83  154.98  431.89  304.96  421.82
 1614.79  386.32 2444.68  378.74 4156.33   375.5 5514.32  375.04 5569.31  378.49
 5584.31  373.87  5639.3  379.02 5894.28  377.75 5919.27   368.3 5969.27  378.33
  7519.1   376.9  7564.1  363.26  7584.1  367.51  7594.1  377.38 7734.82  378.55
 8558.96  376.03 9063.86  380.69 9603.76  404.43 9648.75   400.6  9908.7  402.49
 9988.68  405.9610023.67  418.1810443.59  418.9910801.62  436.91 10888.5  438.21
#Mann= 6 ,-1 , 0
       0     .06       0 4156.33      .1       0  7519.1    .045       0
  7594.1      .1       0 7734.82     .06       010801.62     .05       0
Bank Sta=7519.1,7594.1
XS Rating Curve= 0 ,0
Exp/Cntr=0.3,0.1

Type RM Length L Ch R = 1 ,123188  ,833.15,876.2,858.71
XS GIS Cut Line= 2
2583983.099463146953599.515704232574756.466669726957398.46086223
#Sta/Elev= 30
       0  438.74   504.9  408.56  769.85  408.63 1644.69  377.63 2176.71  374.08
 3444.36  377.68 3824.29  376.53 3879.28  372.65 3904.28     377 4104.24  373.75
 4159.23   377.2 5159.05  377.59 5199.04  367.68 5214.04  374.71 5239.03  377.69
 6093.88  376.17 6143.87  363.13 6158.87  364.66 6173.86  376.13  6410.4  377.37
 6993.71  375.91 7168.68  382.93 8428.45  384.77 8728.39   403.2 9308.27  428.52
 9413.25  431.28 9488.24  424.33  9688.2  427.63 9913.16  442.52 9978.14  442.18
#Mann= 5 ,-1 , 0
       0     .06       0 2176.71      .1       0 6093.88    .045       0
 6173.86      .1       0  6410.4     .06       0
Bank Sta=6093.88,6173.86
XS Rating Curve= 0 ,0
Exp/Cntr=0.3,0.1

Type RM Length L Ch R = 1 ,122311  ,1037.56,1817.83,1439.34
XS GIS Cut Line= 4
2582781.710461726953196.737966482577843.536611056955227.33528323
2577545.023100476955449.162923562574360.633471896956638.04440406
#Sta/Elev= 30
       0  440.95  524.94  395.16  943.41  378.33 1119.87  373.77 1924.77  376.18
 2074.75   371.4 2169.74  375.05 2749.67  375.53 2829.66  371.09 2859.65  376.07
 3879.53  376.41 3904.52  375.49 3929.52   367.9 3959.52  376.08 3984.51  376.42
 5443.51  375.55 5483.18  362.97 5498.06  364.77 5512.94  376.26 5638.56  376.67
 5918.49  377.89 7200.94  381.98    7410  378.96 7545.86  379.26 7575.85  385.47
 7605.84  380.91 7815.79  385.25 8630.58  424.92 8971.97  435.88 9110.45  438.35
#Mann= 8 ,-1 , 0
       0     .06       0  943.41      .1       0 5443.51    .045       0
 5512.94      .1       0 5638.56     .06       0 5918.49      .1       0
    7410     .06       0 8971.97     .05       0
Bank Sta=5443.51,5512.94
XS Rating Curve= 0 ,0
Exp/Cntr=0.3,0.1

Type RM Length L Ch R = 1 ,120494  ,913.77,1868.09,1072.39
XS GIS Cut Line= 3
2583044.950092726952749.208349732582157.860003386952599.93863514
2574287.716622966955169.29438882
#Sta/Elev= 30
       0  434.31   49.98  425.45  174.91  414.98  269.87  401.67  529.74  391.77
  574.72  386.67 1064.54  384.97 1219.52  379.58 1460.69  377.34 2139.41  371.98
  2214.4  374.47  2939.3  375.07  2979.3  373.62 3004.29  368.96 3099.28  374.63
 3224.27  375.05 3254.26  373.34 3284.26  367.16 3339.25  375.92 5044.03   375.6
 5124.02  372.93    5289  376.31 7063.76  376.24 7103.76  362.71 7118.76  365.16
 7133.75  376.54 7988.64  374.28 8363.58  377.71 9034.52  433.44 9178.44  436.56
#Mann= 5 ,-1 , 0
       0     .06       0 1460.69      .1       0 7063.76    .045       0
 7133.75      .1       0 9034.52     .05       0
Bank Sta=7063.76,7133.75
XS Rating Curve= 0 ,0
Exp/Cntr=0.3,0.1

Type RM Length L Ch R = 1 ,118625  ,999.53,2788.28,1056.37
BEGIN DESCRIPTION:
LOB IFA station 2575: flow expansion due to natural high ground upstream
END DESCRIPTION:
XS GIS Cut Line= 4
2584740.043815396951898.126718572582956.16811806 6951581.7366033
2574667.002937886953878.489227642574027.625607716954977.34562573
#Sta/Elev= 30
       0  432.12  489.11  416.78  524.05  412.68 1182.86   394.8 1986.64  386.23
 2181.56  380.18 3228.31  374.66  4270.7  375.51 4525.59  371.55 4920.43  374.54
  4985.4  370.81 5070.36  374.61 5135.34  370.42 5155.33  374.67 5200.31  368.68
 5255.29  375.22 7799.21  374.25  7814.2  366.01 7834.19  362.51 7854.18  364.12
 7874.18  374.25 9698.45  372.51 9913.37   378.210156.46  401.5710413.17  412.79
10537.81  424.0410650.56  426.1410876.81  434.6611352.21  436.4211684.44  436.12
#Mann= 7 ,-1 , 0
       0     .06       0 3228.31      .1       0 7799.21    .045       0
 7874.18      .1       010156.46     .08       010650.56      .1       0
11352.21     .05       0
#XS Ineff= 2 , 0
       0    2575     395               0
Permanent Ineff=
       F       F
Bank Sta=7799.21,7874.18
XS Rating Curve= 0 ,0
Exp/Cntr=0.3,0.1

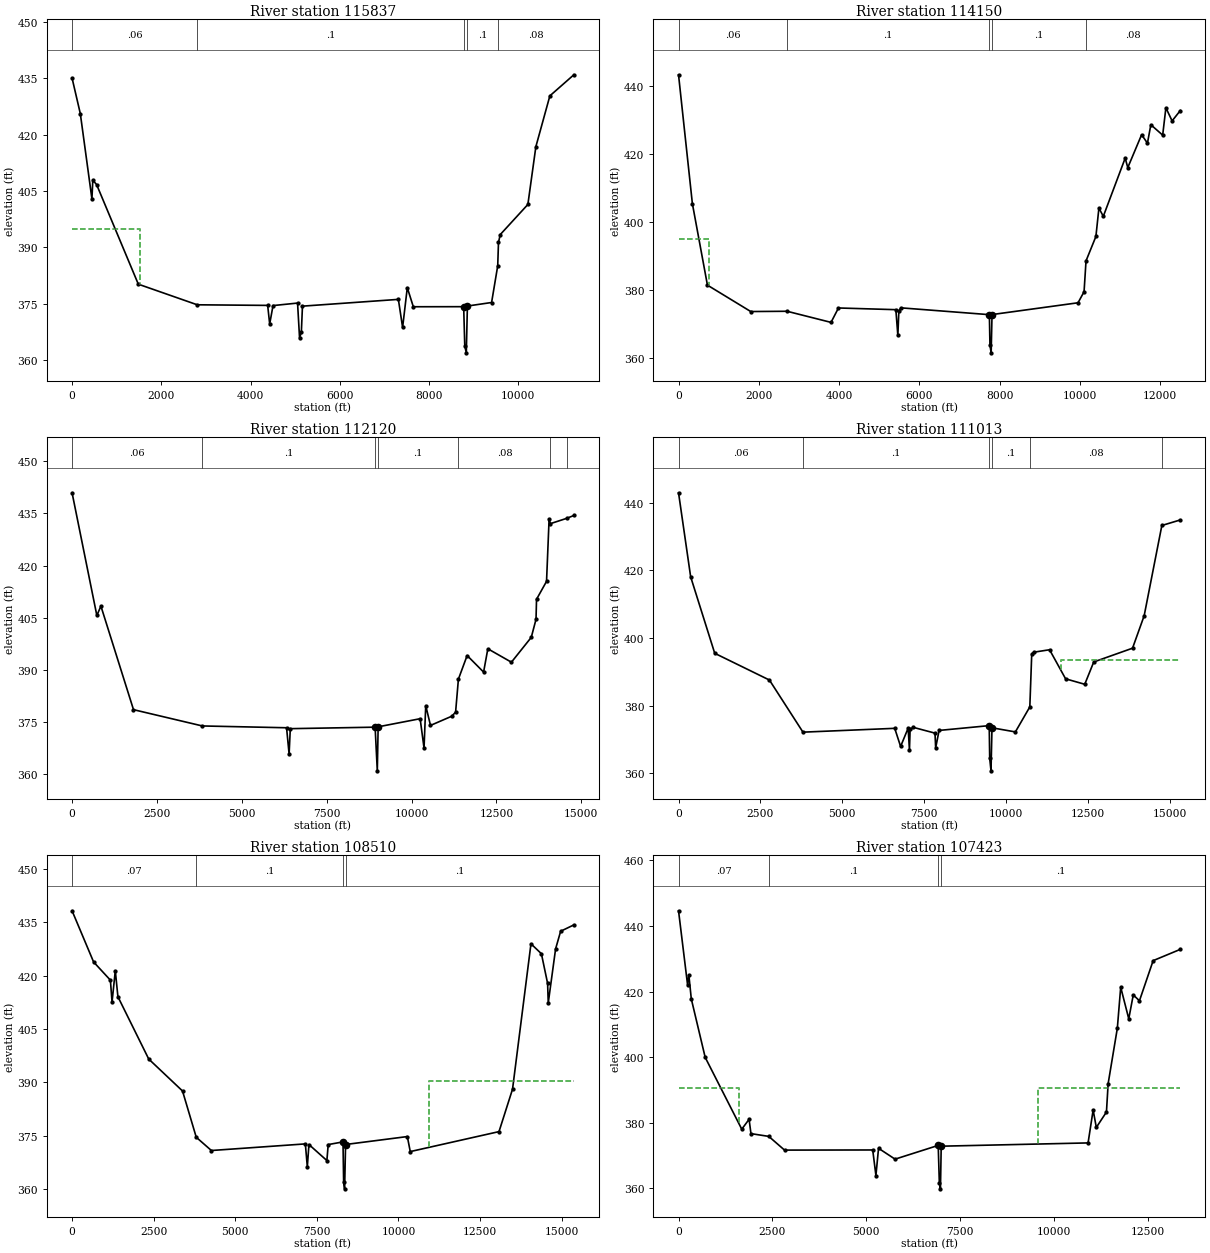
Type RM Length L Ch R = 1 ,115837  ,1090.29,1687.4,1115.36
BEGIN DESCRIPTION:
LOB IFA station 1519: flow expansion due to natural high ground upstream
END DESCRIPTION:
XS GIS Cut Line= 5
2583976.154923226950273.126687722575581.957800886952588.69948439
2575331.481267726952597.600713312574077.046112556952998.23770732
2574055.12588081 6953968.8519078
#Sta/Elev= 30
       0  435.02  184.95  425.57  444.88  402.92  464.88  407.88  549.86  406.72
 1484.61  380.24 2805.92  374.76 4383.84   374.6 4428.83  369.66 4503.81  374.55
 5053.67  375.22 5098.66  365.95 5138.65  367.46 5163.64   374.4 7313.11   376.2
 7408.09  368.74 7513.06  379.32 7648.03  374.24 8776.57  374.26 8801.14  363.85
 8835.54  361.99 8860.11  374.43 9402.35  375.37 9539.66  385.12 9556.98  391.37
 9596.89  393.4310215.44  401.4310394.78   416.810708.43   430.311246.11   435.9
#Mann= 5 ,-1 , 0
       0     .06       0 2805.92      .1       0 8776.57    .045       0
 8860.11      .1       0 9539.66     .08       0
#XS Ineff= 2 , 0
       0    1519     395               0
Permanent Ineff=
       F       F
Bank Sta=8776.57,8860.11
XS Rating Curve= 0 ,0
Exp/Cntr=0.3,0.1

Type RM Length L Ch R = 1 ,114150  ,1285.64,2029.66,1386.13
BEGIN DESCRIPTION:
LOB IFA station 769: flow expansion due to natural high ground upstream
END DESCRIPTION:
XS GIS Cut Line= 3
 2583552.54389386949356.460213972573386.648215136951968.63642006
2573702.10493331 6953946.5294459
#Sta/Elev= 30
       0  443.29  344.87  405.38  719.74   381.4 1799.33  373.63 2702.85  373.71
  3798.6  370.44 3983.54  374.68    5413  374.18 5462.98   366.6 5487.97   373.8
 5537.95  374.72 7742.69  372.71  7757.1  363.72 7787.09  361.48 7808.63  372.74
 9951.25  376.2110101.19  379.4610150.25  388.5410396.08  395.7110471.05  404.06
10580.95  401.6511125.42  418.7611190.36  415.9811535.02  425.6611679.88  423.16
11764.79  428.59 12059.5  425.5312139.43  433.5812294.27  429.7212499.07  432.77
#Mann= 5 ,-1 , 0
       0     .06       0 2702.85      .1       0 7742.69    .045       0
 7808.63      .1       010150.25     .08       0
#XS Ineff= 2 , 0
       0     769     395               0
Permanent Ineff=
       F       F
Bank Sta=7742.69,7808.63
XS Rating Curve= 0 ,0
Exp/Cntr=0.3,0.1

Type RM Length L Ch R = 1 ,112120  ,1016.87,1107.23,1200.11
XS GIS Cut Line= 4
2584365.043909226948356.460245482575629.908492396949815.20076631
 2575330.61348736950088.920035142569904.361872646951081.94626431
#Sta/Elev= 30
       0  440.93  729.68  405.67  849.63  408.36  1809.2   378.6 3836.51  373.92
 6317.19   373.4 6392.15  365.85 6427.14  373.14 8925.31  373.57 8989.61  361.02
 9014.34  373.6710251.08     37610366.01  367.5710415.98  379.76 10555.9  374.07
11185.53  376.7311295.46   377.911378.15  387.3711635.26  394.1612119.98   389.4
12244.91   396.1 12939.5  392.2413524.16  399.3813664.07  404.5713679.07  410.32
13973.89  415.4714048.85  433.3114088.73  432.0614569.37  433.5914778.42  434.41
#Mann= 7 ,-1 , 0
       0     .06       0 3836.51      .1       0 8925.31    .045       0
 9014.34      .1       011378.15     .08       014088.73     .06       0
14569.37     .05       0
#XS Ineff= 1 ,-1
10251.08   10403     376
Permanent Ineff=
       T
Bank Sta=8925.31,9014.34
XS Rating Curve= 0 ,0
Exp/Cntr=0.3,0.1

Type RM Length L Ch R = 1 ,111013  ,1147.2,2502.72,880.03
BEGIN DESCRIPTION:
ROB IFA station 11670: flow contraction due to natural high ground
END DESCRIPTION:
XS GIS Cut Line= 4
2584532.578679136947083.02250364 2575401.21767686948921.02604547
2573626.150032716949085.418433232569828.406972056950930.03646314
#Sta/Elev= 30
       0  442.98  369.98  418.13 1104.94  395.51 2774.84   387.6 3798.84  372.19
 6599.65  373.32 6779.65  367.96 7009.64  373.38 7049.64   366.9 7069.63  373.03
 7169.63   373.6  7829.6   371.9  7849.6  367.54  7954.6   372.7 9484.36  374.12
 9499.34  364.44 9539.29  360.75 9569.25  373.4810283.31  372.2610724.35  379.66
10782.65  395.3210842.57  395.8311327.05  396.5611816.67  387.9612401.21  386.35
12675.99  392.9513860.07  397.0214214.79  406.6114754.99  433.3115318.93  434.95
#Mann= 6 ,-1 , 0
       0     .06       0 3798.84      .1       0 9484.36    .045       0
 9569.25      .1       010724.35     .08       014754.99     .05       0
#XS Ineff= 2 , 0
       0                   11670       0   393.5
Permanent Ineff=
       F       F
Bank Sta=9484.36,9569.25
XS Rating Curve= 0 ,0
Exp/Cntr=0.3,0.1

Type RM Length L Ch R = 1 ,108510  ,780.07,1086.88,881.1
BEGIN DESCRIPTION:
ROB IFA station 10936: flow explansion due to natural high ground upstream
END DESCRIPTION:
XS GIS Cut Line= 5
2584272.161877146945728.855920642576318.948452896947633.00139056
2575962.557761486947873.642313482573290.728459466948352.61084373
2569481.184569396949736.46011014
#Sta/Elev= 30
       0  438.25  659.84  423.86 1174.71  418.75  1224.7   412.6 1324.67  421.41
 1404.65   414.1 2349.42  396.58 3384.16  387.61  3805.4   374.6 4268.93  370.88
 7148.23  372.74 7208.22  366.29  7258.2  372.56 7808.07  368.06 7848.06  372.55
 8301.56   373.3 8321.33  361.95 8350.99  360.11 8380.65  372.5710272.71   374.8
10362.69  370.5813081.65  376.1913496.45  388.1214061.18  428.9714381.02  426.18
14570.93  417.8514590.92  412.3614815.81  427.5414970.74   432.515375.54  434.28
#Mann= 4 ,-1 , 0
       0     .07       0  3805.4      .1       0 8301.56    .045       0
 8380.65      .1       0
#XS Ineff= 2 , 0
       0                   10936       0   390.5
Permanent Ineff=
       F       F
Bank Sta=8301.56,8380.65
XS Rating Curve= 0 ,0
Exp/Cntr=0.3,0.1

Type RM Length L Ch R = 1 ,107423  ,723.84,794.81,530.35
BEGIN DESCRIPTION:
ROB IFA station 9584: flow explansion due to natural high ground upstream
END DESCRIPTION:
XS GIS Cut Line= 3
2582253.932973976945442.397504062573328.649315396947549.52386723
2569383.52826864 6948976.9114324
#Sta/Elev= 30
       0  444.66  239.89  422.17  274.87  425.05  339.84   417.8  709.66  399.98
  1684.2  378.07 1879.11  381.09 1929.09  376.72 2403.57  375.88 2823.66   371.7
 5172.56  371.74 5257.52  363.95 5327.48  372.25 5767.28  368.94 6916.75  373.13
 6946.73  361.71 6976.72  359.89 6996.71  372.8910908.65  373.8911043.49  383.91
 11128.4  378.6111398.09  383.3111443.04  391.9511687.76  408.8311777.66  421.35
11992.42  411.7312112.28     41912277.09  417.2312641.68  429.4613365.85   432.9
#Mann= 4 ,-1 , 0
       0     .07       0 2403.57      .1       0 6916.75    .045       0
 6996.71      .1       0
#XS Ineff= 2 , 0
       0    1600   390.5    9584       0   390.5
Permanent Ineff=
       F       F
Bank Sta=6916.75,6996.71
XS Rating Curve= 0 ,0
Exp/Cntr=0.3,0.1