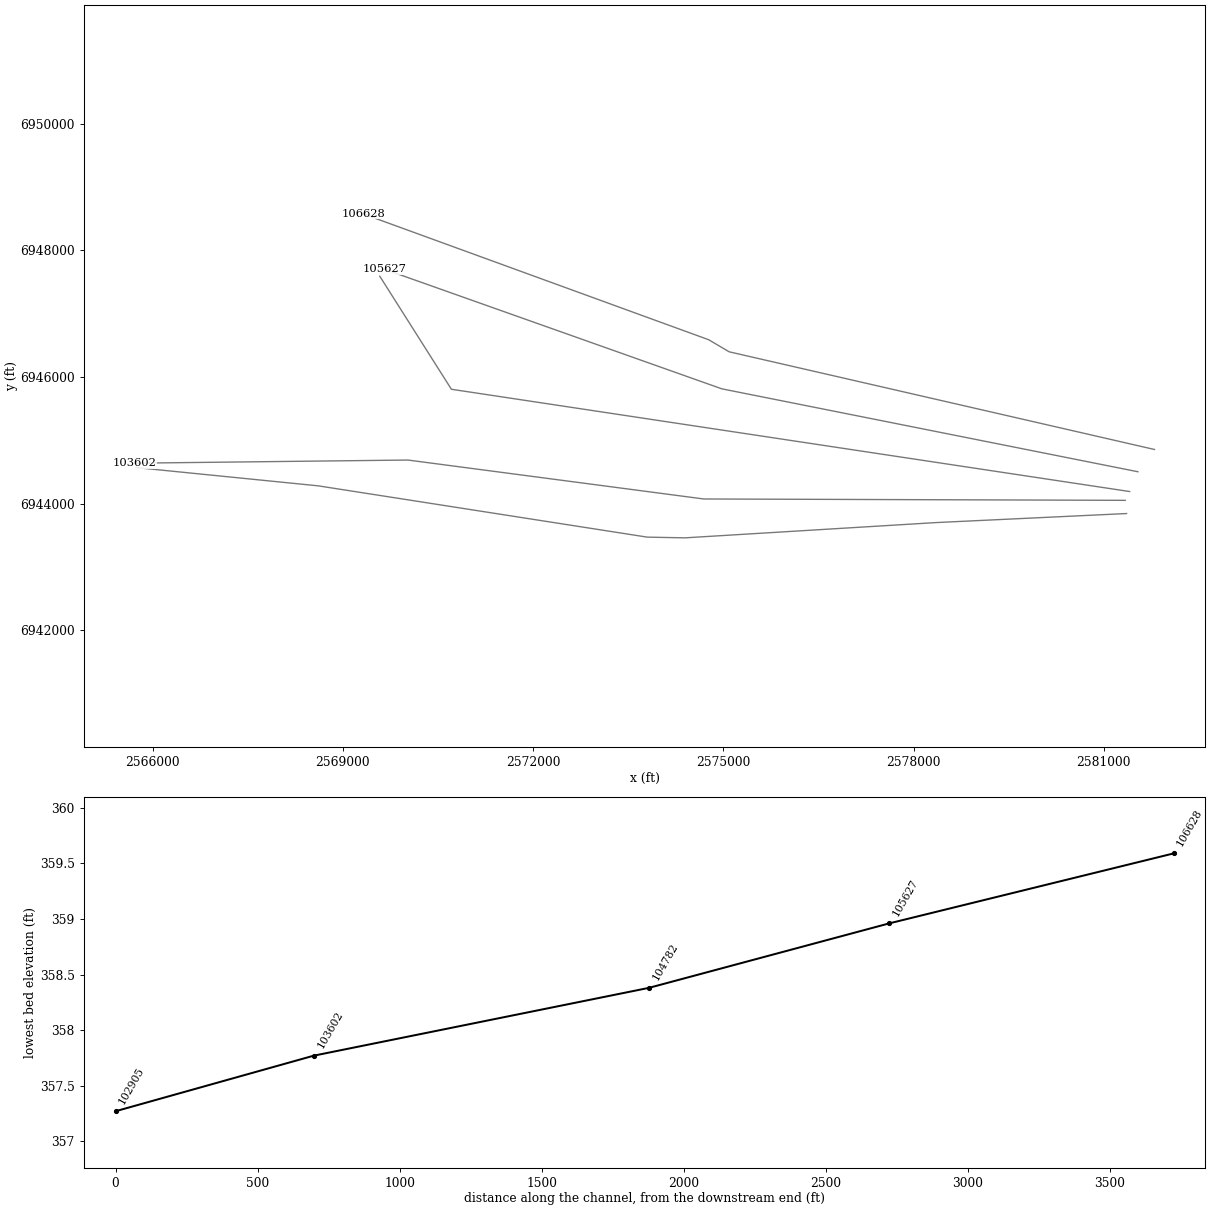
HEC-RAS study EF_FEMA.prj: East_Fork_FEMA

--- EF_FEMA.g06 (geometry) --- (continued)

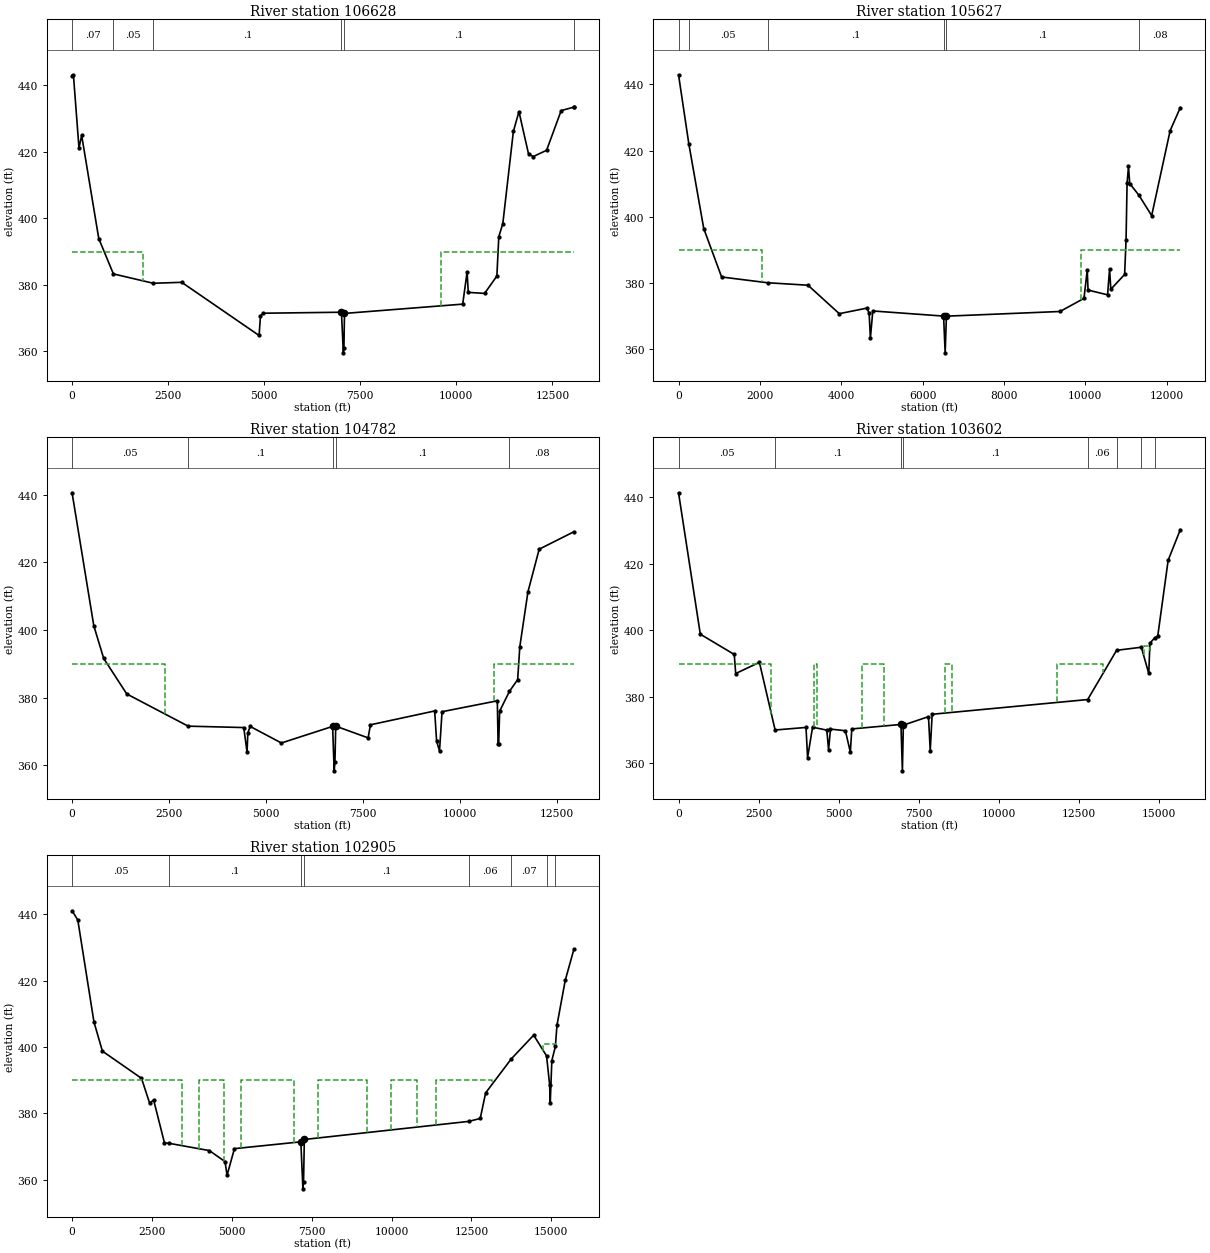
Type RM Length L Ch R = 1 ,106628  ,566.88,1001.58,673.69
BEGIN DESCRIPTION:
ROB IFA station 9608: flow explansion due to natural high ground upstream
END DESCRIPTION:
XS GIS Cut Line= 4
2581798.203570476944856.460027652575092.151037726946398.07472657
2574768.113299976946588.920145392569318.42406814 6948575.4358574
#Sta/Elev= 30
       0  442.89   34.98  443.11  179.89  421.12  249.85  424.89  694.59  393.92
 1075.12   383.3 2112.22  380.49 2853.33  380.77 4867.14   364.8 4902.12  370.69
 4977.07  371.49  7009.6  371.79 7059.08  359.59 7073.93     361 7088.92  371.43
10164.74  374.2210279.65  383.8610309.63  377.75 10734.3  377.4411054.05  382.64
11104.01  394.4611208.93  398.4311483.71   426.1 11628.6  432.05 11878.4   419.3
 12003.3  418.5612348.04  420.4312727.74  432.3613057.23  433.3913057.48  433.39
#Mann= 6 ,-1 , 0
       0     .07       0 1075.12     .05       0 2112.22      .1       0
  7009.6    .045       0 7088.92      .1       013057.23     .08       0
#XS Ineff= 2 , 0
       0    1850     390    9608       0     390
Permanent Ineff=
       F       F
Bank Sta=7009.6,7088.92
XS Rating Curve= 0 ,0
Exp/Cntr=0.3,0.1

Type RM Length L Ch R = 1 ,105627  ,562.95,845.33,938.78
BEGIN DESCRIPTION:
ROB IFA station 9890: flow explansion due to natural high ground upstream
END DESCRIPTION:
XS GIS Cut Line= 3
2581537.787096566944504.89773865 2574975.97640136945813.66283764
2569653.529697146947701.95499282
#Sta/Elev= 30
       0  442.89  253.79  421.98  619.63  396.48 1059.37  381.85 2187.68  380.12
 3183.12  379.37 3952.66  370.78 4632.25  372.46 4687.22  370.95  4717.2  363.37
 4777.17   371.6 6517.48  370.05  6556.1  358.96 6587.04  370.03  9379.9  371.44
 9969.67   375.410049.64  383.9610069.63   377.910549.44  376.4710599.42  384.27
10629.41  378.1410969.28  382.6211004.26  393.0511029.25  410.1211064.24  415.21
11094.23  410.0711320.61  406.5311634.02  400.3812088.84  426.0512338.74  432.99
#Mann= 6 ,-1 , 0
       0     .07       0  253.79     .05       0 2187.68      .1       0
 6517.48    .045       0 6587.04      .1       011320.61     .08       0
#XS Ineff= 2 , 0
       0    2060     390    9890       0     390
Permanent Ineff=
       F       F
Bank Sta=6517.48,6587.04
XS Rating Curve= 0 ,0
Exp/Cntr=0.3,0.1

Type RM Length L Ch R = 1 ,104782  ,862.01,1179.17,1206.85
BEGIN DESCRIPTION:
ROB IFA station 10872: flow explansion due to natural high ground upstream
END DESCRIPTION:
XS GIS Cut Line= 3
2581407.578695556944192.39770748 2570711.40028486945806.84493789
2569581.915339056947591.27772073
#Sta/Elev= 30
       0  440.53  559.86  401.25   814.8  391.59 1409.65  381.09 2991.21  371.58
 4423.88  371.17 4508.86   363.9 4528.86  369.59 4588.85   371.5 5393.66  366.61
 6713.35  371.51 6753.34  358.38 6773.34  360.97 6793.33  371.59 7628.14  368.12
 7688.13  371.98 9342.78  376.07 9392.77  367.17 9467.76  364.26 9532.74  375.85
10957.27  379.0710977.24  366.1710992.22  366.4511017.18  376.0111269.36  381.86
11481.46  385.3411536.37  395.0411746.05  411.26 12035.6  423.8612929.21  429.01
#Mann= 5 ,-1 , 0
       0     .05       0 2991.21      .1       0 6713.35    .045       0
 6793.33      .1       011269.36     .08       0
#XS Ineff= 2 , 0
       0    2400     390   10872       0     390
Permanent Ineff=
       F       F
Bank Sta=6713.35,6793.33
XS Rating Curve= 0 ,0
Exp/Cntr=0.3,0.1

Type RM Length L Ch R = 1 ,103602  ,491.43,697.56,687.23
XS GIS Cut Line= 4
2581338.134280646944053.508549562574691.724345136944075.03114431
2570026.547323816944689.645072562565718.344654146944640.17830798
#Sta/Elev= 30
       0  441.38  679.64  398.86 1739.07  392.76 1784.05  387.03 2523.65   390.4
 3014.39  370.05 3977.86  370.82 4027.83  361.74 4182.75   370.9 4627.52  370.01
 4682.49  364.11 4742.46  370.32 5207.23  369.83 5362.15  363.39 5407.13  370.37
 6941.21  371.72 6986.16  357.77 7016.13  371.51 7800.37  374.07 7855.31  363.88
 7915.26  374.7812769.61  379.2113671.06  394.01 14443.2  394.94 14675.6  387.04
14710.58  396.17 14855.6   397.714955.49   398.315280.36  421.0915660.21   430.3
#Mann= 8 ,-1 , 0
       0     .05       0 3014.39      .1       0 6941.21    .045       0
 7016.13      .1       012769.61     .06       013671.06     .07       0
 14443.2      .1       0 14855.6     .06       0
#XS Ineff= 6 ,-1
       0    2900     390 4213.59  4331.1     390 5717.27 6426.55     390
 8328.54 8538.55     39011818.01   13255     390   14511   14702   395.2
Permanent Ineff=
       F       F       F       F       F       F
Bank Sta=6941.21,7016.13
XS Rating Curve= 0 ,0
Exp/Cntr=0.5,0.3

Type RM Length L Ch R = 1 ,102905  ,527.41,553.15,508.18
BEGIN DESCRIPTION:
US Bridge
END DESCRIPTION:
XS GIS Cut Line= 6
 2581358.96757236943845.175304822578354.728502056943702.54665306
2574397.366338066943461.575350232573800.467925556943472.64192915
2568610.761769556944282.465440722565739.177945816944570.73389307
#Sta/Elev= 30
       0  441.09  179.86   438.3  684.46   407.6  949.25  398.78 2173.28  390.59
 2428.08  383.09 2552.98  384.05 2892.71  371.11 3038.95  370.99 4297.52   368.8
 4787.47  365.49 4852.46  361.37 5082.44  369.39 7161.31  371.44 7225.99  357.27
 7245.89  359.26 7270.76  372.1512416.83   377.612776.88  378.4812946.69   386.2
 13747.8  396.4314449.63   403.614853.04  397.3514948.95  388.7114968.92  383.26
15018.85  395.9415129.72  400.2115178.63  406.5615438.28  420.1415707.91  429.44
#Mann= 8 ,-1 , 0
       0     .05       0 3038.95      .1       0 7161.31    .045       0
 7270.76      .1       012416.83     .06       0 13747.8     .07       0
14853.04      .1       015129.72     .06       0
#XS Ineff= 7 ,-1
       0    3447     390    3972    4752     390    5279    6934     390
    7698    9248     390    9976   10806     390   11395   13150     390
   14749   15140   400.9
Permanent Ineff=
       F       F       F       F       F       F       F
Bank Sta=7161.31,7270.76
XS Rating Curve= 0 ,0
Exp/Cntr=0.5,0.3