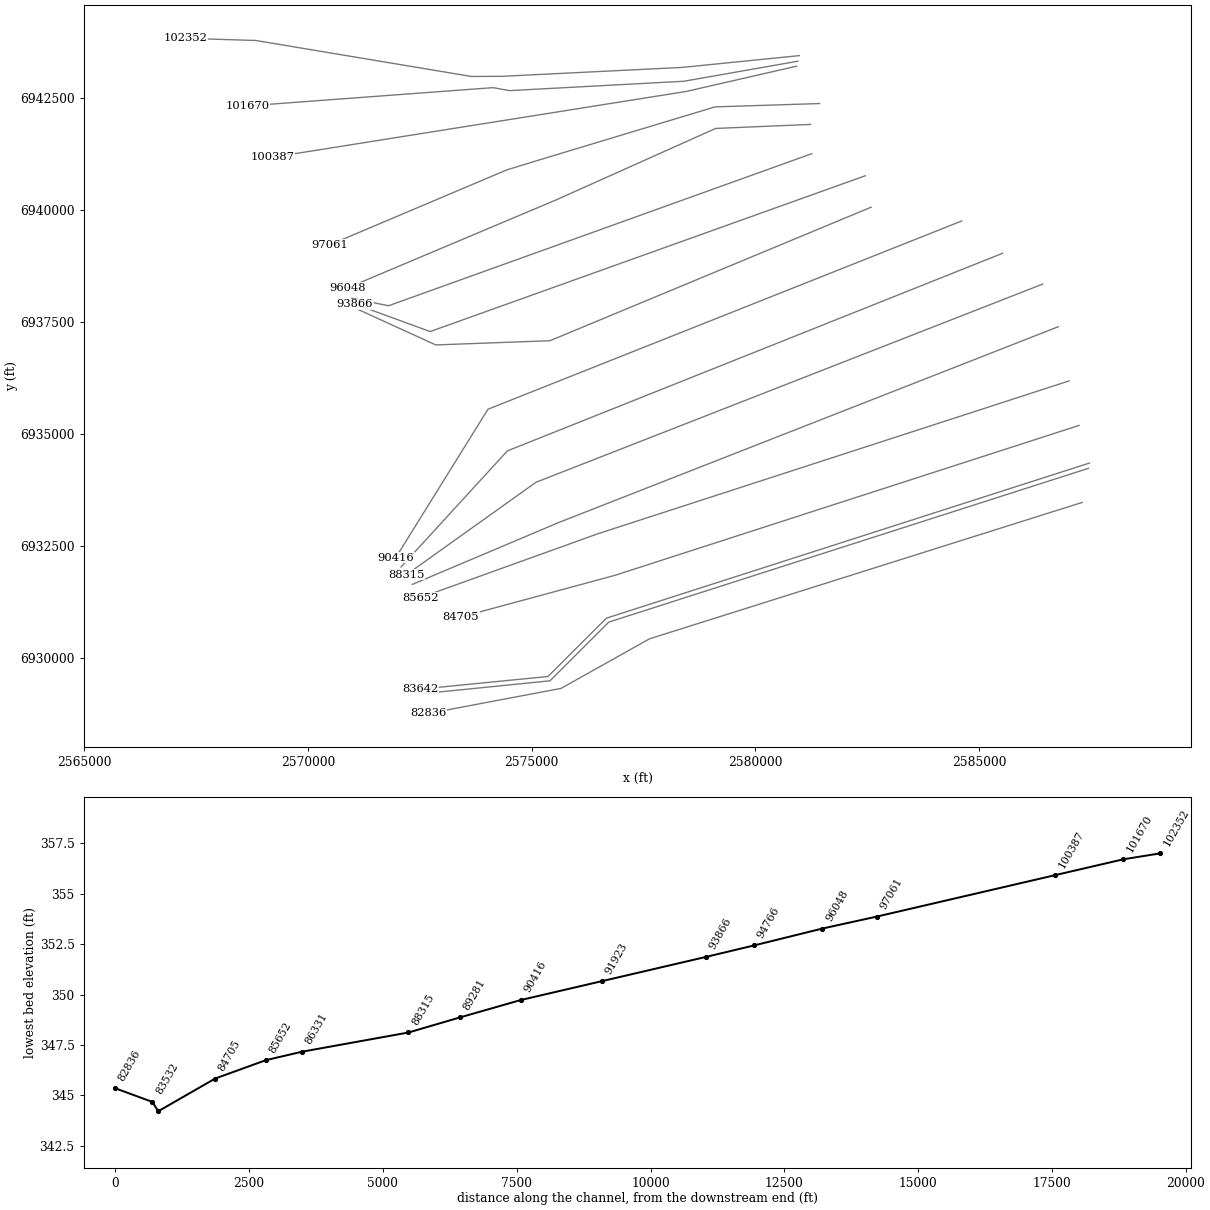
HEC-RAS study EF_FEMA.prj: East_Fork_FEMA

--- EF_FEMA.g06 (geometry) --- (continued)

Type RM Length L Ch R = 4 ,102582  ,,,
BEGIN DESCRIPTION:
IH 20 - Bridge geometry per as-built plans with work accepted date of 2/1/89 .  Road deck in overbanks per Lidar data.
END DESCRIPTION:
Node Name=IH 20
Bridge Culvert--1,0,-1,-1, 0
Deck Dist Width WeirC Skew NumUp NumDn MinLoCord MaxHiCord MaxSubmerge Is_Ogee
178,166,2.6,0, 78, 76, , , 0.98, 0, 0,0,,
       0     189 293.681 388.392 493.072 592.768 692.464 792.159 891.855 991.551
1190.9431390.432 1590.381790.3281990.2762190.2252390.1732590.1212790.0692990.018
3189.9663389.9143544.874    3576    3576    3896    38964159.7154354.6654499.627
4654.5874809.547    4839    51695174.4535329.4125334.411 5569.356029.2316409.133
6819.0276943.995  6959.6  6960.1  6975.1    7579    75797587.413  7590.9  7591.2
8135.0068689.7589069.589 9334.47    9359    98199839.24510370.5410946.81   11002
   1121211246.6811636.5111971.3612461.1412960.9213315.8113830.6514225.5214590.41
14885.32   14932   14933   15431   1543215485.1315825.0215850.91
     420  417.34 415.523 413.975 412.291 410.865 409.592 408.417 407.141 405.939
 403.497 400.987 398.291 395.575 392.821 390.944  389.38 388.662 387.764 387.094
 386.898 386.893 386.614 386.614 386.614 386.805 386.805 386.606  386.18 386.669
 386.533 386.648 386.648 386.796 386.796  386.64 386.621 387.023 388.354 388.495
 388.839 389.357     390     393     393   393.5   393.5   393.5   393.5   390.8
 386.705 383.651 385.737 386.412 386.412 386.372 386.372 384.669 386.493 386.493
 386.538 386.538 385.633  383.93 386.492 389.748 396.844 409.477 417.894  422.66
 424.759 424.759 424.759 424.759 424.195 424.195  425.41  426.29
                                   381.4   381.2
                   381.1   381.1
                                   384.7   385.4
                                  381.15 380.872                         380.993
 381.038
 -21.319  73.392 178.072 277.768 377.464 477.159 576.855 676.551 875.9431075.432
 1275.381475.3281675.2761875.2252075.1732275.1212475.0692675.0182874.9663074.914
3229.874    3261    3261    3581    35813844.7154039.6654184.6274339.5874494.547
    4524    48544859.4535014.4125019.411 5254.355714.2316094.1336504.0276628.995
  6644.6  6645.1  6660.1    7264    72647272.413  7275.9  7276.27820.0068374.758
8754.589 9019.47    9044    95049524.245 9984.0410488.81   10544   1075410788.68
11178.5111513.3612003.1412502.9212857.8113372.6513767.5214132.4114427.32   14474
   14475   14973   1497415027.1315367.02   15482
 415.523 413.975 412.291 410.865 409.592 408.417 407.141 405.939 403.497 400.987
 398.291 395.575 392.821 390.944  389.38 388.662 387.764 387.094 386.898 386.893
 386.614 386.614 386.614 386.805 386.805 386.606  386.18 386.669 386.533 386.648
 386.648 386.796 386.796  386.64 386.621 387.023 388.354 388.495 388.839 389.357
     390     393     393   393.5   393.5   393.5   393.5   390.8 386.705 383.651
 385.737 386.412 386.412 386.372 386.372 384.669 386.493 386.493 386.538 386.538
 385.633  383.93 386.492 389.748 396.844 409.477 417.894  422.66 424.759 424.759
 424.759 424.759 424.195 424.195  425.41  426.29
                   381.4   381.2
   381.1   381.1
                   384.7   385.4
                  381.15 380.872                         380.993 381.038
Pier Skew, UpSta & Num, DnSta & Num=  ,3656.01, 2 ,3341.01, 2 , 0 , 0 , 0 ,,
       2       2
       0     390
       2       2
       0     390
Pier Skew, UpSta & Num, DnSta & Num=  ,3736.01, 2 ,3421.01, 2 , 0 , 0 , 0 ,,
       2       2
       0     390
       2       2
       0     390
Pier Skew, UpSta & Num, DnSta & Num=  ,3816.01, 2 ,3501.01, 2 , 0 , 0 , 0 ,,
       2       2
       0     390
       2       2
       0     390
Pier Skew, UpSta & Num, DnSta & Num=  ,4935.01, 2 ,4620.01, 2 , 0 , 0 , 0 ,,
       2       2
       0     390
       2       2
       0     390
Pier Skew, UpSta & Num, DnSta & Num=  ,5015.01, 2 ,4700.01, 2 , 0 , 0 , 0 ,,
       2       2
       0     390
       2       2
       0     390
Pier Skew, UpSta & Num, DnSta & Num=  ,5095.01, 2 ,4780.01, 2 , 0 , 0 , 0 ,,
       2       2
       0     390
       2       2
       0     390
Pier Skew, UpSta & Num, DnSta & Num=  ,7076.2, 2 ,6761.2, 2 , 0 , 0 , 0 ,,
       4       4
       0     390
       4       4
       0     390
Pier Skew, UpSta & Num, DnSta & Num=  ,7176.2, 2 ,6861.2, 2 , 0 , 0 , 0 ,,
       4       4
       0     390
       4       4
       0     390
Pier Skew, UpSta & Num, DnSta & Num=  ,7276.2, 2 ,6961.2, 2 , 0 , 0 , 0 ,,
       4       4
       0     390
       4       4
       0     390
Pier Skew, UpSta & Num, DnSta & Num=  ,7376.2, 2 ,7061.2, 2 , 0 , 0 , 0 ,,
       4       4
       0     390
       4       4
       0     390
Pier Skew, UpSta & Num, DnSta & Num=  ,7477.61, 2 ,7162.61, 2 , 0 , 0 , 0 ,,
       4       4
       0     390
       4       4
       0     390
Pier Skew, UpSta & Num, DnSta & Num=  ,9439.1, 2 ,9124.1, 2 , 0 , 0 , 0 ,,
       2       2
       0     390
       2       2
       0     390
Pier Skew, UpSta & Num, DnSta & Num=  ,9519.1, 2 ,9204.1, 2 , 0 , 0 , 0 ,,
       2       2
       0     390
       2       2
       0     390
Pier Skew, UpSta & Num, DnSta & Num=  ,9599.1, 2 ,9284.1, 2 , 0 , 0 , 0 ,,
       2       2
       0     390
       2       2
       0     390
Pier Skew, UpSta & Num, DnSta & Num=  ,9679.1, 2 ,9364.1, 2 , 0 , 0 , 0 ,,
       2       2
       0     390
       2       2
       0     390
Pier Skew, UpSta & Num, DnSta & Num=  ,9759.1, 2 ,9444.1, 2 , 0 , 0 , 0 ,,
       2       2
       0     390
       2       2
       0     390
Pier Skew, UpSta & Num, DnSta & Num=  ,11072, 2 ,10614, 2 , 0 , 0 , 0 ,,
       2       2
       0     390
       2       2
       0     390
Pier Skew, UpSta & Num, DnSta & Num=  ,11142, 2 ,10684, 2 , 0 , 0 , 0 ,,
       2       2
       0     390
       2       2
       0     390
Abutment Skew #Up #Dn= , 2 , 2
    3576  3618.8
   381.4     360
    3261  3303.8
   381.4     360
Abutment Skew #Up #Dn= , 2 , 2
3852.831    3896
     360   381.2
3537.831    3581
     360   381.2
Abutment Skew #Up #Dn= , 2 , 2
    4839  4889.2
   381.1     356
    4524  4574.2
   381.1     356
Abutment Skew #Up #Dn= , 2 , 2
5122.439    5169
     356   381.1
 4806.66    4854
     356   381.1
Abutment Skew #Up #Dn= , 2 , 2
  6975.1 7019.57
   384.7     362
  6660.1 6704.57
   384.7     362
Abutment Skew #Up #Dn= , 2 , 2
7528.558    7579
     362 385.359
7213.558    7264
     362 385.359
Abutment Skew #Up #Dn= , 2 , 2
    93599395.256
  381.15     363
    90449080.256
  381.15     363
Abutment Skew #Up #Dn= , 2 , 2
9782.427    9819
     363  380.87
9467.427    9504
     363  380.87
BR Coef=-1 , 0 , 0 ,, 0 ,,,0.8,-1,,0,
WSPro=,,,, 1 ,,,, 0 ,,,, 0 ,,,,-1 ,-1 ,-1 , 0 , 0 , 0 , 0 , 0
BC Mult= 3 ,0,4752,0,4345
BC Mult= 3 ,3972,6934,3611,6498
BC Mult= 3 ,5279,9248,4862,8966
BC Mult= 3 ,7698,10806,7326,10423
BC Mult= 3 ,9976,15707.91,9562,13802.55
BR U #Sta/Elev= 490
       0  441.09   54.96  441.29   99.92   441.1   124.9  440.07  144.89  439.76
  179.86   438.3  209.83  436.68  229.82  435.94  269.79  433.96  299.76  431.95
  309.76  431.73  354.72  428.62  369.71  428.28  389.69  426.96  394.69  427.16
  409.68  425.63  444.65  423.63   504.6  419.38  554.56  415.48  624.51  411.47
  644.49  410.88  684.46   407.6  714.44  406.13  739.42  405.67  769.39  403.54
  849.33  401.09  949.25  398.78  989.22   398.4 1034.18  397.42 1074.15  396.93
  1144.1  395.79 1164.08  395.89 1219.04   395.4 1348.93  394.56 1398.89  394.34
 1413.88  393.99 1433.87  394.19 1583.75  393.44  1648.7  392.99 1733.63  392.17
 1743.62     392  1773.6     392 1793.58     391 1803.57     391 1848.54     390
 1868.52  389.71 1888.51  389.71  1898.5  389.71 1928.47  389.71 1998.42     388
 2008.41     388 2033.39     388 2073.36     387 2128.32     387 2173.28     387
 2263.21     386 2338.15   385.6 2368.13  385.52 2388.11  384.43 2428.08  383.09
 2458.06  383.87 2468.05  383.56 2488.03  384.54 2523.01  384.54 2552.98  384.05
 2637.91  380.67 2667.89  379.13 2712.86  377.24 2737.84  376.65 2747.83  375.98
 2792.79  374.83 2837.76  373.15 2862.74  371.85 2877.73  372.17 2892.71  371.11
  2907.7  371.84 2922.69  371.12 2937.68  371.54 2947.67  370.87 2957.66  371.54
 2992.63  371.18 3038.95  370.99 3097.62  370.99 3117.61  371.21 3132.61  370.42
 3182.61  370.88 3197.61  370.53  3247.6  370.63  3292.6  370.07  3322.6  370.49
 3407.59  369.97 3417.59  370.49 3477.59  370.15 3507.58  370.31 3547.58  370.06
 3567.58  369.28 3577.58  369.98 3597.58  369.55 3637.57  369.43 3657.57  369.84
 3707.57  369.41 3722.57  369.56 3752.57  368.78 3797.56  368.98 3812.56  369.32
 3872.56  368.31 3887.56  368.37 3937.55  369.26 3972.55  369.01 4007.55  369.32
 4052.54  369.39 4097.54  368.78 4112.54  369.19 4162.53  368.78 4197.53  369.18
 4237.52  368.48 4252.52   368.8 4267.52  368.37 4297.52   368.8 4322.52  368.02
 4332.52  368.12 4362.51  367.26 4372.51  367.53 4402.51  366.91 4417.51  367.17
 4432.51  366.68  4452.5  367.35  4477.5  366.55  4502.5  366.87  4527.5  366.48
  4542.5  366.95 4562.49  365.89 4592.49  366.22 4602.49  365.93 4632.49  366.52
 4652.48  366.36 4672.48   365.1 4682.48   366.1 4707.48   365.3 4717.48  365.88
 4757.47  365.11 4787.47  365.49 4802.47  364.81 4812.47  363.46 4832.47  363.19
 4852.46  361.37 4872.46  361.66 4892.46  362.93 4907.46  361.74 4927.46   361.5
 4942.46  364.69 4952.46  365.17 4972.45  368.15 4992.45   367.8 4997.45   368.3
 5032.45  368.71 5047.45  367.38 5057.44  368.82 5082.44  369.39 5117.44  368.79
 5142.44  369.39 5162.43  368.22 5192.43  368.72 5237.43  368.77 5247.43  368.08
 5307.42  369.32 5347.42   368.4 5357.42  367.48 5377.41  367.94 5382.41  367.26
 5427.41   368.8 5442.41  368.99  5467.4  368.63  5477.4  369.29  5497.4  369.09
  5512.4  370.27  5547.4  369.82  5567.4  370.26 5592.39   369.7 5647.39  370.05
 5672.38  369.36 5687.38  370.26 5727.38  370.14 5742.38  370.34 5767.38  369.82
 5832.37  370.53 5842.37  369.93 5862.37   370.6 5887.36  368.71 5897.36  369.39
 5917.36   368.9 5927.36  369.75 5957.36  370.38 6012.35  370.71 6042.35  370.69
 6062.35  370.13 6072.35  369.02 6082.34  369.23 6127.34  368.33 6147.34  369.58
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BR U #Mann= 8
       0     .05 3038.95      .1 7161.31     .04 7270.76      .112416.83     .06
 13747.8     .0714853.04      .115129.72     .06
BR D #Sta/Elev= 490
       0  434.22       5  434.44      35   433.9      85   432.1     125  429.64
     170  426.04     225  421.33     290  417.17     315  415.19     350  412.93
     380   410.5     400  409.79     420  407.29     445  405.41     475   404.3
     510  403.62     535  402.19     595  400.27     630  399.35     730  397.46
  824.99  396.22  864.99  395.91  929.99  395.56 1064.99   395.1 1234.99  394.16
 1439.99  394.13 1494.99  394.16 1559.99  394.31 1614.99   394.6 1709.99     393
 1714.99     392 1824.99     391 1849.99     391 1854.99     391 1869.99   390.7
 1879.99  390.65 1894.99  389.35 1904.99  389.18 1919.99  389.58 1934.99  388.84
 1959.99  386.98 2009.99  383.95 2074.99  381.19 2089.99  380.42 2099.99   378.6
 2114.99  377.41 2129.99  377.17 2144.99  377.73 2154.99  378.54 2159.99  380.26
 2169.99  380.83 2174.99  381.84 2184.99   382.7 2199.99  380.81  2203.3  379.55
 2214.99  375.05 2229.99   373.2 2239.99  372.56 2249.99  372.79 2284.99  372.14
 2314.99  371.75 2324.99  371.94 2374.99  372.08 2429.99  371.54 2439.99  371.88
 2454.99  371.84 2464.99  371.29 2479.99  371.61 2489.99  371.28 2504.99  371.66
 2549.99  371.53 2609.99  371.79 2634.99  371.62 2654.97  371.27 2664.97   371.7
 2709.94  371.69 2724.93   371.3 2734.92  371.47 2754.91  372.49  2769.9  372.22
 2794.89  370.65 2804.88  370.24 2829.86  370.06 2844.86   369.5 2884.83  370.25
 2924.81   370.7 2964.78  370.82 3034.74   370.2 3069.71   370.7 3119.68  370.79
 3209.63  370.79 3234.61  370.67  3259.6  370.33 3289.58  370.74 3314.56  370.21
 3339.55  370.25 3354.54  369.57 3369.53  370.27 3394.51   369.2  3409.5  370.48
 3429.49  370.42 3509.44  370.66 3594.39  370.55 3689.33  370.93  3739.3  370.85
 3789.26  370.62 3854.22  370.44 3864.22  370.59 3914.19  370.27 3949.16  370.66
 3994.14  370.48 4024.12  370.64 4039.11  369.67  4049.1  370.18 4064.09  369.87
 4094.07  369.98 4109.06  370.23 4119.06  369.91 4134.05  370.31 4154.04  370.32
 4174.03  369.95 4199.01  370.43 4238.99  370.37 4273.97  370.44 4358.92  370.44
  4388.9  370.61 4458.86  370.57 4483.85  370.42 4548.81  370.78 4583.79  370.34
 4608.77  370.17 4668.74  370.18 4673.73  370.04 4678.73  368.59 4693.72  362.91
 4698.72  362.07 4713.71  362.59  4723.7  362.41 4743.69   365.1 4758.68  366.02
 4773.68   365.2 4783.67  363.05 4788.67  361.53 4793.66  361.04 4808.65  362.01
 4823.65  361.08 4833.64  361.67 4848.63  363.48 4858.63  363.38 4868.62  366.19
 4878.61  363.09 4888.61  362.23  4898.6  360.64  4908.6  360.65 4918.59  361.42
 4933.58  361.35 4953.57  362.38 4963.56  364.67 4968.56  366.45 4973.56  367.17
 4983.55  367.28 4993.55  368.69 5008.54  369.81 5018.53   369.7 5028.53   368.9
  5068.5  370.46 5088.49  369.28 5098.48  369.68 5128.47  368.55 5153.45  369.29
 5168.44  368.89 5183.44  368.11 5198.43  366.77 5208.42  365.46 5223.41  366.63
 5228.41   366.2  5238.4  361.88  5243.4  360.35 5263.39  360.08 5278.38  360.45
 5288.37  362.16 5298.37  365.65 5313.36  368.97 5328.35  369.66 5338.34  369.04
 5373.32  369.69 5398.31  368.43  5408.3  368.26 5423.29  368.78 5453.28   369.1
 5488.26  369.14 5503.25  368.54 5528.23  368.77 5548.22  369.42 5558.22   369.5
  5588.2  369.04 5638.17  368.82 5663.15   369.1 5673.15  368.67 5693.14  368.96
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BR D #Mann= 6
       0     .05  2203.3      .1 7002.25     .04 7087.17      .110699.94     .06
13748.46     .07
BC Design=,, 0 ,, 0 ,,,,,,
BC Use User HTab Curves=0
BC User HTab FreeFlow(D)= 0

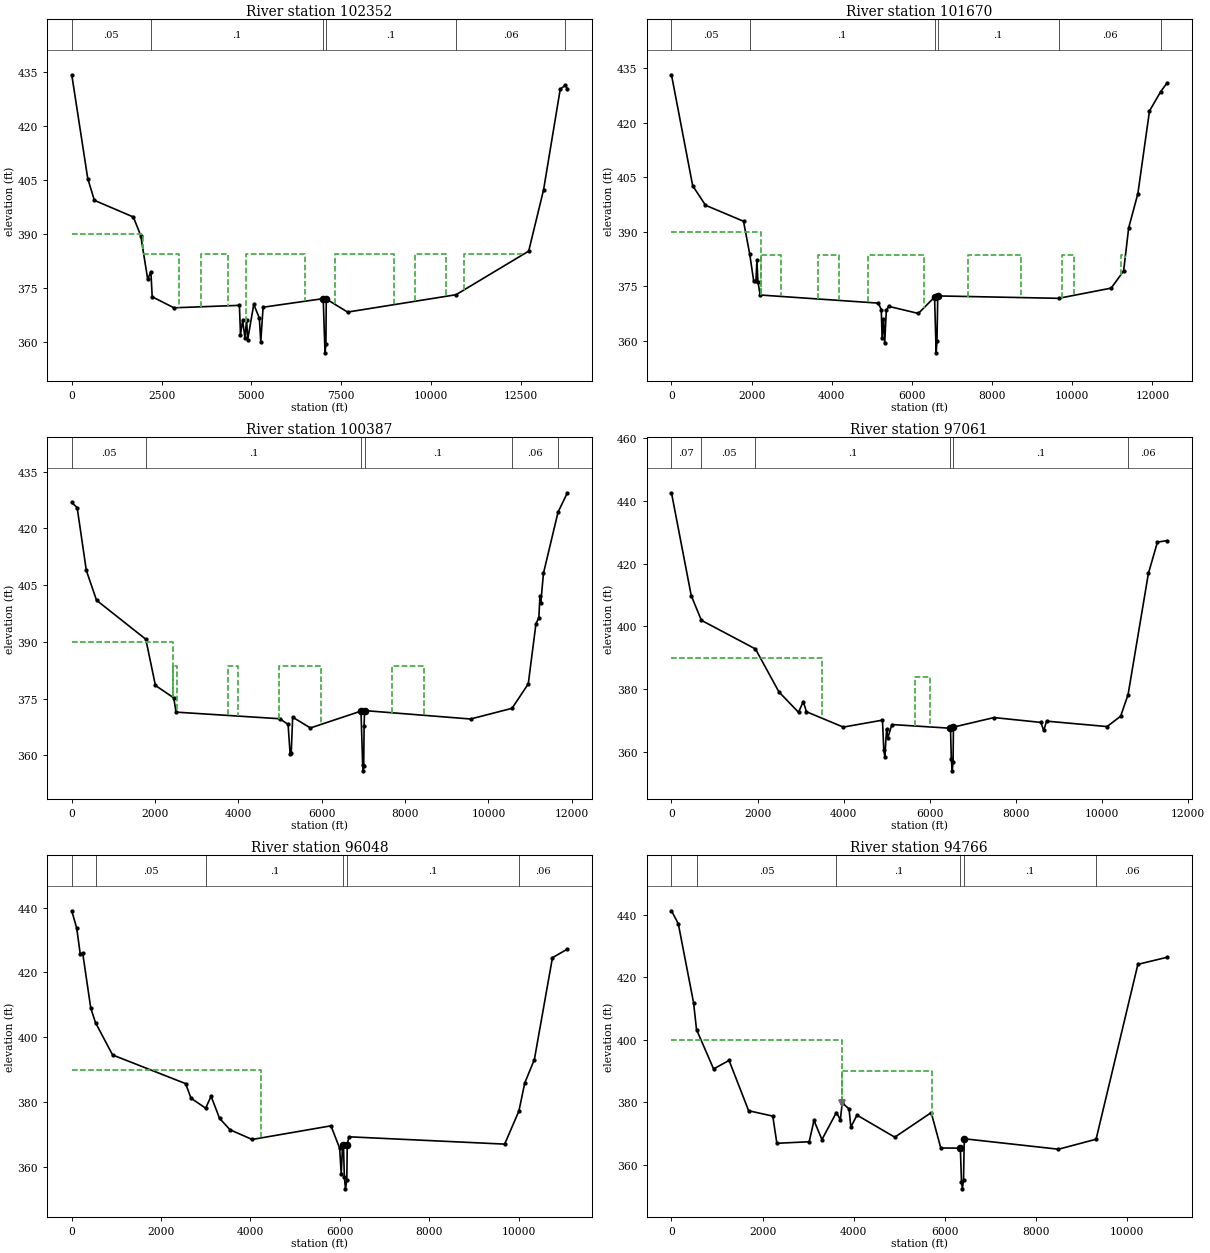
Type RM Length L Ch R = 1 ,102352  ,319.23,682.06,550.14
BEGIN DESCRIPTION:
DS Bridge
LOB IFA station 1982: flow contraction due to natural high ground downstream
END DESCRIPTION:
XS GIS Cut Line= 6
2580983.967666136943435.45302714 2578362.20388086943171.81149407
 2574339.58987886942973.46477789 2573655.24282236942969.93722589
2568833.675365726943772.952680232567266.955730146943820.73375264
#Sta/Elev= 30
       0  434.22     445  405.41     630  399.35 1714.99  394.72 1919.99  389.58
 2114.99  377.41  2203.3  379.55 2239.99  372.56 2844.86   369.5 4668.74  370.18
 4698.72  362.07 4758.68  366.02 4823.65  361.08 4868.62  366.19  4898.6  360.64
  5068.5  370.46 5223.41  366.63 5263.39  360.08 5328.35  369.66 7002.25  372.05
 7052.21  356.99 7077.18  359.31 7087.17  371.94 7681.79  368.3110699.94  373.13
12724.24  385.2413138.59  402.2513602.86  430.2213748.46  431.3413802.55  430.25
#Mann= 6 ,-1 , 0
       0     .05       0  2203.3      .1       0 7002.25    .045       0
 7087.17      .1       010699.94     .06       013748.46     .07       0
#XS Ineff= 7 ,-1
       0    1982     390    1982    2990   384.5    3611    4345   384.5
    4862    6498   384.5    7326    8966   384.5    9562   10423   384.5
   10917   12610   384.5
Permanent Ineff=
       F       F       F       F       F       F       F
Bank Sta=7002.25,7087.17
XS Rating Curve= 0 ,0
Exp/Cntr=0.5,0.3

Type RM Length L Ch R = 1 ,101670  ,446.89,1282.17,914.48
BEGIN DESCRIPTION:
LOB IFA station 2229: flow contraction due to natural high ground downstream
END DESCRIPTION:
XS GIS Cut Line= 5
2580949.245294636943310.453277142578401.54730605 6942863.2560088
2574504.449457216942654.170468972574136.16902581 6942720.8645613
2568648.900144736942313.78925999
#Sta/Elev= 30
       0  433.15  529.31  402.65   848.9  397.28 1797.68  392.88 1953.35  383.79
 2052.35  376.36 2107.28  376.41 2132.24   382.1 2157.21  376.28 2212.14   372.6
 5160.17  370.37 5235.13  368.61 5255.12   360.8  5290.1  366.03 5320.08  359.29
 5360.06  368.39 5420.03  369.48 6159.61  367.53 6564.27  372.02 6604.19   356.7
 6624.16  359.89 6644.12  372.35 9660.11  371.6910971.91   374.511281.79  379.24
11406.74  391.0311636.65  400.4711926.53   423.212206.48  428.5212366.35  430.92
#Mann= 6 ,-1 , 0
       0     .05       0 1953.35      .1       0 6564.27    .045       0
 6644.12      .1       0 9660.11     .06       012206.48     .07       0
#XS Ineff= 7 ,-1
       0    2229     390    2229    2726  383.65 3662.55 4173.34  383.65
 4895.82 6291.98  383.65 7406.01 8711.49  383.65 9731.3310054.83  383.65
11215.83   11320  383.65
Permanent Ineff=
       F       F       F       F       F       F       F
Bank Sta=6564.27,6644.12
XS Rating Curve= 0 ,0
Exp/Cntr=0.3,0.1

Type RM Length L Ch R = 1 ,100387  ,809.32,3326.36,1425.52
BEGIN DESCRIPTION:
LOB IFA station 2434: flow contraction due to natural high ground downstream
END DESCRIPTION:
XS GIS Cut Line= 3
2580921.46746305 6943199.34195082578457.36215505 6942636.3985229
2569204.455792136941167.95592172
#Sta/Elev= 30
       0  426.85  129.88  425.47  349.67  408.88  594.43     401 1777.46  390.69
 2008.09  378.48 2447.66   375.2 2502.61  371.43 4992.26  369.68 5192.23  368.17
 5242.22  360.23 5267.22   360.5 5302.21   370.1 5727.16  367.24 6941.99   371.7
 6981.98  357.47 6996.98  355.91 7006.98  357.29 7016.98  367.83 7026.98  371.84
 9571.54  369.6110567.06  372.4410956.27  378.8811141.24  394.7811211.22  396.44
11236.22  402.0411256.21  400.17 11321.2  408.1311671.76  424.3111896.09  429.41
#Mann= 6 ,-1 , 0
       0     .05       0 1777.46      .1       0 6941.99    .045       0
 7026.98      .1       010567.06     .06       011671.76     .07       0
#XS Ineff= 5 ,-1
       0    2434     390    2434    2530  383.65 3740.32 3989.82  383.65
 4982.72 5970.95  383.65 7689.68 8447.44  383.65
Permanent Ineff=
       F       F       F       F       F
Bank Sta=6941.99,7026.98
XS Rating Curve= 0 ,0
Exp/Cntr=0.3,0.1

Type RM Length L Ch R = 1 ,97061   ,780.29,1013.3,1063.03
BEGIN DESCRIPTION:
LOB IFA station 3502: flow contraction due to natural high ground downstream
END DESCRIPTION:
XS GIS Cut Line= 5
2581435.356527136942366.008643732579101.332979986942291.91233523
2575358.390990816941165.308945392574448.669056976940887.53128573
2570475.289208476939209.62289615
#Sta/Elev= 30
       0   442.6  459.06  409.77  694.45   401.9 1950.15  392.76 2495.16  379.05
 2950.02  372.55 3059.99  375.95 3134.97  372.71 3989.71  367.82 4899.44  370.04
 4929.43  360.63 4954.42  358.36 4994.41  367.18  5019.4  364.28 5119.37  368.63
 6478.51  367.46 6498.01  357.59 6517.93  353.86 6537.85  356.58 6547.81  367.82
 7490.07  370.86 8574.61  369.32 8644.58  366.75 8709.56  369.7210114.01  367.99
10428.89  371.2910602.39  378.2111073.64  416.8511283.55  426.8511508.47  427.34
#Mann= 6 ,-1 , 0
       0     .07       0  694.45     .05       0 1950.15      .1       0
 6478.51    .045       0 6547.81      .1       010602.39     .06       0
#XS Ineff= 2 ,-1
       0    3502     390 5664.75 5998.24  383.65
Permanent Ineff=
       F       F
Bank Sta=6478.51,6547.81
XS Rating Curve= 0 ,0
Exp/Cntr=0.3,0.1

Type RM Length L Ch R = 1 ,96048   ,1090.05,1281.61,847.13
BEGIN DESCRIPTION:
LOB IFA station 4227: flow contraction due to natural high ground downstream
END DESCRIPTION:
XS GIS Cut Line= 4
2581233.967494226941900.731030972579112.051134396941810.50188072
 2575562.78231436940223.360698062570878.066946226938251.28951098
#Sta/Elev= 30
       0  439.01  109.94   433.7   189.9  425.69  244.87  425.94  424.77  409.05
   531.7   404.5   914.5  394.55 2548.61  385.71 2668.55  381.23 2997.16  378.14
 3118.31  381.82 3308.21  375.01 3543.09  371.48 4037.82  368.49 5801.96   372.7
 5996.86   365.8 6031.85  357.79 6061.83  366.49 6081.83  366.73 6101.82  356.97
 6126.81  353.27 6156.79  356.02 6166.79  366.72 6201.77  369.32 9690.34  367.06
10009.93   377.310140.16  385.9210355.08  393.1310759.92  424.5411094.79   427.2
#Mann= 6 ,-1 , 0
       0     .07       0   531.7     .05       0 2997.16      .1       0
 6081.83    .045       0 6166.79      .1       010009.93     .06       0
#XS Ineff= 1 ,-1
       0    4227     390
Permanent Ineff=
       F
Bank Sta=6081.83,6166.79
XS Rating Curve= 0 ,0
Exp/Cntr=0.3,0.1

Type RM Length L Ch R = 1 ,94766   ,933.26,899.98,865.49
BEGIN DESCRIPTION:
LOB - Kaufman LID15
LOB IFA station 5726: flow contraction due to natural high ground
END DESCRIPTION:
XS GIS Cut Line= 3
 2581261.74532586941247.953137062571801.677959896937855.45598505
2570982.233404556938022.12264648
#Sta/Elev= 30
       0  441.21     150  437.06     485  411.89  550.51  403.27     925  390.71
    1265  393.43    1695  377.37 2224.99  375.65 2314.99  366.97 3024.99  367.47
 3129.99  374.26 3304.99  368.15 3621.26  376.78 3709.99  374.53 3749.99   379.9
 3899.98  377.94 3939.98  372.15 4074.98  375.97 4904.98  368.92 5704.98  376.77
 5914.98  365.47 6344.98  365.42 6369.98  354.66 6389.98  352.43 6414.98  355.36
 6429.98  368.42 8499.98  365.08 9326.14  368.2710244.11  424.1110886.21  426.37
#Mann= 6 ,-1 , 0
       0     .07       0  550.51     .05       0 3621.26      .1       0
 6344.98    .045       0 6429.98      .1       0 9326.14     .06       0
Levee=-1,3749.99,379.9,0,,,,
#XS Ineff= 2 ,-1
       0 3749.99     400 3749.99    5726     390
Permanent Ineff=
       F       F
Bank Sta=6344.98,6429.98
XS Rating Curve= 0 ,0
Exp/Cntr=0.3,0.1

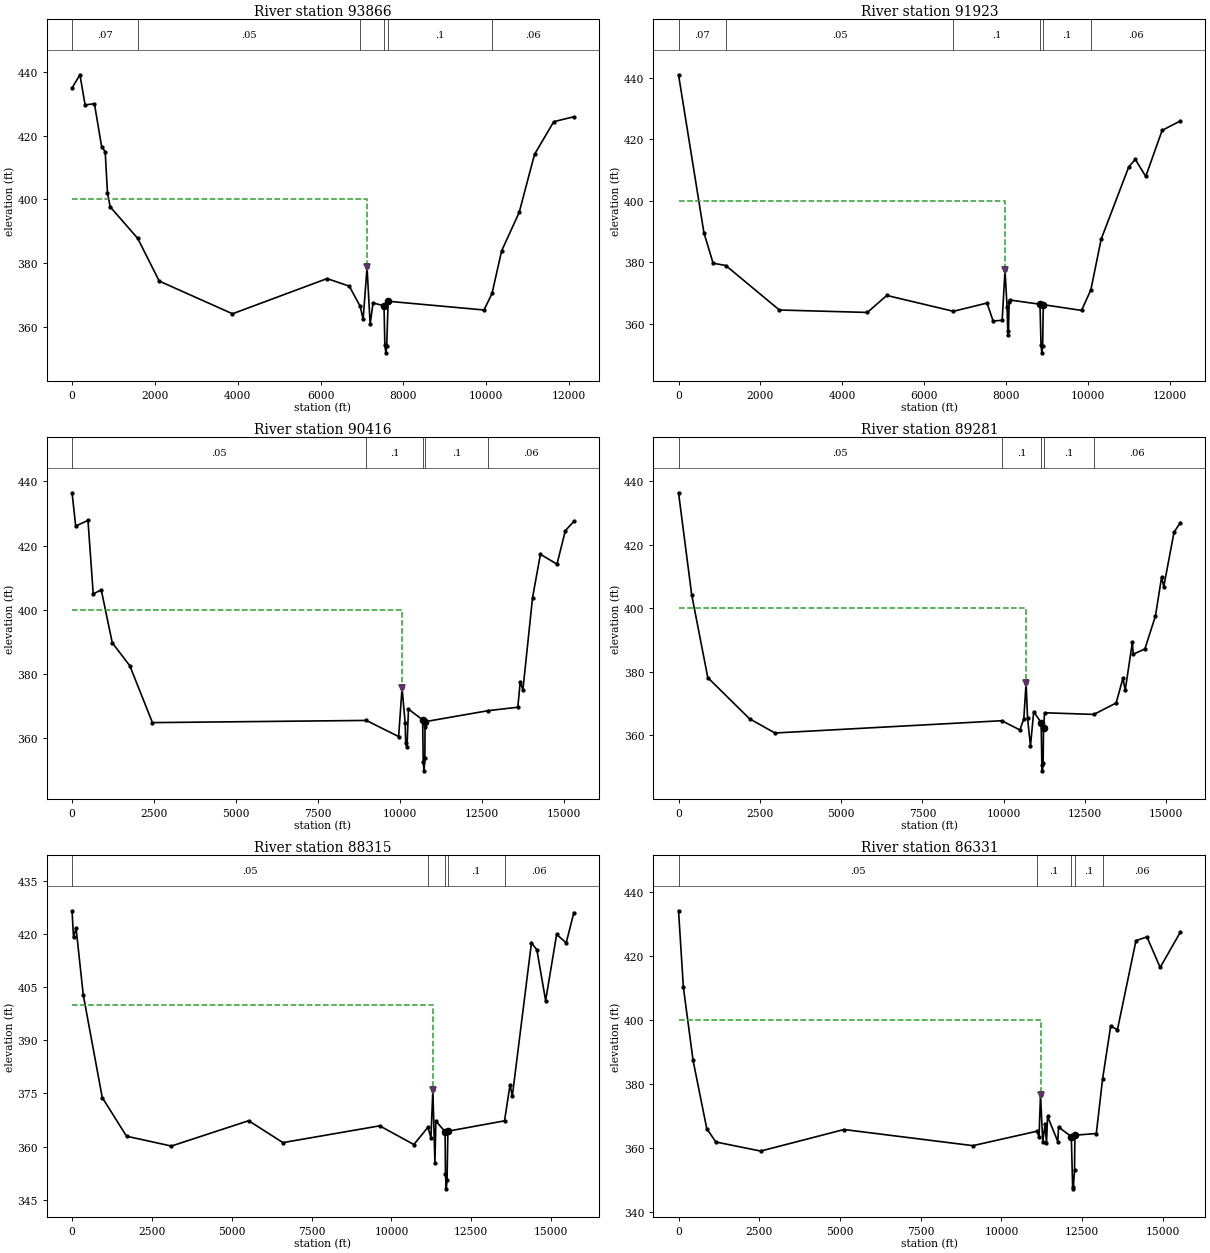
Type RM Length L Ch R = 1 ,93866   ,1064.64,1943.09,664.51
BEGIN DESCRIPTION:
LOB - Kaufman LID15
END DESCRIPTION:
XS GIS Cut Line= 3
 2582456.18978736940754.897692732572731.197754386937279.81638831
2571049.507876316937892.78235398
#Sta/Elev= 30
       0  435.02  189.95  439.14  314.92  429.67  539.86  430.07  714.81   416.5
  799.78  415.03  854.77  402.14  919.75  397.71 1585.61  387.78 2104.44  374.39
 3873.96  364.12 6158.37  375.17 6693.24  372.79 6957.36  366.48 7028.15  362.38
 7123.13  378.65 7198.11  360.88 7268.09  367.51 7533.02  366.64 7553.02  354.29
 7578.01  351.86    7598     354    7633  368.05 9947.48  365.31 10141.2  370.49
10372.41  383.8510797.41  395.95 11167.4  414.16 11632.4  424.42 12117.4  425.97
#Mann= 6 ,-1 , 0
       0     .07       0 1585.61     .05       0 6957.36      .1       0
 7533.02    .045       0    7633      .1       0 10141.2     .06       0
Levee=-1,7123.13,378.65,0,,,,
#XS Ineff= 2 , 0
       0 7123.13     400               0
Permanent Ineff=
       F       F
Bank Sta=7533.02,7633
XS Rating Curve= 0 ,0
Exp/Cntr=0.3,0.1

Type RM Length L Ch R = 1 ,91923   ,989.78,1507.45,1487.6
BEGIN DESCRIPTION:
LOB - Kaufman LID15
END DESCRIPTION:
XS GIS Cut Line= 4
2582588.134077226940053.508675562575408.796073726937075.24789982
2572856.712595226936981.497759222571096.296168556937783.58112881
#Sta/Elev= 30
       0  440.89  619.81  389.67  844.74  379.74 1154.81     379 2464.23  364.56
 4613.55  363.77  5088.4  369.28 6717.32  364.14 7537.66  366.82 7687.61  360.97
 7907.52  361.24 7977.49  377.41 8027.46  365.56 8047.45  356.47 8062.45  357.66
 8077.44  367.17 8092.43  367.81 8832.09  366.43 8857.08  353.27 8877.07  350.66
 8897.06  352.91 8912.05  366.29 9846.62  364.43   10075   371.1 10326.4  387.53
11001.26  411.0211161.23  413.4311416.18   407.9 11816.1  422.8412261.02  425.91
#Mann= 6 ,-1 , 0
       0     .07       0 1154.81     .05       0 6717.32      .1       0
 8832.09    .045       0 8912.05      .1       0   10075     .06       0
Levee=-1,7977.49,377.41,0,,,,
#XS Ineff= 2 , 0
       0 7977.49     400               0
Permanent Ineff=
       F       F
Bank Sta=8832.09,8912.05
XS Rating Curve= 0 ,0
Exp/Cntr=0.3,0.1

Type RM Length L Ch R = 1 ,90416   ,1035.09,1134.87,1123.78
BEGIN DESCRIPTION:
LOB - Kaufman LID15
END DESCRIPTION:
XS GIS Cut Line= 3
 2584615.91184586939747.953184312574023.915641386935547.15581164
2571961.313467386932234.53579648
#Sta/Elev= 30
       0  436.45     110  426.07  484.98  427.84  644.98  404.92  889.97  406.16
 1224.96  389.67 1759.94  382.51 2449.91  364.77 8970.28  365.45 9954.86  360.42
10059.86  375.5810154.86  364.6110169.86  358.2810209.86  357.0210254.86  368.95
10687.03  365.6510704.86  352.3710729.86  349.7310754.86  353.6910759.86  363.41
10765.61  365.0712686.94   368.513588.21  369.5713663.15  377.5913743.09  374.96
14037.87  403.7614277.69  417.2814782.31  414.1815037.12  424.6415296.92  427.53
#Mann= 5 ,-1 , 0
       0     .05       0 8970.28      .1       010687.03    .045       0
10765.61      .1       012686.94     .06       0
Levee=-1,10059.86,375.58,0,,,,
#XS Ineff= 2 , 0
       010059.86     400               0
Permanent Ineff=
       F       F
Bank Sta=10687.03,10765.61
XS Rating Curve= 0 ,0
Exp/Cntr=0.3,0.1

Type RM Length L Ch R = 1 ,89281   ,910.58,965.47,940.73
BEGIN DESCRIPTION:
LOB - Kaufman LID15
END DESCRIPTION:
XS GIS Cut Line= 3
2585525.634107726939025.730875482574455.613268816934616.69769882
 2572080.67116836932028.37282299
#Sta/Elev= 30
       0   436.3  404.86  404.21  899.68  378.18 2184.23  365.24 2963.95  360.77
 9937.83  364.6310496.17  361.7310616.13  365.18 10686.1  376.5310731.08  365.46
10821.05   356.710921.01   367.511150.26  363.9711170.91  350.7911185.91  348.87
 11210.9  351.4611222.05  362.4511255.88  367.1312769.57  366.6113454.72   370.2
 13664.6  377.9713734.56   374.213954.43  389.3413979.42  385.54 14339.2   387.2
14664.01  397.58 14853.9  409.8614918.86  406.7515233.68  423.8415428.57  426.93
#Mann= 5 ,-1 , 0
       0     .05       0 9937.83      .1       011150.26    .045       0
11222.05      .1       012769.57     .06       0
Levee=-1,10686.1,376.53,0,,,,
#XS Ineff= 2 , 0
       0 10686.1     400               0
Permanent Ineff=
       F       F
Bank Sta=11150.26,11222.05
XS Rating Curve= 0 ,0
Exp/Cntr=0.3,0.1

Type RM Length L Ch R = 1 ,88315   ,1019.33,1984.52,897.83
BEGIN DESCRIPTION:
LOB - Kaufman LID15
END DESCRIPTION:
XS GIS Cut Line= 3
2586421.467617886938338.230938152575096.479113066933917.55998948
2572200.028541136931854.76162164
#Sta/Elev= 30
       0   426.5   44.99  418.99  124.97  421.65  349.92  402.83  944.78  373.86
 1704.61  362.96 3109.28  360.18  5528.7  367.32 6603.44  361.15 9632.77  365.88
10702.57  360.61 11143.8  365.4711237.46  362.5311297.45   375.911362.44  355.44
11392.43  367.2311680.33  364.2411692.37  352.2511717.37  348.1211742.36  350.61
11768.54  364.3713541.43  367.2913715.45  377.4713785.37  374.2214384.67  417.43
14554.47  415.5114829.15  401.1815173.74  419.8515473.39  417.4515713.11  425.98
#Mann= 5 ,-1 , 0
       0     .05       0 11143.8      .1       011680.33    .045       0
11768.54      .1       013541.43     .06       0
Levee=-1,11297.45,375.9,0,,,,
#XS Ineff= 2 , 0
       011297.45     400               0
Permanent Ineff=
       F       F
Bank Sta=11680.33,11768.54
XS Rating Curve= 0 ,0
Exp/Cntr=0.3,0.1

Type RM Length L Ch R = 1 ,86331   ,684.5,678.4,518.16
BEGIN DESCRIPTION:
LOB - Kaufman LID15
END DESCRIPTION:
XS GIS Cut Line= 3
2586768.68969247 6937386.84209292575601.844900226933018.82294181
2572330.236942146931637.74761997
#Sta/Elev= 30
       0  434.04  149.95  410.13  449.84   387.3  874.69  365.98 1154.59  361.81
 2544.09  358.97 5123.21   365.7 9116.82  360.6611101.23  365.1711166.02  363.39
   11211  376.6411280.98  361.9111355.95  367.5411395.93  361.3611430.92  369.79
11745.79  361.9511770.78  366.47 12165.5  363.4912205.45  347.8812225.43  347.17
12265.38  353.1112275.37  363.9312939.61  364.4513132.21  381.38 13384.1  398.01
13593.86   396.914168.21  424.7314507.82  425.8714917.35  416.3315541.64  427.35
#Mann= 5 ,-1 , 0
       0     .05       011101.23      .1       0 12165.5    .045       0
12275.37      .1       013132.21     .06       0
Levee=-1,11211,376.64,0,,,,
#XS Ineff= 2 , 0
       0   11211     400               0
Permanent Ineff=
       F       F
Bank Sta=12165.5,12275.37
XS Rating Curve= 0 ,0
Exp/Cntr=0.3,0.1

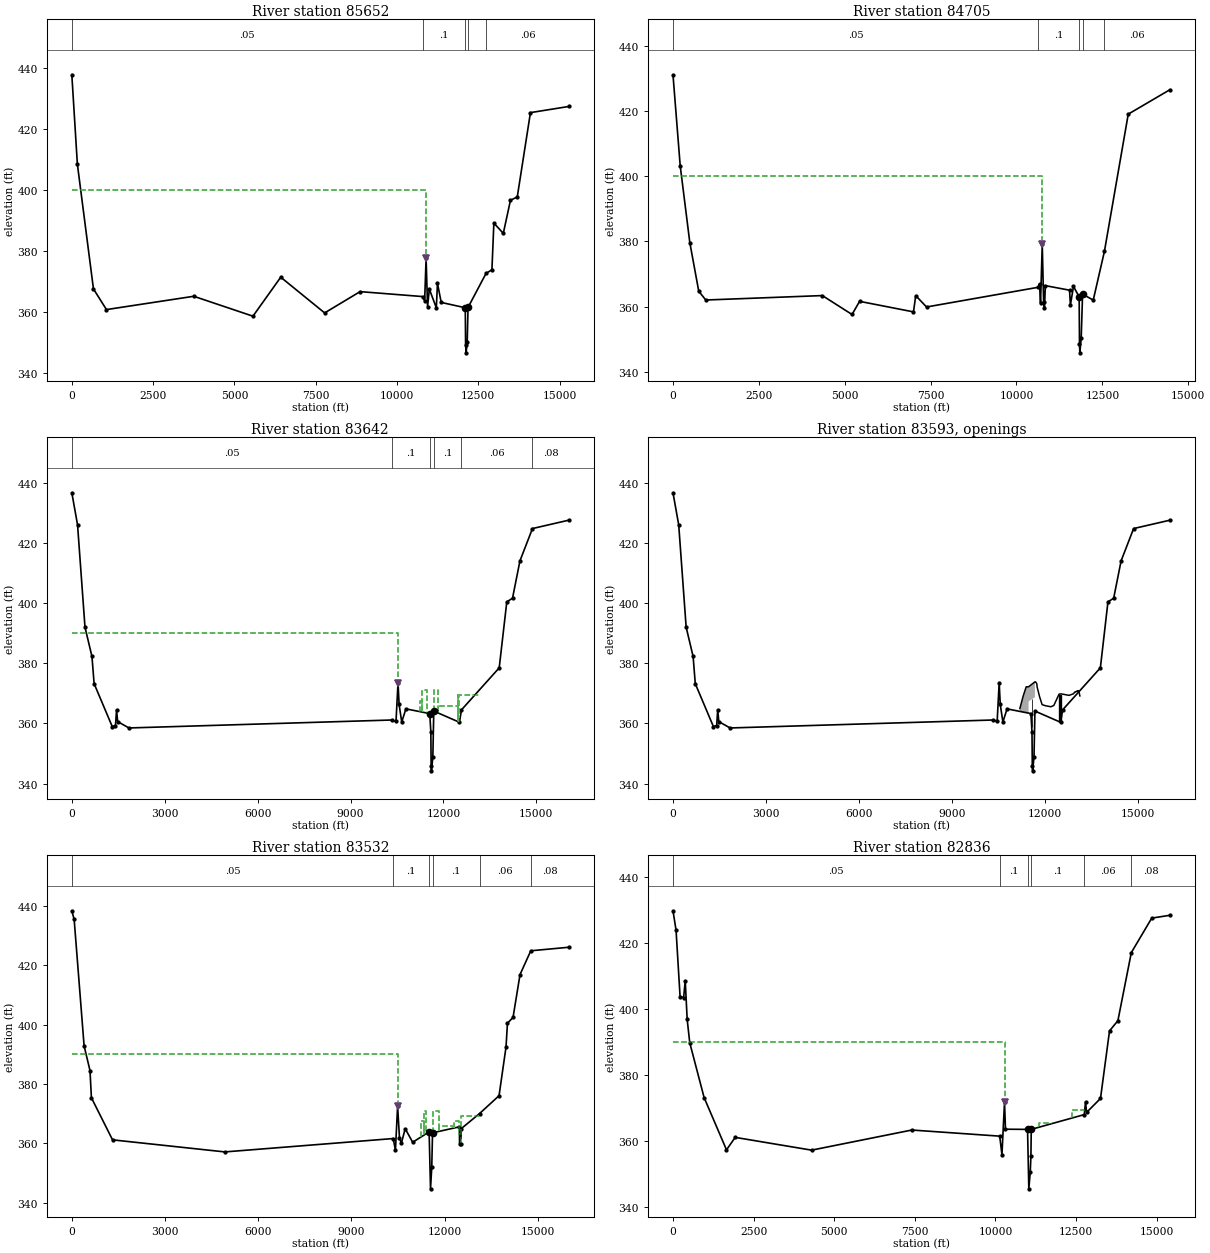
Type RM Length L Ch R = 1 ,85652   ,1013.2,947.16,954.31
BEGIN DESCRIPTION:
LOB - Kaufman LID15
END DESCRIPTION:
XS GIS Cut Line= 3
2587011.745308736936178.508551572576480.14727747 6932769.2548714
2572514.698843556931344.77904581
#Sta/Elev= 30
       0  437.65  169.99  408.47  664.98  367.65 1064.97  360.89 3749.89  365.24
 5569.85  358.73 6424.83  371.48 7774.81   359.8  8864.8  366.7610794.88  365.14
 10849.8  363.73 10894.8  377.66 10939.8  361.85 10994.8  367.5711209.75  361.48
11244.73  369.4611359.69  363.23 12099.4  361.4912109.39  349.4312124.39  346.75
12159.38  350.2412184.37  361.5812738.84  372.7312919.08   373.912979.05  389.17
13268.94  385.8113488.86  396.6113698.77  397.7314103.62  425.2815283.15  427.29
#Mann= 5 ,-1 , 0
       0     .05       010794.88      .1       0 12099.4    .045       0
12184.37      .1       012738.84     .06       0
Levee=-1,10894.8,377.66,0,,,,
#XS Ineff= 2 , 0
       0 10894.8     400               0
Permanent Ineff=
       F       F
Bank Sta=12099.4,12184.37
XS Rating Curve= 0 ,0
Exp/Cntr=0.3,0.1

Type RM Length L Ch R = 1 ,84705   ,862.37,1063.63,1377.28
BEGIN DESCRIPTION:
LOB - Kaufman LID15
END DESCRIPTION:
XS GIS Cut Line= 3
2587233.967633316935185.453122972576864.320065566931842.42437598
2573415.306294316930910.75137056
#Sta/Elev= 30
       0  431.11  209.91  403.22  489.78  379.65  749.67  364.75  954.58  362.04
  4348.1   363.4 5212.72   357.6 5432.62  361.63 7001.93   358.4  7066.9  363.39
 7381.77   359.910631.43  365.9410670.44  367.0410700.43  361.0910750.41  379.11
10790.39  361.3710815.38  359.6110840.38  366.4511544.97  365.0511569.95  360.52
 11659.9   366.211824.54  363.0211834.79  348.5211844.79  345.8411884.77  350.43
11924.23  363.8512234.56  362.01 12559.7  376.9213253.95  419.0414468.23  426.54
#Mann= 5 ,-1 , 0
       0     .05       010631.43      .1       011824.54    .045       0
11924.23      .1       0 12559.7     .06       0
Levee=-1,10750.41,379.11,0,,,,
#XS Ineff= 2 , 0
       010750.41     400               0
Permanent Ineff=
       F       F
Bank Sta=11824.54,11924.23
XS Rating Curve= 0 ,0
Exp/Cntr=0.5,0.3

Type RM Length L Ch R = 1 ,83642   ,101.77,109.11,115.85
BEGIN DESCRIPTION:
US Bridge
LOB - Kaufman LID15
END DESCRIPTION:
XS GIS Cut Line= 4
2587467.995380486934346.564380812576670.911003566930886.36362407
2575365.001869986929584.878366142572512.52857231 6929303.9803059
#Sta/Elev= 30
       0   436.7  184.97  426.02  424.92     392  649.88  382.25  719.87  373.21
 1304.77  358.95 1409.75  359.27 1444.75  364.53 1479.74  360.59 1844.68  358.48
10343.22  361.1310468.19  360.6610533.18  373.5710568.17  366.2910653.16  360.46
10788.13  364.8311557.87  363.2611592.85  357.2211602.84   345.711612.84  344.22
11657.81   348.811687.79   364.112516.89  360.3712582.18   364.513800.92  378.47
14045.59  400.4214230.33  401.6214470.01  414.0414874.45   424.816047.85  427.59
#Mann= 6 ,-1 , 0
       0     .05       010343.22      .1       011557.87    .045       0
11687.79      .1       012582.18     .06       014874.45     .08       0
Levee=-1,10533.18,373.57,0,,,,
#XS Ineff= 7 ,-1
       010533.18     390   11250   11321   367.6   11321   11467     371
   11704   11820     371   11820   12459   365.8   12459   12477   369.4
   12518   13170   369.4
Permanent Ineff=
       F       F       F       F       F       F       F
Bank Sta=11557.87,11687.79
XS Rating Curve= 0 ,0
Exp/Cntr=0.5,0.3

Type RM Length L Ch R = 4 ,83593   ,,,
BEGIN DESCRIPTION:
East Malloy Bridge Road - Bridge geometry per Compass survey dated October 2017.  Road deck supplemented with Lidar data outside of the surveyed bridge/culvert openings.
END DESCRIPTION:
Node Name=E Malloy Bridge
Bridge Culvert--1,0,-1,-1, 0
Deck Dist Width WeirC Skew NumUp NumDn MinLoCord MaxHiCord MaxSubmerge Is_Ogee
30,32,2.6,0, 62, 62, , , 0.98, 0, 0,0,,
11201.3111306.0111405.7511481.5211481.52   11687   11687 11708.1 11748.1 11759.8
11839.5811919.3712034.0612203.4212297.99 12465.5 12495.5 12542.112790.7812930.15
12935.1312940.1112945.0812950.0612955.0412960.0212964.9912969.9712974.9512979.93
 12984.912989.8812994.8612999.8413004.8113009.7913014.7713019.7513024.72 13029.7
13034.6813039.6613044.6313049.6113054.5913059.5713064.5513069.52 13074.513079.48
13084.4613089.4313094.4113099.3913104.3713109.3613114.3613119.3613124.3513129.35
13134.3413139.34
 364.945 369.016 372.173 372.173 372.173 373.811 373.811 373.811 373.194 372.023
 368.833 366.244 365.858 365.534 365.965   369.7   369.8   369.8 369.322 369.847
 369.884  369.96 370.034  370.11 370.185 370.259 370.314 370.373 370.412 370.412
 370.425 370.486 370.509 370.553 370.527 370.518 370.505 370.552   370.6 370.661
  370.67  370.65 370.664 370.662 370.757 370.737 370.685 370.713 370.756 370.818
 370.882 370.827 370.836 370.861 370.843 370.671 370.394 370.114 369.835  369.57
 369.348  369.14
                                   367.3   368.7
11201.3111306.0111405.75 11418.3 11418.3 11623.1 11623.1 11645.1   11685 11759.8
11839.5811919.3712034.0612203.4212297.99 12465.5 12495.5 12542.112790.7812930.15
12935.1312940.1112945.0812950.0612955.0412960.0212964.9912969.9712974.9512979.93
 12984.912989.8812994.8612999.8413004.8113009.7913014.7713019.7513024.72 13029.7
13034.6813039.6613044.6313049.6113054.5913059.5713064.5513069.52 13074.513079.48
13084.4613089.4313094.4113099.3913104.3713109.3613114.3613119.3613124.3513129.35
13134.3413139.34
 364.945 369.016 372.173 372.173 372.173 373.811 373.811 373.811 373.194 372.023
 368.833 366.244 365.858 365.534 365.965   369.7   369.8   369.8 369.322 369.847
 369.884  369.96 370.034  370.11 370.185 370.259 370.314 370.373 370.412 370.412
 370.425 370.486 370.509 370.553 370.527 370.518 370.505 370.552   370.6 370.661
  370.67  370.65 370.664 370.662 370.757 370.737 370.685 370.713 370.756 370.818
 370.882 370.827 370.836 370.861 370.843 370.671 370.394 370.114 369.835  369.57
 369.348  369.14
                                   367.3   368.7
Pier Skew, UpSta & Num, DnSta & Num=  ,11584.53, 2 ,11525.9, 2 , 0 , 0 , 0 ,,
       3       3
       0     370
       3       3
       0     370
BR Coef=-1 , 0 , 0 ,, 0 ,,,0.8,-1,,0,
WSPro=,,,, 1 ,,,, 0 ,,,, 0 ,,,,-1 ,-1 ,-1 , 0 , 0 , 0 , 0 , 0
Multiple Barrel Culv=2,9,9,30.2,0.013,0.4,1,8,1,360.37,359.96, 4,Culvert #1  , 0 ,30
12483.4812483.3512493.0812492.9512502.8512502.6712512.3912512.34
BC Culvert Barrel=1,Barrel #1,0
BC Culvert Barrel=2,Barrel #2,0
BC Culvert Barrel=3,Barrel #3,0
BC Culvert Barrel=4,Barrel #4,0
Culvert Bottom n=0.013
BC Mult= 3 ,0,12475,0,12475
BC Mult= 2 ,11690,16047.85,11625,15994.46
BC Design=,, 0 ,, 0 ,,,,,,
BC Use User HTab Curves=0
BC User HTab FreeFlow(D)= 0

Type RM Length L Ch R = 1 ,83532   ,653.52,696.01,503.42
BEGIN DESCRIPTION:
DS Bridge
LOB - Kaufman LID15
END DESCRIPTION:
XS GIS Cut Line= 4
 2587443.68965486934228.508842652576724.39580472 6930798.4851909
2575410.315427636929488.856248482572540.306403896929199.81384756
#Sta/Elev= 30
       0  438.44      75  435.53  394.99  392.88  584.98  384.55  629.98   375.4
 1309.96   361.2 4924.86  357.1310344.69  361.6410414.75  357.6610484.75  372.55
10544.75  361.9510604.75  360.0210729.75  364.9510969.75  360.3811499.13   363.9
11544.01  344.6811583.91  351.8811608.85  363.5612471.65  365.5912478.85  359.96
12516.84  359.9612536.49  365.0113123.95  370.08 13749.9  376.0913974.86  392.56
14019.85  400.5214199.81  402.4614424.77  416.93 14771.4  424.9515994.46  426.14
#Mann= 6 ,-1 , 0
       0     .05       010344.69      .1       011499.13    .045       0
11608.85      .1       013123.95     .06       0 14771.4     .08       0
Levee=-1,10484.75,372.55,0,,,,
#XS Ineff= 7 ,-1
       010484.75     390   11250   11321   367.6   11321   11413     371
   11626   11820     371   11820   12298   365.8   12298   12475   367.6
   12518   13120   369.4
Permanent Ineff=
       F       F       F       F       F       F       F
Bank Sta=11499.13,11608.85
XS Rating Curve= 0 ,0
Exp/Cntr=0.5,0.3

Type RM Length L Ch R = 1 ,82836   ,757.82,873.74,766.88
BEGIN DESCRIPTION:
LOB - Kaufman LID15
END DESCRIPTION:
XS GIS Cut Line= 4
2587304.800824976933468.092056392577635.153169566930425.75758989
2575656.730289136929319.511442812572700.028525386928762.31373832
#Sta/Elev= 30
       0  429.75   94.97  423.88  219.93  403.67   329.9  403.41  379.89  408.49
  439.87   396.8  519.84  389.69  964.71  373.07  1659.5  357.19 1929.42  360.98
 4298.74   357.1 7407.85  363.21 10133.1  361.3510201.81  355.7310281.69  371.64
10311.64  363.4610995.64   363.411035.58  345.3611080.51  350.5411100.48  355.34
11110.84  363.4112755.36  367.8912793.41  371.76 12828.4  368.5613258.23  372.79
13538.12   393.313798.02   396.414214.28  417.0614847.61  427.5215412.39  428.39
#Mann= 6 ,-1 , 0
       0     .05       0 10133.1      .1       010995.64    .045       0
11110.84      .1       012755.36     .06       014214.28     .08       0
Levee=-1,10281.69,371.64,0,,,,
#XS Ineff= 3 ,-1
       010281.69     390   11364   11711   365.2   12385   12770   369.4
Permanent Ineff=
       F       F       F
Bank Sta=10995.64,11110.84
XS Rating Curve= 0 ,0
Exp/Cntr=0.3,0.1