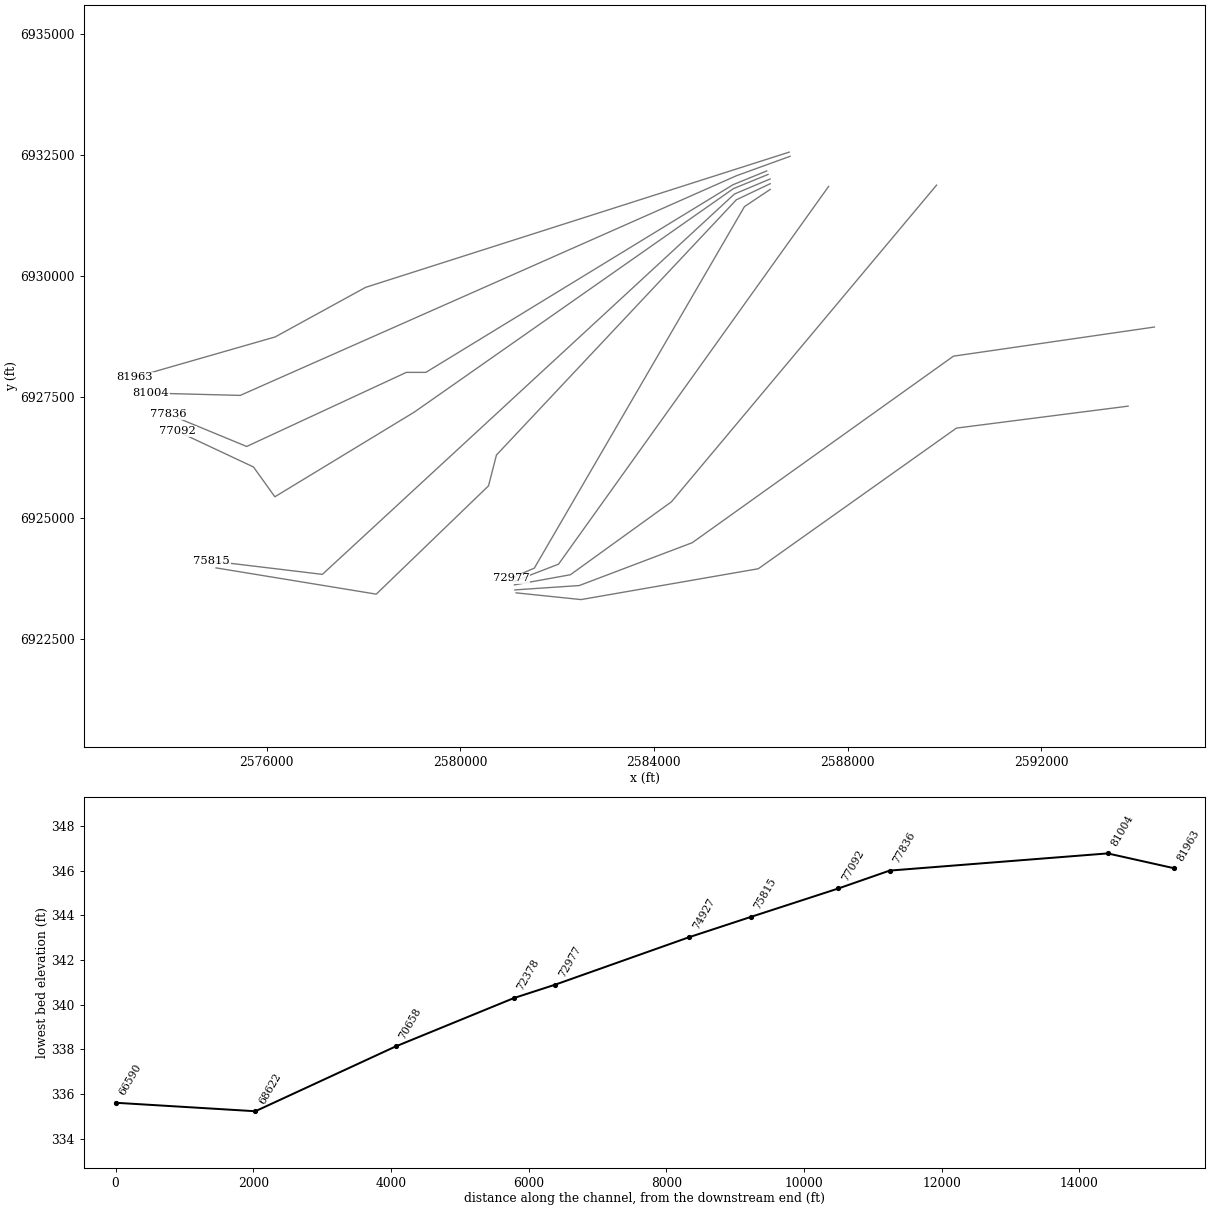
HEC-RAS study EF_FEMA.prj: East_Fork_FEMA

--- EF_FEMA.g06 (geometry) --- (continued)

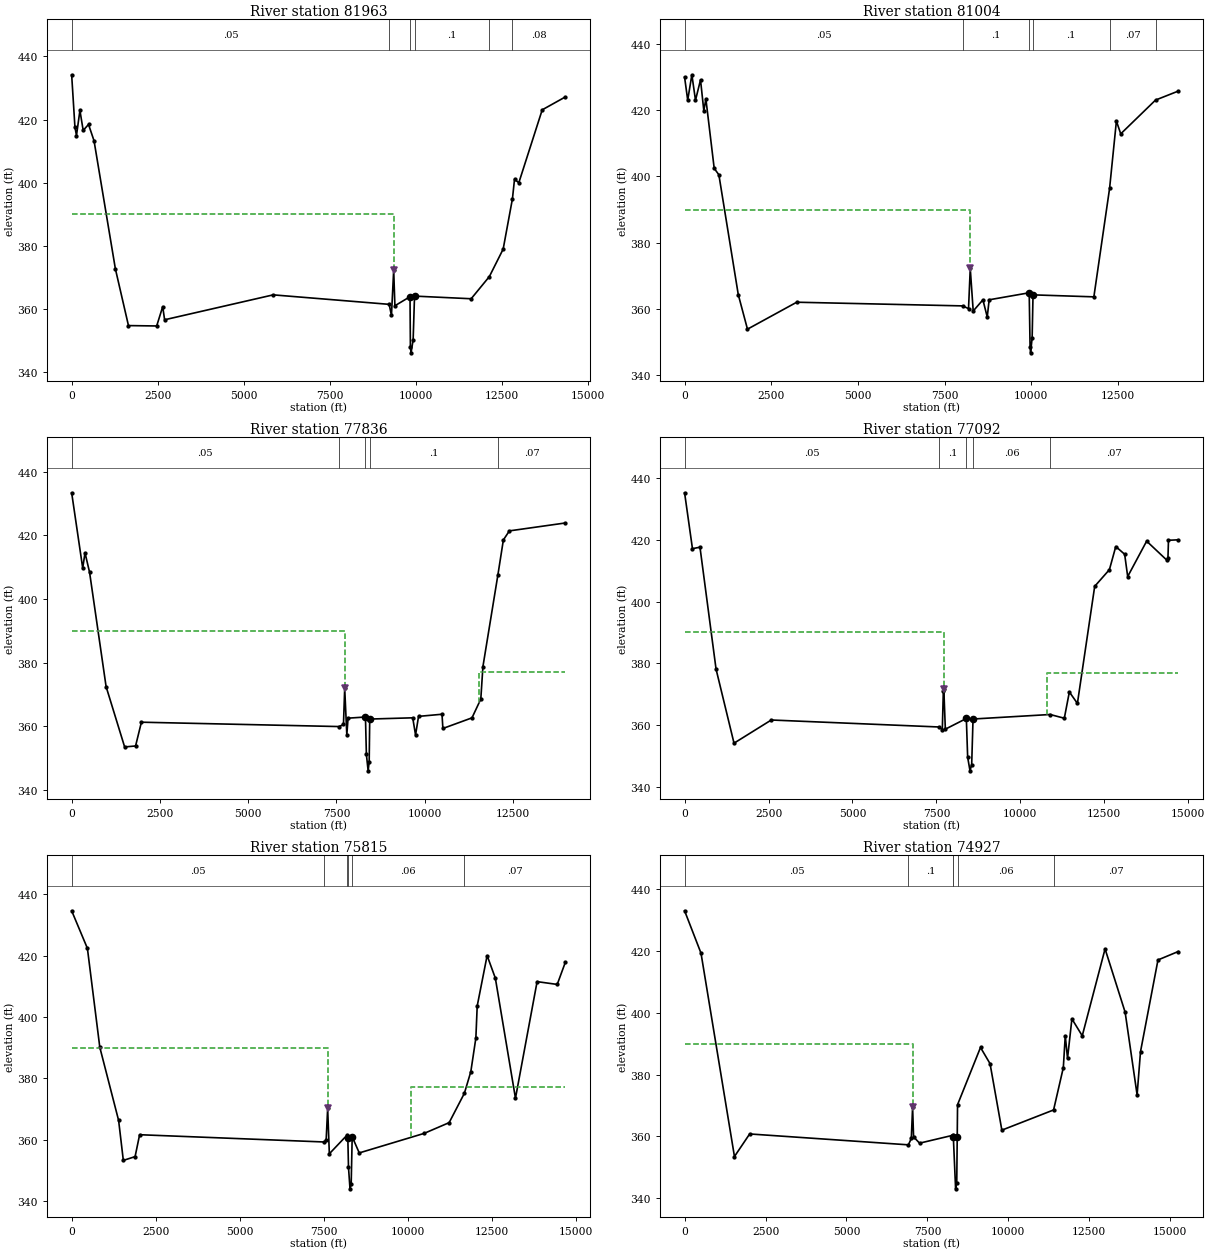
Type RM Length L Ch R = 1 ,81963   ,763.86,958.88,840.21
BEGIN DESCRIPTION:
LOB - Kaufman LID15
END DESCRIPTION:
XS GIS Cut Line= 4
2586794.384194886932558.369794472578043.976170816929762.79664548
2576176.819800146928738.257684072573276.417464466927904.67470557
#Sta/Elev= 30
       0  434.18   94.96  417.62  139.94  414.95   239.9  422.89  334.86  416.56
  489.79  418.45  649.73  413.28 1269.47  372.72 1649.31  354.75 2468.96  354.63
 2643.88  360.75 2698.86  356.59 5852.56  364.48 9219.59  361.48 9286.24  357.97
 9351.23  372.32 9386.23  361.03 9825.15   363.9 9836.18  347.92 9856.17  346.12
 9916.17  350.28 9956.16  364.0911600.78  363.2512129.63  370.2812530.05  378.97
12799.39  394.91 12859.8  401.08 12984.7  399.9913664.17  423.0814333.64  427.15
#Mann= 6 ,-1 , 0
       0     .05       0 9219.59      .1       0 9825.15    .045       0
 9956.16      .1       012129.63     .06       012799.39     .08       0
Levee=-1,9351.23,372.32,0,,,,
#XS Ineff= 2 , 0
       0 9351.23     390               0
Permanent Ineff=
       F       F
Bank Sta=9825.15,9956.16
XS Rating Curve= 0 ,0
Exp/Cntr=0.3,0.1

Type RM Length L Ch R = 1 ,81004   ,893.94,3167.54,1000.79
BEGIN DESCRIPTION:
LOB - Kaufman LID15
END DESCRIPTION:
XS GIS Cut Line= 4
2586811.745380646932471.564193822585703.914591066932070.11224081
2575455.980690646927529.815219062573609.533924226927577.34563582
#Sta/Elev= 30
       0  429.93   89.87  423.01   209.7  430.66  314.55  422.98  459.35  429.14
  554.21  419.83  614.13  423.35  853.79  402.43  988.59  400.49 1548.28  364.33
 1813.24  353.92 3233.08  362.05 8018.91  360.94 8187.58  360.11 8237.57  372.23
 8322.56   359.4 8602.51  362.76 8727.49  357.59 8782.48  362.78 9937.27   364.9
 9962.27   348.6 9977.26  346.7810022.26  351.3310047.25  364.2711801.94  363.67
12255.38   396.412451.74  416.7112576.54  412.8413580.55  423.0314233.95  425.73
#Mann= 6 ,-1 , 0
       0     .05       0 8018.91      .1       0 9937.27    .045       0
10047.25      .1       012255.38     .07       013580.55     .08       0
Levee=-1,8237.57,372.23,0,,,,
#XS Ineff= 2 , 0
       0 8237.57     390               0
Permanent Ineff=
       F       F
Bank Sta=9937.27,10047.25
XS Rating Curve= 0 ,0
Exp/Cntr=0.3,0.1

Type RM Length L Ch R = 1 ,77836   ,308.65,744.14,1041.53
BEGIN DESCRIPTION:
LOB - Kaufman LID15
ROB IFA station 11533: flow contraction due to natural high ground downstream
END DESCRIPTION:
XS GIS Cut Line= 6
2586329.106582146932169.480808482585634.53480855 6931884.9669418
2579288.946777976928005.586577222578886.169040226928005.58657722
2575587.846568636926473.917724562573967.606698896927143.31763248
#Sta/Elev= 30
       0  433.37  313.16  409.69  377.78   414.5  507.02  408.41  975.51  372.46
 1500.33  353.52 1810.23  353.82 1975.17  361.29 7574.07  359.92 7698.24  360.57
 7733.23  371.94 7793.21  357.31  7828.2  362.56 8321.11  362.92 8347.21   351.2
 8396.93  346.01 8426.77  348.88 8441.69  362.28 9659.82  362.67 9739.74  357.27
 9824.66  363.1210489.01  363.7910513.99  359.3211338.18  362.6611587.94  368.56
11647.88  378.7712069.63  407.4112227.31  418.5612397.11   421.413980.25  423.88
#Mann= 5 ,-1 , 0
       0     .05       0 7574.07      .1       0 8321.11    .045       0
 8441.69      .1       012069.63     .07       0
Levee=-1,7733.23,371.94,0,,,,
#XS Ineff= 2 , 0
       0 7733.23     390   11533       0     377
Permanent Ineff=
       F       F
Bank Sta=8321.11,8441.69
XS Rating Curve= 0 ,0
Exp/Cntr=0.3,0.1

Type RM Length L Ch R = 1 ,77092   ,943.98,1276.8,1378.67
BEGIN DESCRIPTION:
LOB - Kaufman LID15
ROB IFA station 10783.6: flow contraction due to natural high ground downstream
END DESCRIPTION:
XS GIS Cut Line= 6
2586356.884085646932096.56428765 2585642.12042336931804.04846847
2579052.835701636927186.142349972576169.750588556925433.65865023
2575728.610722816926049.683008732574162.919300396926785.24485782
#Sta/Elev= 30
       0  435.19  234.18  417.11   458.4  417.58  937.29  378.12 1472.24  354.16
 2582.12  361.66 7580.45   359.4 7676.66  358.53 7706.66  370.91 7721.65  371.63
 7766.65  358.69 8392.23  362.15 8431.57  349.61 8501.55  345.21 8551.53  347.26
 8591.52  361.9810888.78  363.4411310.65  362.23 11460.6  370.7311700.52  367.03
12215.35  404.9112653.98  410.3212843.39   417.813107.97  415.2913197.97  408.08
13762.92  419.5414362.87   413.414397.87  414.1914412.87  419.8214702.85  419.97
#Mann= 5 ,-1 , 0
       0     .05       0 7580.45      .1       0 8392.23    .045       0
 8591.52     .06       010888.78     .07       0
Levee=-1,7721.65,371.63,0,,,,
#XS Ineff= 2 , 0
       0 7721.65     390 10783.6       0     377
Permanent Ineff=
       F       F
Bank Sta=8392.23,8591.52
XS Rating Curve= 0 ,0
Exp/Cntr=0.3,0.1

Type RM Length L Ch R = 1 ,75815   ,500.58,888.74,1416.72
BEGIN DESCRIPTION:
LOB - Kaufman LID15
ROB IFA station 10102.8: flow contraction due to natural high ground downstream
END DESCRIPTION:
XS GIS Cut Line= 4
2586398.550997056932002.814147062585663.920248466931693.04376923
 2577151.74764036923830.090991232574868.214477726924105.12324956
#Sta/Elev= 30
       0  434.66   468.4   422.4  837.26  390.12 1397.17  366.24 1537.15  353.21
 1887.09  354.44 2022.07  361.59 7513.93  359.22 7571.07  359.76 7616.06  370.16
 7666.05  355.37 8204.61  361.59 8215.96  360.56 8235.95  350.92 8280.94  343.93
 8315.94  345.52 8345.93  360.93 8555.89  355.6510485.51  362.0211230.37  365.53
11683.22   375.111875.24  382.1612025.21  393.15 12065.2   403.612360.15  420.04
12604.67  412.6813203.38   373.513846.99  411.54 14445.7  410.6314685.19  417.79
#Mann= 6 ,-1 , 0
       0     .05       0 7513.93      .1       0 8204.61     .06       0
 8215.96    .045       0 8345.93     .06       011683.22     .07       0
Levee=-1,7616.06,370.16,0,,,,
#XS Ineff= 2 , 0
       0 7616.06     390 10102.8       0     377
Permanent Ineff=
       F       F
Bank Sta=8215.96,8345.93
XS Rating Curve= 0 ,0
Exp/Cntr=0.3,0.1

Type RM Length L Ch R = 1 ,74927   ,1396.59,1949.18,1764.62
BEGIN DESCRIPTION:
LOB - Kaufman LID15
ROB IFA station 9544: flow contraction due to natural high ground
END DESCRIPTION:
XS GIS Cut Line= 6
2586402.023102976931905.591900562585701.455606486931572.75004657
2580747.280147396926297.253379732580582.989137386925660.03910297
 2578264.4816353 6923421.52947242574955.020078396923964.06414847
#Sta/Elev= 30
       0  432.95  507.13  419.24  1540.3  353.48 2010.11  360.78 6912.73  357.26
 7003.05  359.31 7043.04  369.48 7073.02  359.85 7257.95   357.8 8294.15  360.37
 8301.79   359.7 8371.59  343.03 8406.49  345.02 8421.44  359.65 8431.41  370.24
 9140.39  388.75 9435.19  383.51 9799.93  362.0111397.72  368.5411698.64  382.23
 11758.6  392.5611828.55  385.2111963.48  397.9912283.36  392.5212988.08  420.63
13607.84  400.1513977.69  373.4414082.65  387.3914622.44  417.05 15247.2  419.77
#Mann= 6 ,-1 , 0
       0     .05       0 6912.73      .1       0 8294.15     .06       0
 8301.79    .045       0 8431.41     .06       011397.72     .07       0
Levee=-1,7043.04,369.48,0,,,,
#XS Ineff= 2 , 0
       0 7043.04     390    9544       0     377
Permanent Ineff=
       F       F
Bank Sta=8301.79,8421.44
XS Rating Curve= 0 ,0
Exp/Cntr=0.3,0.1

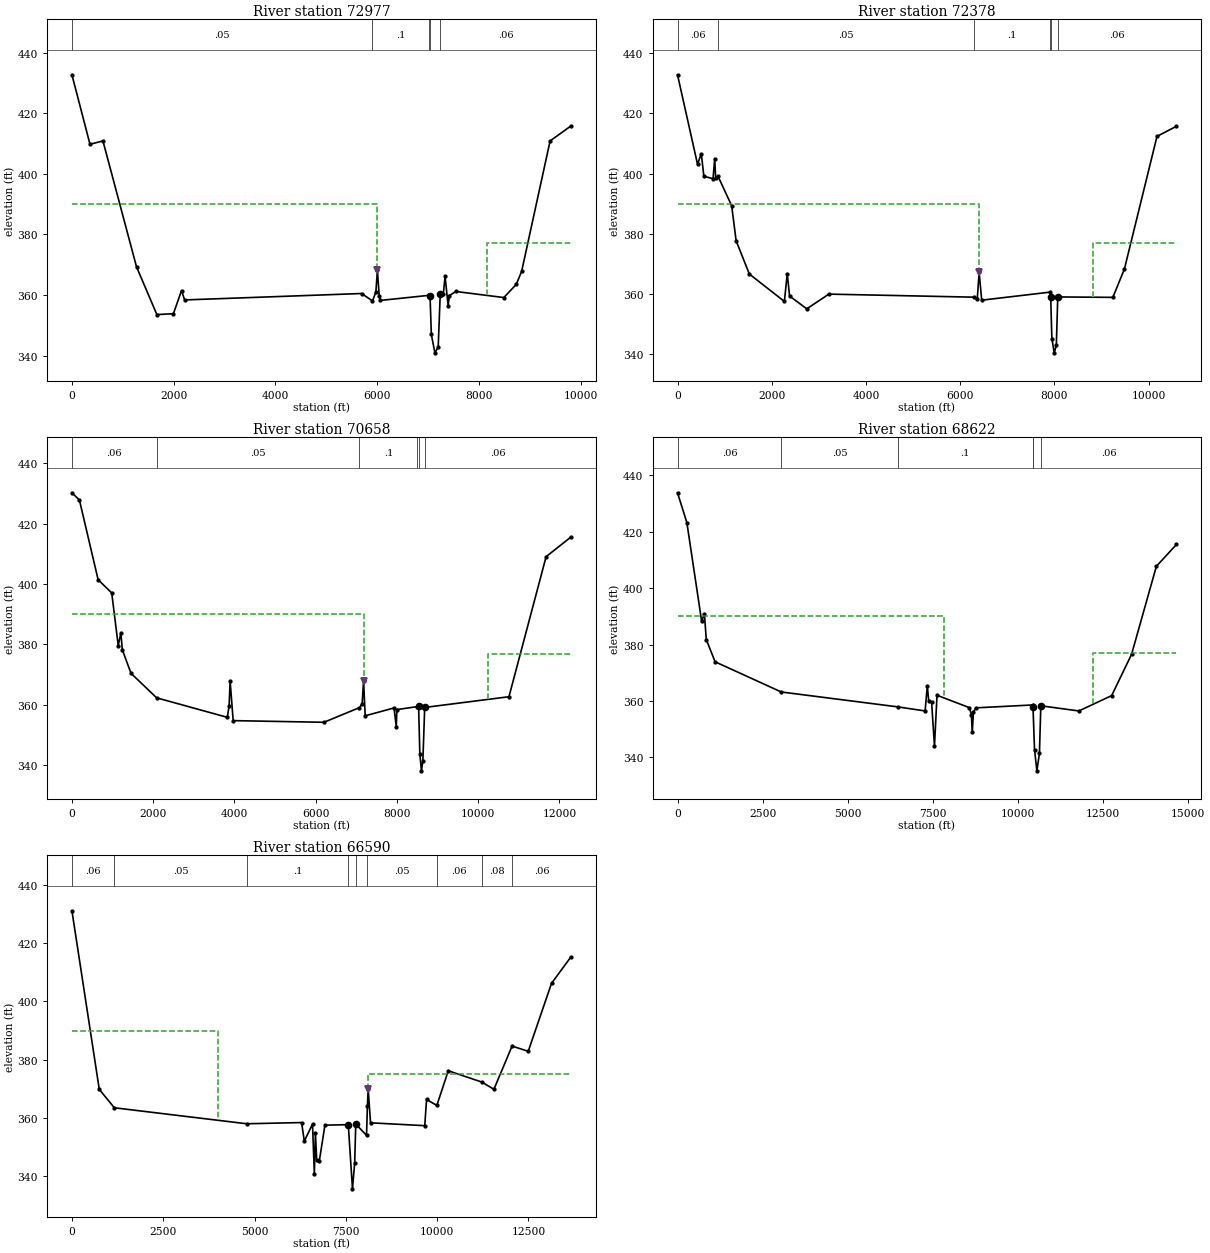
Type RM Length L Ch R = 1 ,72977   ,812.59,599.81,512.27
BEGIN DESCRIPTION:
LOB - Kaufman LID15
ROB IFA station 8157: flow expansion due to natural high ground upstream
END DESCRIPTION:
XS GIS Cut Line= 4
2586402.023102976931787.536362392585870.115374136931432.29625922
2581529.340919236923958.793161652581049.317272986923751.96614748
#Sta/Elev= 30
       0  432.67  354.79  409.74  609.64  410.83 1269.46  369.28 1669.35  353.53
 1994.26  353.82 2154.21  361.46  2214.2  358.36 5693.21  360.48  5906.6  358.02
 5973.14  360.96 6003.13  368.16 6038.12  359.81 6063.11   358.2 7023.05  359.89
 7037.98  359.62 7062.84  346.99 7132.82   340.9  7197.8   342.8 7237.79  360.36
 7297.77  360.17 7332.76  366.14 7392.75   356.5 7417.74  359.78 7542.71  361.15
 8487.46  359.15 8732.41  363.49 8837.38  367.79 9396.78  410.84 9804.96  415.76
#Mann= 5 ,-1 , 0
       0     .05       0  5906.6      .1       0 7023.05     .06       0
 7037.98    .045       0 7237.79     .06       0
Levee=-1,6003.13,368.16,0,,,,
#XS Ineff= 2 , 0
       0 6003.13     390    8157       0     377
Permanent Ineff=
       F       F
Bank Sta=7037.98,7237.79
XS Rating Curve= 0 ,0
Exp/Cntr=0.3,0.1

Type RM Length L Ch R = 1 ,72378   ,1353.88,1719.75,835.38
BEGIN DESCRIPTION:
LOB - Kaufman LID15
ROB IFA station 8827: flow expansion due to natural high ground upstream
END DESCRIPTION:
XS GIS Cut Line= 3
2587608.57679223 6931849.90631642582029.768724146924041.25625131
2581101.400502136923682.52140448
#Sta/Elev= 30
       0  432.87  424.86  403.08  504.83   406.6  559.81  399.06  754.75  398.29
  789.73  404.99  809.73  398.64  861.56  399.02 1149.61   389.3 1244.58   377.6
 1524.49  366.55 2269.24   357.4 2329.22  366.66  2379.2  359.21 2744.08  354.95
 3213.93  359.85 6295.71  358.83 6362.87  358.06 6402.85  367.13 6457.84  357.83
 7914.71  360.52 7922.34  358.84 7947.33  345.05 7997.32   340.3  8042.3  342.84
 8072.29  358.91 9241.86  358.77 9486.77  368.1710178.99  412.3610592.04  415.73
#Mann= 6 ,-1 , 0
       0     .06       0  861.56     .05       0 6295.71      .1       0
 7914.71     .06       0 7922.34    .045       0 8072.29     .06       0
Levee=-1,6402.85,367.13,0,,,,
#XS Ineff= 2 , 0
       0 6402.85     390    8827       0     377
Permanent Ineff=
       F       F
Bank Sta=7922.34,8072.29
XS Rating Curve= 0 ,0
Exp/Cntr=0.3,0.1

Type RM Length L Ch R = 1 ,70658   ,1805.09,2036.2,1079.67
BEGIN DESCRIPTION:
LOB - Kaufman LID15
ROB IFA station 10237: flow expansion due to natural high ground upstream
END DESCRIPTION:
XS GIS Cut Line= 4
2589837.743593726931875.947930982584361.332302476925329.66345139
2582274.02545346 6923822.32394642581118.761687896923613.07698956
#Sta/Elev= 30
       0  430.28     185  427.86  644.99  401.47  979.99  397.09 1139.99  379.62
 1204.99  383.88 1239.99  378.28 1454.99  370.44 2085.93  362.32 3824.95  355.86
 3869.95  359.66 3894.95  367.91 3969.95  354.77 6204.95  354.22 7078.08  359.08
 7144.95  360.34 7179.95  367.97 7219.95  356.37 7929.95  358.97 7984.95   352.8
 7999.95  358.42 8500.74  359.41 8534.86   359.5 8564.94  343.81 8604.93  338.13
 8639.93  341.39 8684.92  359.1410759.55  362.6911674.04  409.1112283.57  415.59
#Mann= 6 ,-1 , 0
       0     .06       0 2085.93     .05       0 7078.08      .1       0
 8500.74     .06       0 8534.86    .045       0 8684.92     .06       0
Levee=-1,7179.95,367.97,0,,,,
#XS Ineff= 2 , 0
       0 7179.95     390   10237       0     377
Permanent Ineff=
       F       F
Bank Sta=8534.86,8684.92
XS Rating Curve= 0 ,0
Exp/Cntr=0.3,0.1

Type RM Length L Ch R = 1 ,68622   ,1568.87,2031.43,1299.5
BEGIN DESCRIPTION:
LOB IFA station 7840: flow expansion due to Kaufman LID15 levee upstream
ROB IFA station 12204: flow expansion due to natural high ground upstream
END DESCRIPTION:
XS GIS Cut Line= 5
2594338.177506226928943.005306072590187.13757996 6928340.6866288
 2584791.22251886924484.626755642582458.030006726923599.30569164
2581127.442116726923508.91053122
#Sta/Elev= 30
       0  433.85  274.97  423.25  709.92  388.23  789.91     391   844.9  381.79
 1104.87   373.9 3047.63   363.2 6467.94  357.92 7273.27  356.47 7338.25  365.48
 7378.23  359.99  7463.2  359.71 7548.17  344.04 7623.14  362.03 8572.76  357.65
 8632.74  355.17 8657.73  348.83 8692.71  356.08 8762.69  357.5710429.59  358.59
10442.03  358.0410487.01  342.7910556.99  335.2310631.96  341.4910671.94   358.3
11790.18  356.4712753.49  361.9213337.47  376.5514066.76  407.7714656.18  415.51
#Mann= 6 ,-1 , 0
       0     .06       0 3047.63     .05       0 6467.94      .1       0
10429.59     .06       010442.03    .045       010671.94     .06       0
#XS Ineff= 2 , 0
       0    7840     390   12204       0     377
Permanent Ineff=
       F       F
Bank Sta=10442.03,10671.94
XS Rating Curve= 0 ,0
Exp/Cntr=0.3,0.1

Type RM Length L Ch R = 1 ,66590   ,1845.22,1842.01,825.61
BEGIN DESCRIPTION:
ROB - Kaufman LID10
LOB IFA station 4000: flow expansion due to Kaufman LID15 levee upstream
END DESCRIPTION:
XS GIS Cut Line= 5
2593794.774721646927307.588629392590248.669609136926853.69485214
2586155.986521566923946.590758232582493.689384226923308.87746672
 2581153.48373136923448.14654514
#Sta/Elev= 30
       0  431.18  748.96  369.79 1161.54  363.47 4784.37  357.98 6287.38  358.39
  6362.3  352.01 6587.08  357.88 6637.03  340.84    6667  354.67 6701.97  345.36
  6771.9  345.12 6926.75   357.5 7566.11  357.66    7681  335.61 7740.94  344.51
 7770.91  357.89 8065.62  353.99 8089.95  364.14 8110.57  369.99 8175.51   358.3
  9659.4  357.32 9709.37  366.32 9990.46  364.2810303.98  376.19 11216.7  372.33
11553.15  369.8312050.78  384.69 12492.3  382.8713131.05  406.2613660.02  415.29
#Mann= 9 ,-1 , 0
       0     .06       0 1161.54     .05       0 4784.37      .1       0
 7566.11    .045       0 7770.91      .1       0 8089.95     .05       0
 9990.46     .06       0 11216.7     .08       012050.78     .06       0
Levee=0,,,-1,8110.57,369.99,,
#XS Ineff= 2 , 0
       0    4000     390 8110.57       0     375
Permanent Ineff=
       F       F
Bank Sta=7566.11,7770.91
XS Rating Curve= 0 ,0
Exp/Cntr=0.3,0.1