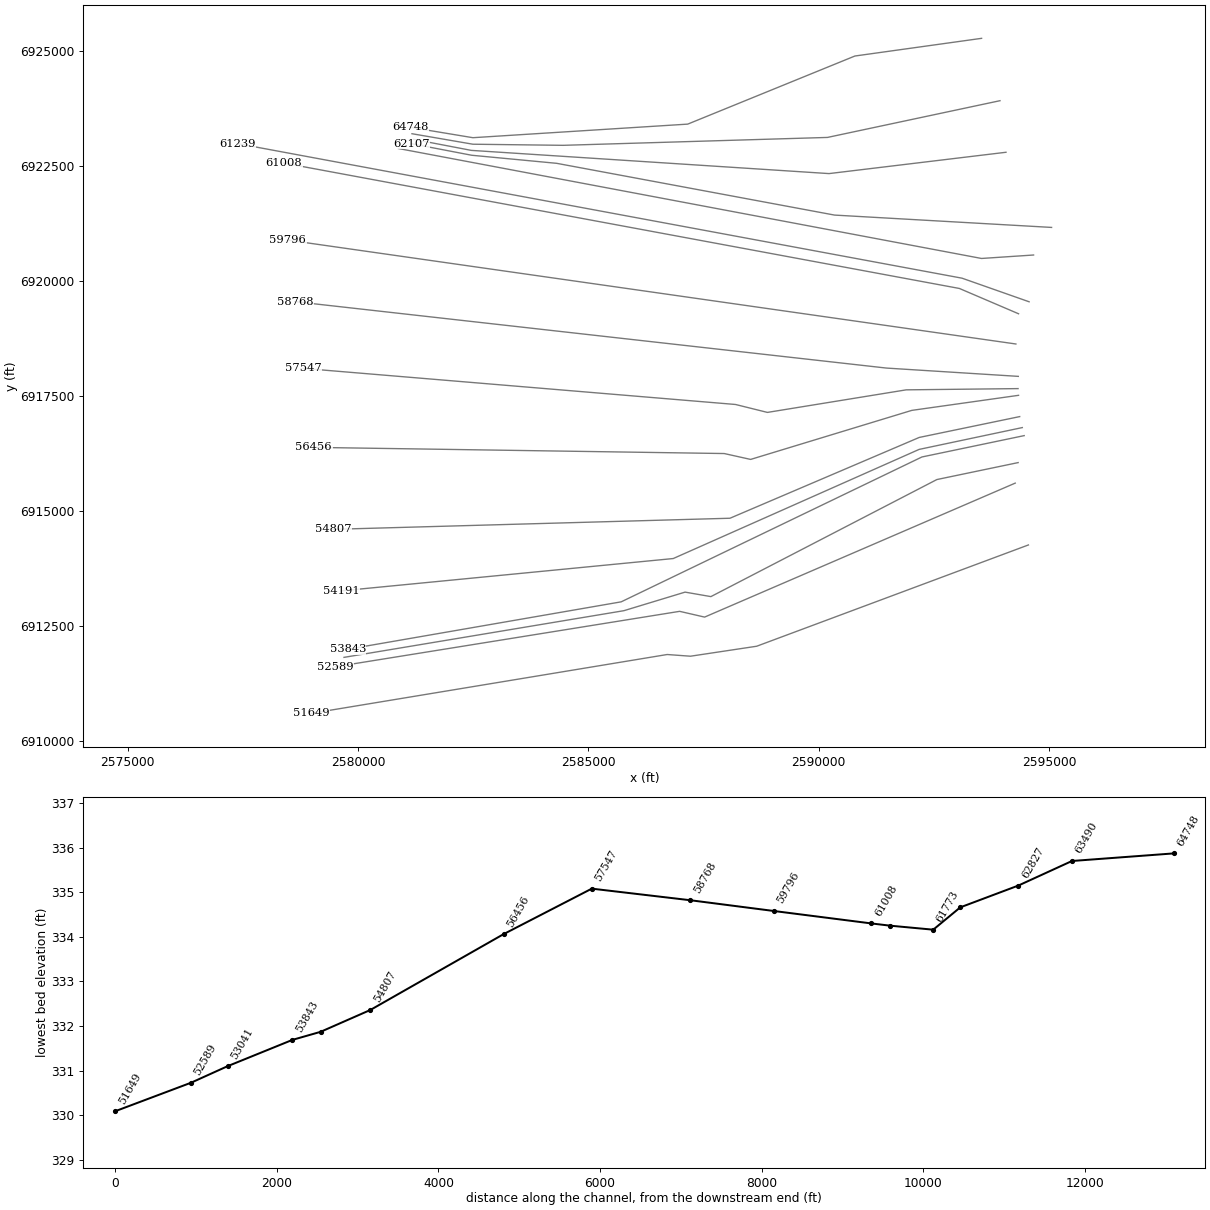
HEC-RAS study EF_FEMA.prj: East_Fork_FEMA

--- EF_FEMA.g06 (geometry) --- (continued)

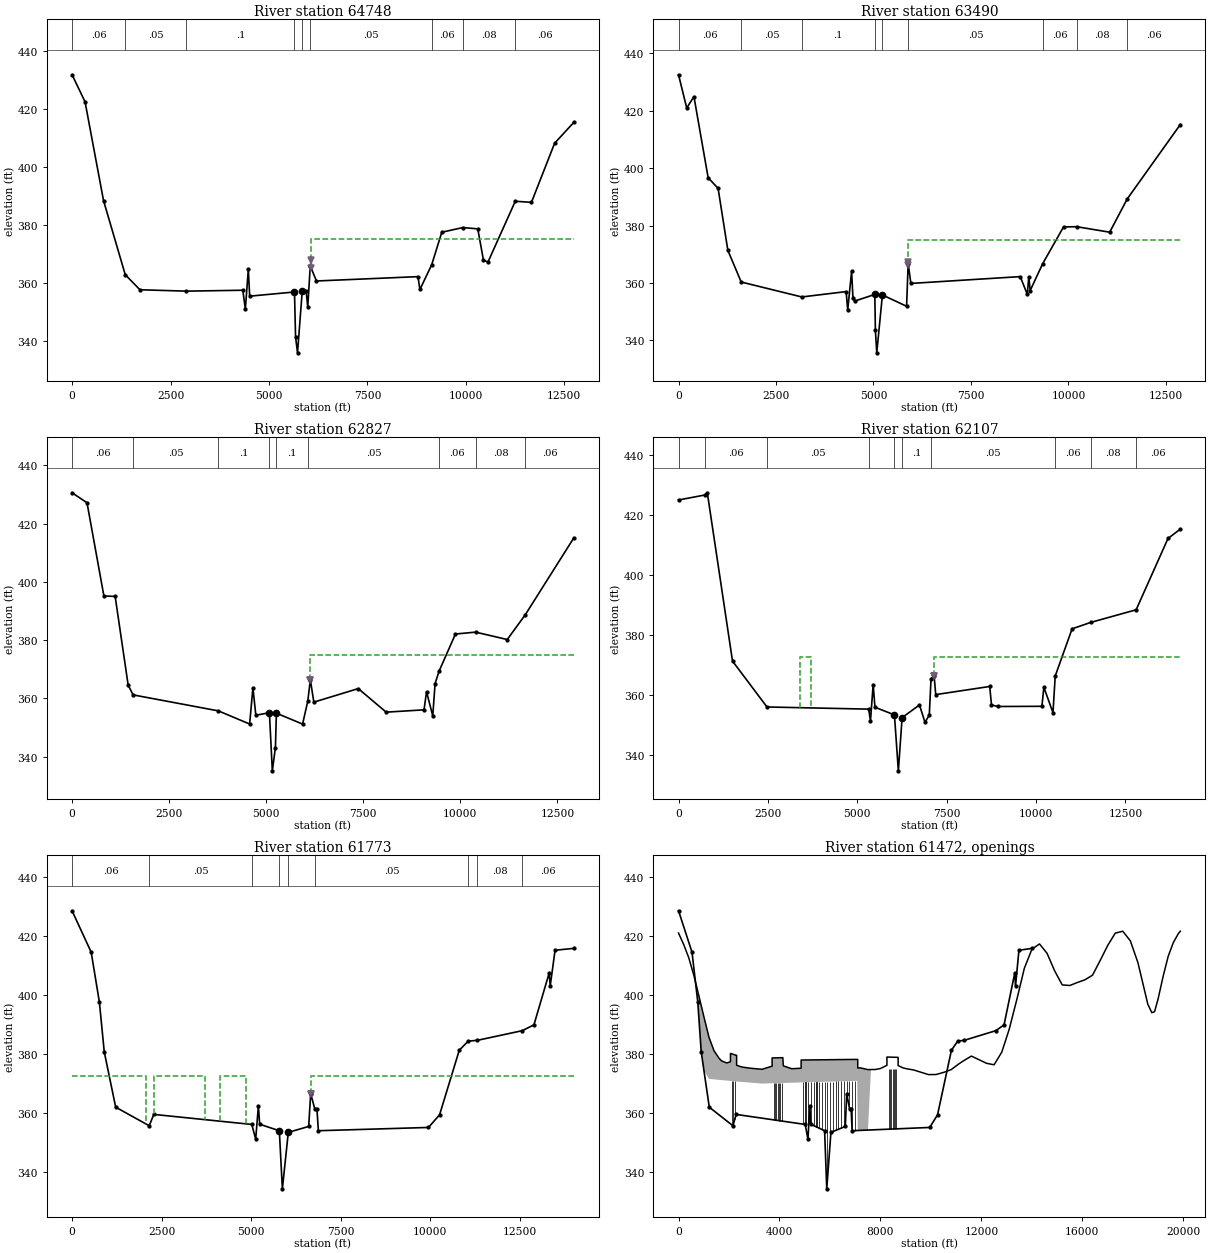
Type RM Length L Ch R = 1 ,64748   ,1485.94,1258.36,388.27
BEGIN DESCRIPTION:
ROB - Kaufman LID10
END DESCRIPTION:
XS GIS Cut Line= 5
2593534.358247736925267.657997982590784.831594566924883.80279456
2587155.986490066923404.924190642582493.076524566923110.03665707
2581136.122545566923335.29932989
#Sta/Elev= 30
       0  431.73  329.55  422.42   798.9  388.36 1350.37  362.81 1722.64  357.62
 2900.35  357.14 4335.63  357.45  4400.6  350.99 4475.58  364.62 4510.56  355.41
 5648.22  356.85 5675.12  341.43  5725.1  335.87 5845.05  357.18 5945.01  357.03
    5985   351.6 6048.89  365.87 6204.92  360.64 8783.47  362.14 8833.44  357.71
 9133.62  366.27 9388.11  377.44 9922.23  379.0610302.58  378.6110447.49  367.78
10562.42  367.1911254.62  388.1211665.99  387.7612254.09  408.1412742.51  415.34
#Mann= 9 ,-1 , 0
       0     .06       0 1350.37     .05       0 2900.35      .1       0
 5648.22    .045       0 5845.05      .1       0 6048.89     .05       0
 9133.62     .06       0 9922.23     .08       011254.62     .06       0
Levee=0,,,-1,6069.97,367.73,,
#XS Ineff= 2 , 0
       0                 6069.97       0     375
Permanent Ineff=
       F       F
Bank Sta=5648.22,5845.05
XS Rating Curve= 0 ,0
Exp/Cntr=0.3,0.1

Type RM Length L Ch R = 1 ,63490   ,807.88,662.89,436.52
BEGIN DESCRIPTION:
ROB - Kaufman LID10
END DESCRIPTION:
XS GIS Cut Line= 5
2593933.663879566923913.491414982590188.802274816923115.88999181
2584451.816373476922944.351949072582493.237613476922968.49396114
2581170.844917066923196.41050006
#Sta/Elev= 30
       0  432.54  209.94  420.96  394.88  424.94  759.77  396.67  1014.7  392.98
 1264.62   371.4 1607.43  360.36 3161.18  355.16 4298.83  357.03 4338.82  350.59
 4438.81  364.14 4473.81  354.65 4518.81  353.72 5033.76  356.05 5048.76  343.51
 5083.75   335.7 5228.74  355.86 5848.68  351.92 5889.26  366.81 5958.67  359.87
 8763.46  362.25 8943.46   356.1 8983.46  362.23 9018.46  357.39 9337.22   366.7
 9873.28  379.5410209.89  379.6311057.58  377.7211507.35   389.312869.15  415.22
#Mann= 9 ,-1 , 0
       0     .06       0 1607.43     .05       0 3161.18      .1       0
 5033.76    .045       0 5228.74      .1       0 5889.26     .05       0
 9337.22     .06       010209.89     .08       011507.35     .06       0
Levee=0,,,-1,5893.68,367.28,,
#XS Ineff= 2 , 0
       0                 5893.68       0     375
Permanent Ineff=
       F       F
Bank Sta=5033.76,5228.74
XS Rating Curve= 0 ,0
Exp/Cntr=0.3,0.1

Type RM Length L Ch R = 1 ,62827   ,933.3,720.09,426.45
BEGIN DESCRIPTION:
ROB - Kaufman LID10
END DESCRIPTION:
XS GIS Cut Line= 4
2594063.871952476922793.699691312590222.728059966922330.61728415
2582458.835123236922834.600528152581205.567288556923074.88252789
#Sta/Elev= 30
       0  430.59   384.9  427.17  819.78  395.17  1109.7  395.02 1444.61   364.6
 1571.64  361.22 3769.35  355.73 4573.52  351.22 4658.47  363.65 4733.42  354.24
 5083.21  355.09 5158.16  335.15 5238.11  343.15  5263.1  354.94 5937.68   351.2
 6071.76   359.1 6137.56  366.42  6227.5  358.73  7371.8  363.38 8091.36  355.29
 9065.78  356.09 9130.75  362.29 9290.65  354.01 9350.62   365.1 9454.11  369.38
 9875.31  382.1110394.37  382.7611209.53  380.22   11675  388.7412925.27  415.13
#Mann= 9 ,-1 , 0
       0     .06       0 1571.64     .05       0 3769.35      .1       0
 5083.21    .045       0  5263.1      .1       0 6071.76     .05       0
 9454.11     .06       010394.37     .08       0   11675     .06       0
Levee=0,,,-1,6137.56,366.42,,
#XS Ineff= 2 , 0
       0                 6137.56       0     375
Permanent Ineff=
       F       F
Bank Sta=5083.21,5263.1
XS Rating Curve= 0 ,0
Exp/Cntr=0.3,0.1

Type RM Length L Ch R = 1 ,62107   ,347.84,334.05,325.77
BEGIN DESCRIPTION:
ROB - Kaufman LID10
END DESCRIPTION:
XS GIS Cut Line= 5
2595053.455275136921161.755120562590342.430904556921429.73555572
2584311.848149466922553.571234552582467.506693816922728.78577915
2581162.16448823 6922979.3964984
#Sta/Elev= 30
       0  424.87  732.47  426.52  804.77  427.27 1509.56  371.22 2473.35  355.93
 5318.47  355.21 5368.56  351.33 5443.56   363.4 5493.55  355.85 6038.49  353.29
 6148.48  334.66 6253.47  352.39 6738.42   356.6  6893.4  350.81 7013.39  353.24
 7062.29   365.3 7148.37  366.41 7193.37  360.05 8703.23  362.76 8753.22  356.64
 8923.21  356.0910163.13  356.1510218.12  362.48 10473.1  354.0210535.91  366.26
11007.88  381.9611525.04  384.0812799.03   388.313690.13  412.0514034.93  415.17
#Mann= 10 ,-1 , 0
       0     .05       0  732.47     .06       0 2473.35     .05       0
 5318.47      .1       0 6038.49    .045       0 6253.47      .1       0
 7062.29     .05       010535.91     .06       011525.04     .08       0
12799.03     .06       0
Levee=0,,,-1,7148.37,366.41,,
#XS Ineff= 2 ,-1
 3388.51 3718.61   372.5 7148.3714034.93   372.5
Permanent Ineff=
       F       F
Bank Sta=6038.49,6253.47
XS Rating Curve= 0 ,0
Exp/Cntr=0.5,0.3

Type RM Length L Ch R = 1 ,61773   ,508.19,534.06,519.89
BEGIN DESCRIPTION:
US Bridge
ROB - Kaufman LID10
END DESCRIPTION:
XS GIS Cut Line= 3
2594662.83040021 6920562.79700092593532.223081386920487.75253156
2580875.706071636922875.23004006
#Sta/Elev= 30
       0  428.56   534.1  414.49  763.72  397.49  898.49  380.69 1218.09  361.88
 2154.83  355.58 2283.07  359.43  5018.7  356.02 5127.99  351.03 5202.99   362.4
 5237.99   356.1 5787.97  353.88 5872.96  334.16 6037.96  353.33 6607.94  355.34
 6662.93  366.49 6781.16  361.16 6837.93  361.41 6877.93  353.89 9952.87     355
10262.87  359.2910812.87  381.2211062.84   384.311319.55  384.5812573.11  387.86
12897.87  389.8313322.87  407.4113352.87  403.0813487.87  415.1614012.87   415.8
#Mann= 9 ,-1 , 0
       0     .06       0 2154.83     .05       0  5018.7      .1       0
 5787.97    .045       0 6037.96      .1       0 6781.16     .05       0
11062.84     .06       011319.55     .08       012573.11     .06       0
Levee=0,,,-1,6662.93,366.49,,
#XS Ineff= 4 ,-1
       0    2065   372.5    2295    3715   372.5    4140    4860   372.5
 6662.9314012.87   372.5
Permanent Ineff=
       F       F       F       F
Bank Sta=5787.97,6037.96
XS Rating Curve= 0 ,0
Exp/Cntr=0.5,0.3

Type RM Length L Ch R = 4 ,61472   ,,,
BEGIN DESCRIPTION:
HWY 175 - bridge deck outside surveyed area is cut from LiDAR of road
END DESCRIPTION:
Node Name=HWY 175
Bridge Culvert--1,0,-1,-1, 0
Deck Dist Width WeirC Skew NumUp NumDn MinLoCord MaxHiCord MaxSubmerge Is_Ogee
175,120,2.6,0, 94, 94, , , 0.98, 0, 0,0,,
       0 204.976 404.952 604.928 804.9041004.8811204.8571404.8331604.8091704.797
1904.7741909.773  2057.4  2057.4  2076.1  2076.1  2282.7  2282.7  2301.4  2301.4
2304.7262504.7022704.6782904.6553304.607  3707.4  3707.4  3726.1  4132.7  4132.7
  4151.44484.467  4857.4  4858.1  4876.1  4923.1  6985.6  7082.6  7100.7  7101.4
7204.1447504.1087804.0728004.049  8257.4  8257.4  8276.1  8682.7  8682.7  8701.4
  8701.48903.9419103.9189303.8959603.8589903.82310203.7910503.7510803.7211103.68
11303.6611603.6211903.5812203.5512503.5112808.4813103.4413403.4113703.3714003.34
 14303.314603.2614903.2315203.1915503.1615803.1216103.0916403.0516703.0117002.98
17302.9417602.9117902.8718202.8418402.8118592.7918752.7718862.7619002.7419202.72
19402.6919602.6719802.6519882.64
 421.001 417.084 412.615 406.701 399.748 392.595  385.67 381.063 378.495 377.603
 376.906 376.903   377.3   380.1   380.1   380.1   379.5   379.5   379.5   376.7
 376.099 375.537 375.265 375.067 374.746   375.8   378.6   378.6   378.7   378.7
   375.9 374.942   375.1   377.9   377.9   377.9   378.1   378.1   378.1   375.2
 375.233  374.64 374.681  375.02   376.1   378.9   378.9   378.8   378.8   378.8
     376 375.184 374.823 374.546 373.749 372.948 372.968 373.688 374.637 376.561
 377.688  379.23  378.01 376.778 376.275 380.578 388.367 398.429 409.064 415.546
 417.301 414.095 408.164 403.401 403.192 404.217 405.123 406.688 411.622 416.742
 420.958 421.616  418.34 410.937 403.759 396.886 393.967  394.32 398.668 406.362
  413.12 417.717 420.789 421.627
                                           372.1   371.5
                                                           370.6   370.6
                                   369.9     370   370.3     370
                                                   370.8   370.8
       0 204.976 404.952 604.928 804.9041004.8811204.8571404.8331604.8091704.797
1904.7741909.773  2057.4  2057.4  2076.1  2076.1  2282.7  2282.7  2301.4  2301.4
2304.7262504.7022704.6782904.6553304.607  3707.4  3707.4  3726.1  4132.7  4132.7
  4151.44484.467  4857.4  4858.1  4876.1  4923.1  6985.6  7082.6  7100.7  7101.4
7204.1447504.1087804.0728004.049  8257.4  8257.4  8276.1  8682.7  8682.7  8701.4
  8701.48903.9419103.9189303.8959603.8589903.82310203.7910503.7510803.7211103.68
11303.6611603.6211903.5812203.5512503.5112808.4813103.4413403.4113703.3714003.34
 14303.314603.2614903.2315203.1915503.1615803.1216103.0916403.0516703.0117002.98
17302.9417602.9117902.8718202.8418402.8118592.7918752.7718862.7619002.7419202.72
19402.6919602.6719802.6519882.64
 421.001 417.084 412.615 406.701 399.748 392.595  385.67 381.063 378.495 377.603
 376.906 376.903   377.3   380.1   380.1   380.1   379.5   379.5   379.5   376.7
 376.099 375.537 375.265 375.067 374.746   375.8   378.6   378.6   378.7   378.7
   375.9 374.942   375.1   377.9   377.9   377.9   378.1   378.1   378.1   375.2
 375.233  374.64 374.681  375.02   376.1   378.9   378.9   378.8   378.8   378.8
     376 375.184 374.823 374.546 373.749 372.948 372.968 373.688 374.637 376.561
 377.688  379.23  378.01 376.778 376.275 380.578 388.367 398.429 409.064 415.546
 417.301 414.095 408.164 403.401 403.192 404.217 405.123 406.688 411.622 416.742
 420.958 421.616  418.34 410.937 403.759 396.886 393.967  394.32 398.668 406.362
  413.12 417.717 420.789 421.627
                                           372.1   371.5
                                                           370.6   370.6
                                   369.9     370   370.3     370
                                                   370.8   370.8
Pier Skew, UpSta & Num, DnSta & Num=  ,2126.09, 2 ,2126.09, 2 , 0 , 0 , 0 ,,
     2.5     2.5
       0     375
     2.5     2.5
       0     375
Pier Skew, UpSta & Num, DnSta & Num=  ,2176.09, 2 ,2176.09, 2 , 0 , 0 , 0 ,,
     2.5     2.5
       0     375
     2.5     2.5
       0     375
Pier Skew, UpSta & Num, DnSta & Num=  ,2226.09, 2 ,2226.09, 2 , 0 , 0 , 0 ,,
     2.5     2.5
       0     375
     2.5     2.5
       0     375
Pier Skew, UpSta & Num, DnSta & Num=  ,3777.09, 2 ,3777.09, 2 , 0 , 0 , 0 ,,
     2.5     2.5
       0     375
     2.5     2.5
       0     375
Pier Skew, UpSta & Num, DnSta & Num=  ,3828.09, 2 ,3828.09, 2 , 0 , 0 , 0 ,,
     2.5     2.5
       0     375
     2.5     2.5
       0     375
Pier Skew, UpSta & Num, DnSta & Num=  ,3879.09, 2 ,3879.09, 2 , 0 , 0 , 0 ,,
     2.5     2.5
       0     375
     2.5     2.5
       0     375
Pier Skew, UpSta & Num, DnSta & Num=  ,3930.09, 2 ,3930.09, 2 , 0 , 0 , 0 ,,
     2.5     2.5
       0     375
     2.5     2.5
       0     375
Pier Skew, UpSta & Num, DnSta & Num=  ,3981.09, 2 ,3981.09, 2 , 0 , 0 , 0 ,,
     2.5     2.5
       0     375
     2.5     2.5
       0     375
Pier Skew, UpSta & Num, DnSta & Num=  ,4032.09, 2 ,4032.09, 2 , 0 , 0 , 0 ,,
     2.5     2.5
       0     375
     2.5     2.5
       0     375
Pier Skew, UpSta & Num, DnSta & Num=  ,4083.09, 2 ,4083.09, 2 , 0 , 0 , 0 ,,
     2.5     2.5
       0     375
     2.5     2.5
       0     375
Pier Skew, UpSta & Num, DnSta & Num=  ,4923.09, 2 ,4923.09, 2 , 0 , 0 , 0 ,,
       3       3
       0     372
       3       3
       0     372
Pier Skew, UpSta & Num, DnSta & Num=  ,5031.65, 2 ,5031.65, 2 , 0 , 0 , 0 ,,
       3       3
       0     372
       3       3
       0     372
Pier Skew, UpSta & Num, DnSta & Num=  ,5140.21, 2 ,5140.21, 2 , 0 , 0 , 0 ,,
       3       3
       0     372
       3       3
       0     372
Pier Skew, UpSta & Num, DnSta & Num=  ,5248.77, 2 ,5248.77, 2 , 0 , 0 , 0 ,,
       3       3
       0     372
       3       3
       0     372
Pier Skew, UpSta & Num, DnSta & Num=  ,5357.33, 2 ,5357.33, 2 , 0 , 0 , 0 ,,
       3       3
       0     372
       3       3
       0     372
Pier Skew, UpSta & Num, DnSta & Num=  ,5465.89, 2 ,5465.89, 2 , 0 , 0 , 0 ,,
       3       3
       0     372
       3       3
       0     372
Pier Skew, UpSta & Num, DnSta & Num=  ,5574.45, 2 ,5574.45, 2 , 0 , 0 , 0 ,,
       3       3
       0     372
       3       3
       0     372
Pier Skew, UpSta & Num, DnSta & Num=  ,5683.01, 2 ,5683.01, 2 , 0 , 0 , 0 ,,
       3       3
       0     372
       3       3
       0     372
Pier Skew, UpSta & Num, DnSta & Num=  ,5791.57, 2 ,5791.57, 2 , 0 , 0 , 0 ,,
       3       3
       0     372
       3       3
       0     372
Pier Skew, UpSta & Num, DnSta & Num=  ,5900.13, 2 ,5900.13, 2 , 0 , 0 , 0 ,,
       3       3
       0     372
       3       3
       0     372
Pier Skew, UpSta & Num, DnSta & Num=  ,6008.69, 2 ,6008.69, 2 , 0 , 0 , 0 ,,
       3       3
       0     372
       3       3
       0     372
Pier Skew, UpSta & Num, DnSta & Num=  ,6117.25, 2 ,6117.25, 2 , 0 , 0 , 0 ,,
       3       3
       0     372
       3       3
       0     372
Pier Skew, UpSta & Num, DnSta & Num=  ,6225.81, 2 ,6225.81, 2 , 0 , 0 , 0 ,,
       3       3
       0     372
       3       3
       0     372
Pier Skew, UpSta & Num, DnSta & Num=  ,6334.37, 2 ,6334.37, 2 , 0 , 0 , 0 ,,
       3       3
       0     372
       3       3
       0     372
Pier Skew, UpSta & Num, DnSta & Num=  ,6442.93, 2 ,6442.93, 2 , 0 , 0 , 0 ,,
       3       3
       0     372
       3       3
       0     372
Pier Skew, UpSta & Num, DnSta & Num=  ,6551.49, 2 ,6551.49, 2 , 0 , 0 , 0 ,,
       3       3
       0     372
       3       3
       0     372
Pier Skew, UpSta & Num, DnSta & Num=  ,6660.05, 2 ,6660.05, 2 , 0 , 0 , 0 ,,
       3       3
       0     372
       3       3
       0     372
Pier Skew, UpSta & Num, DnSta & Num=  ,6768.61, 2 ,6768.61, 2 , 0 , 0 , 0 ,,
       3       3
       0     372
       3       3
       0     372
Pier Skew, UpSta & Num, DnSta & Num=  ,6877.17, 2 ,6877.17, 2 , 0 , 0 , 0 ,,
       3       3
       0     372
       3       3
       0     372
Pier Skew, UpSta & Num, DnSta & Num=  ,6985.6, 2 ,6985.6, 2 , 0 , 0 , 0 ,,
       3       3
       0     372
       3       3
       0     372
Pier Skew, UpSta & Num, DnSta & Num=  ,8327.09, 2 ,8327.09, 2 , 0 , 0 , 0 ,,
     2.5     2.5
       0     375
     2.5     2.5
       0     375
Pier Skew, UpSta & Num, DnSta & Num=  ,8378.09, 2 ,8378.09, 2 , 0 , 0 , 0 ,,
     2.5     2.5
       0     375
     2.5     2.5
       0     375
Pier Skew, UpSta & Num, DnSta & Num=  ,8429.09, 2 ,8429.09, 2 , 0 , 0 , 0 ,,
     2.5     2.5
       0     375
     2.5     2.5
       0     375
Pier Skew, UpSta & Num, DnSta & Num=  ,8480.09, 2 ,8480.09, 2 , 0 , 0 , 0 ,,
     2.5     2.5
       0     375
     2.5     2.5
       0     375
Pier Skew, UpSta & Num, DnSta & Num=  ,8531.09, 2 ,8531.09, 2 , 0 , 0 , 0 ,,
     2.5     2.5
       0     375
     2.5     2.5
       0     375
Pier Skew, UpSta & Num, DnSta & Num=  ,8582.09, 2 ,8582.09, 2 , 0 , 0 , 0 ,,
     2.5     2.5
       0     375
     2.5     2.5
       0     375
Pier Skew, UpSta & Num, DnSta & Num=  ,8633.09, 2 ,8633.09, 2 , 0 , 0 , 0 ,,
     2.5     2.5
       0     375
     2.5     2.5
       0     375
Abutment Skew #Up #Dn= , 2 , 2
  2076.1  2116.1
   372.1     355
  2076.1  2116.1
   372.1     355
Abutment Skew #Up #Dn= , 2 , 2
 2238.07  2282.7
  354.86   371.5
 2238.07  2282.7
  354.86   371.5
Abutment Skew #Up #Dn= , 2 , 2
  3726.1  3766.1
   370.6  355.49
  3726.1  3766.1
   370.6  355.49
Abutment Skew #Up #Dn= , 2 , 2
  4092.7  4132.7
   355.2   370.6
  4092.7  4132.7
   354.3   370.6
Abutment Skew #Up #Dn= , 2 , 2
  4876.1  4911.4
   369.9  355.25
  4876.1  4911.4
   369.9  355.25
Abutment Skew #Up #Dn= , 2 , 2
  7045.2  7082.6
  353.77     370
  7045.2  7082.6
  353.77     370
Abutment Skew #Up #Dn= , 2 , 2
  8276.1  8316.1
   370.8   354.2
  8276.1  8316.1
   370.8   354.2
Abutment Skew #Up #Dn= , 2 , 2
  8642.7  8682.7
     355   370.8
  8642.7  8682.7
     355   370.8
BR Coef=-1 , 0 , 0 ,, 0 ,,,0.8,-1,,0,
WSPro=,,,, 1 ,,,, 0 ,,,, 0 ,,,,-1 ,-1 ,-1 , 0 , 0 , 0 , 0 , 0
BC Mult= 3 ,0,3715,0,3715
BC Mult= 3 ,2295,4860,2295,4860
BC Mult= 3 ,4140,8257,4145,8265
BC Mult= 3 ,7100,14012.87,7100,17543.94
BR U #Sta/Elev= 490
       0  428.56   14.97  428.23   34.94  428.31   119.8  427.55  139.76  426.97
  154.74  427.24  174.71  426.69  189.68  426.89  214.64  426.55  224.62  425.82
  244.59  423.09  249.58  423.08  269.55  424.55   299.5  424.39  319.46  423.05
  344.42  422.65  364.39  422.04  369.38   421.5  449.24  418.67  484.19  416.54
  494.17  416.47   534.1  414.49  559.06  412.92  574.04  411.48  589.01  410.99
  598.99   409.9  618.96  409.04  648.91  406.81  673.87  404.44  683.85  403.97
  718.79  401.07  728.77  400.54  763.72  397.49   773.7  395.98  798.66   394.2
  808.64  392.92  823.61  391.82  858.56  387.15  873.53  384.72  883.51  383.61
  898.49  380.69  913.46  379.64  928.44  379.43  943.41  378.72  968.37   376.4
  978.35  376.49  998.32  375.58  1008.3  374.25 1028.27  372.57 1058.22   371.2
 1073.19  369.74 1088.17  369.09 1103.14  367.94 1143.09   365.7 1183.09  363.69
 1198.09  363.31 1218.09  361.88 1238.09  361.41 1263.09  360.46 1288.09  360.32
 1308.09   359.5 1368.09  358.38 1408.09  357.89 1438.09  358.11 1468.09  357.53
 1543.09  356.37 1558.08  356.73 1698.08  355.72 1733.08  355.97 1758.08  355.66
 1823.08   355.7 1843.08   355.4 1913.08  355.51 1963.08  354.79 2003.08  355.55
 2048.07  355.16 2063.07  354.65 2078.07  355.25 2113.07  355.27 2154.83  355.58
 2183.07  355.61 2208.07  355.36 2228.07  354.52 2248.07  355.05 2263.07   357.6
 2283.07  359.43 2303.07  356.12 2313.07  355.37 2353.07   355.9 2418.07  355.58
 2493.07  355.93 2553.06  355.81 2668.06  355.95 2768.06  355.87 2868.06  355.99
 2913.06  355.61 2973.06  355.72 3043.06  354.95 3053.05  355.35 3058.05  356.33
 3073.05  357.37 3103.05  357.39 3118.05  356.68 3148.05  355.89 3183.05  355.63
 3203.05  355.73 3253.05  355.47 3273.05  355.58 3298.05  355.02 3323.05  355.37
 3373.05  355.71 3478.05  355.32 3508.05  354.76 3548.05  354.77 3583.04   355.3
 3603.04  355.13 3643.04  355.37 3683.04  355.21 3693.04   354.6 3713.04  354.47
 3728.04  355.15 3738.04  355.04 3763.04  355.49 3803.04  355.24 3848.04  355.26
 3878.04  355.52 3913.04  355.56 3933.04  355.25 3998.04   355.4 4013.04  354.92
 4028.04   355.4 4073.03  355.44 4128.03  354.96 4208.03  355.23 4218.03  355.55
 4238.03  355.37 4258.03  354.77 4278.03  354.74 4293.03  355.16 4368.02  355.44
 4438.02  355.26 4473.02  355.64 4513.02  355.21 4553.02  355.41 4588.02  355.19
 4643.01  355.69 4663.01  355.61 4678.01  355.18 4723.01  355.21 4803.01  355.54
    4873  355.46    4898  355.55    4923  355.15    4933  355.44    4958  355.13
    4983  355.32    4993   354.9    5003  355.63  5018.7  356.02    5028  354.73
    5038     352    5048  351.96    5068  353.92    5088  354.46    5098  353.75
    5108  352.17 5127.99  351.03 5147.99  354.45 5162.99  355.42 5172.99     357
 5182.99  360.11 5192.99  362.02 5202.99   362.4 5207.99  361.82 5227.99  356.91
 5237.99   356.1 5267.99  356.35 5292.99  356.02 5312.99  355.31 5332.99  355.55
 5337.99  355.12 5367.98  355.68 5392.98  355.85 5402.98  355.36 5422.98  355.74
 5447.98  355.59 5517.98  355.99 5542.98  355.68 5552.98  356.25 5562.98  355.97
 5582.98   356.1 5607.98  354.85 5627.97  354.82 5667.97  353.77 5682.97  354.36
 5717.97  354.93 5747.97  355.16 5772.97  354.83 5787.97  353.88 5792.97  352.55
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BR U #Mann= 9
       0     .06 2154.83     .05  5018.7      .1 5787.97    .045 6037.96      .1
 6781.16     .0511062.84     .0611319.55     .0812573.11     .06
BR D #Sta/Elev= 483
       0  424.68   29.98   424.5   59.96  423.94   84.94  423.92  104.93  424.43
  124.92  424.48   154.9  423.75  199.87  423.21  284.81  424.07  344.77  424.37
  429.71  424.03  464.69  422.92  494.67  421.48  524.65  420.42  574.62  419.07
  614.59  417.48  719.52  412.12  754.27  410.18  794.47  406.24  824.45  403.83
  874.42  401.59  929.38  397.32  959.36  394.84  984.35  392.48 1024.32  388.34
 1029.32  388.07  1054.3  383.09 1079.28  380.09 1094.27   377.6 1109.26  376.61
 1124.25  377.25 1134.25  379.17 1154.23  377.22 1164.23  378.56 1174.22  378.55
 1184.21   376.6  1204.2  374.12 1314.13  367.11 1369.09  364.01 1419.05  361.65
 1474.02  360.04    1504  359.49 1518.99  358.67 1563.97  358.36 1588.97  360.33
 1628.97  360.15 1638.97  358.76 1648.97  358.31 1723.97  357.78 1738.97  358.09
 1748.97  358.93 1788.97   359.1 1833.97  359.94 1858.97  359.55 1873.97  360.26
 1898.97  359.78 1903.97  360.16 1923.96  359.81 1963.96  360.38 1983.96  360.08
 2013.96  359.17 2028.96  359.47 2098.96  359.04 2118.96  359.31 2128.96  359.92
 2153.96  358.75 2163.96  359.02 2180.49  358.62 2208.96  357.58 2238.96  358.02
 2263.96  357.77 2288.96   358.8 2338.96  359.11 2348.96  359.65 2378.96  359.27
 2393.96  359.62 2418.96  359.46 2448.96  358.58 2488.96  358.15 2498.96  356.77
 2513.96  355.69 2528.96   357.5 2558.96   357.9 2583.96  358.65 2598.96  359.92
 2613.96  359.64 2633.96  360.19 2648.96  361.33 2678.96  361.57 2693.95  360.62
 2718.95  355.83 2743.95  353.52 2793.95  353.58 2803.95  354.64 2818.95   354.6
 2858.95  355.58 2878.95  355.16 2893.95  357.51 2923.95  358.12 2938.95  356.47
 2963.95  354.38 2983.95   353.7 3033.95  354.83 3063.95  354.44 3123.95  354.19
 3148.95  354.71 3168.95  354.41 3183.95  355.12 3198.95  355.03 3213.95   355.5
 3243.95   355.8 3263.95   355.7 3298.95  356.31 3318.95  355.81 3338.95  358.44
 3348.95  358.11 3358.95  355.65 3393.95  355.67 3418.95  356.26 3443.95  355.84
 3528.94  356.12 3583.94  355.66 3653.94  355.91 3673.94  355.65 3738.94  355.78
 3773.94  355.18 3793.94  355.54 3838.94  355.03 3858.94   355.4 3883.94     355
 3928.94  355.53 3938.94  354.83 3954.08   354.8 3983.94  354.14 4018.94  354.61
 4043.94  354.54 4073.94  353.84 4113.94  355.07 4143.94  355.43 4158.94  355.23
 4168.94  355.67 4203.94  355.46 4268.94  356.01 4313.94  355.98 4358.94   355.5
 4388.94  355.72 4403.94  355.46 4478.94  355.41 4498.94  355.69 4548.94  355.69
 4578.94  355.88 4663.94  355.63 4703.94  355.82 4808.94  355.75 4828.94   355.5
 4888.94  355.86 4948.94  355.75 4973.94  355.53 5173.94  356.15 5208.94  355.99
 5278.94  354.83 5283.94  354.13 5293.94  351.08 5308.94  349.16 5313.94  349.56
 5333.94  354.01 5348.94  355.19 5358.94  357.83 5368.94  361.54 5378.94   362.3
 5393.94  360.61 5408.94  357.16 5428.94  355.74 5458.94  355.96 5478.94  355.19
 5493.94  355.89 5503.94  355.49 5523.94  355.85 5553.94  355.11 5568.94  355.71
 5593.94  355.83 5608.94  355.39 5673.94  355.88 5683.94  355.55 5693.94   356.5
 5703.94  356.37 5713.94  355.14 5728.94  354.57 5748.94  354.38 5763.94  353.16
 5788.94  353.08 5813.94  353.44 5823.94   353.1 5848.94  353.51 5858.94  353.26
 5883.94  353.71 5893.94  352.86 5928.94  353.77 5938.94  354.96 5964.02  353.91
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BR D #Mann= 10
       0     .07  754.27     .06 2180.49     .05 3954.08      .1 5964.02    .035
 6129.55      .1 6856.56     .05   13561     .0615671.59     .0517286.68     .07
BC Design=,, 0 ,, 0 ,,,,,,
BC Use User HTab Curves=0
BC User HTab FreeFlow(D)= 0

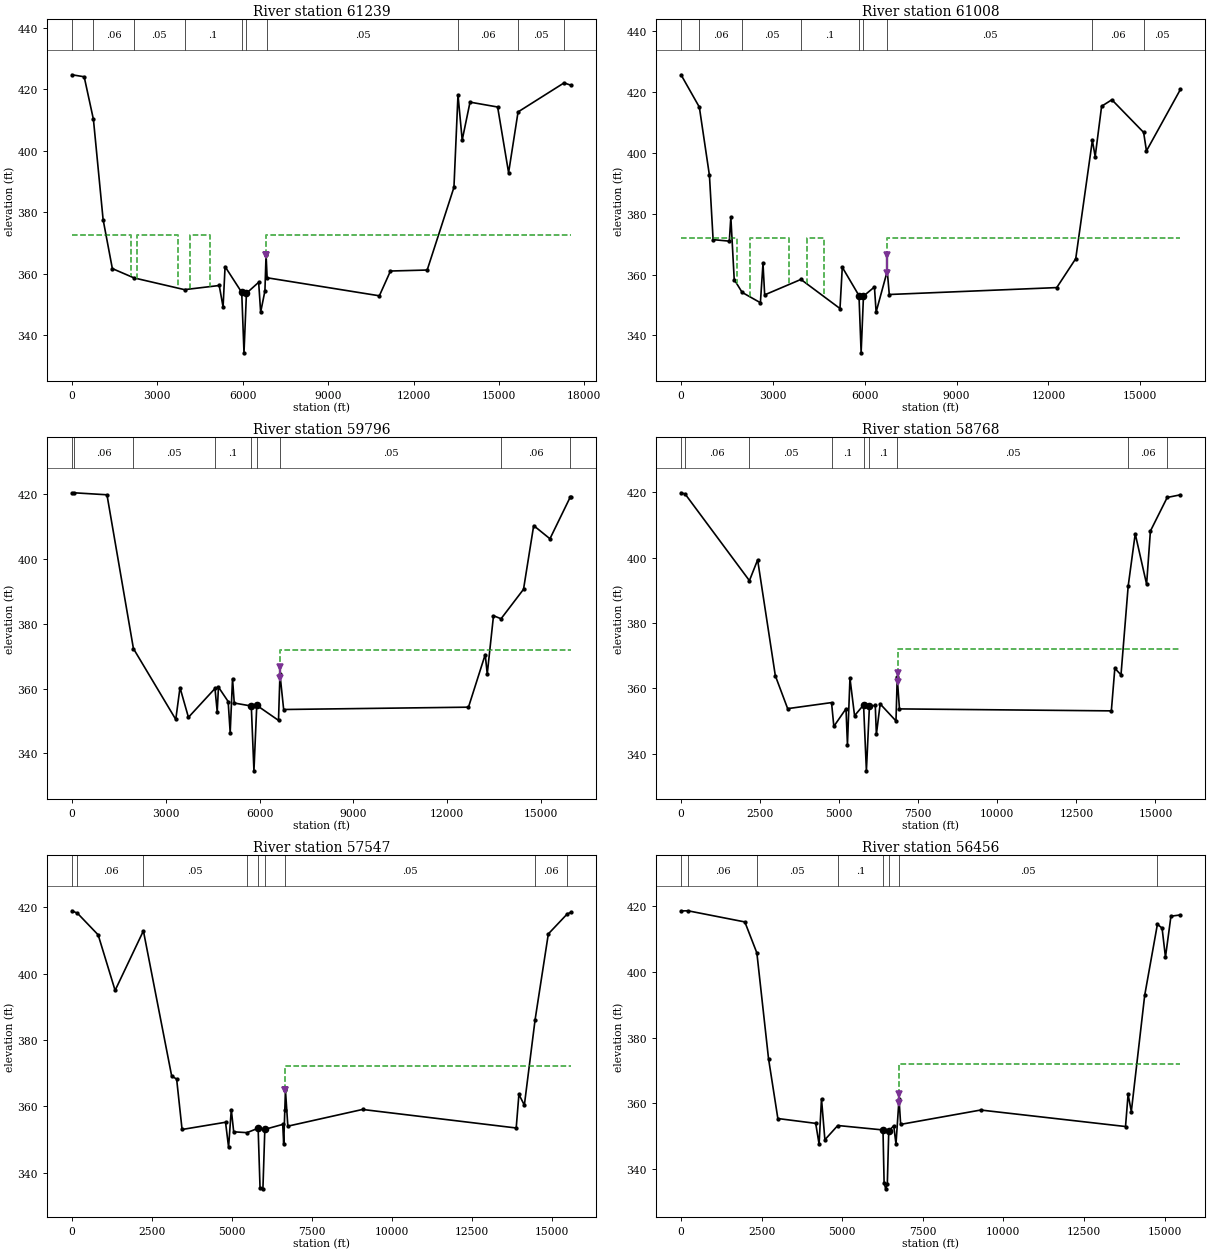
Type RM Length L Ch R = 1 ,61239   ,231.81,230.66,231.9
BEGIN DESCRIPTION:
DS Bridge
ROB - Kaufman LID10
END DESCRIPTION:
XS GIS Cut Line= 3
2594565.608153726919547.172063652593109.176027226920059.67431948
2577378.631044816922982.72752848
#Sta/Elev= 30
       0  424.68  429.71  424.03  754.27  410.18 1094.27   377.6 1419.05  361.65
 2180.49  358.62 3954.08   354.8 5173.94  356.15 5308.94  349.16 5378.94   362.3
 5964.02  353.91 6043.79  334.25 6129.55  353.63 6558.94  357.19 6628.94  347.46
 6778.94   354.4 6818.94  366.23 6856.56  358.6610798.94   352.811188.94  360.86
12478.94  361.1813418.94  388.06   13561  418.1713708.94  403.4613983.94  415.78
14953.94   414.215338.94  392.8315671.59   412.617286.68  422.0417543.94  421.23
#Mann= 10 ,-1 , 0
       0     .07       0  754.27     .06       0 2180.49     .05       0
 3954.08      .1       0 5964.02    .045       0 6129.55      .1       0
 6856.56     .05       0   13561     .06       015671.59     .05       0
17286.68     .07       0
Levee=0,,,-1,6818.94,366.23,,
#XS Ineff= 4 ,-1
       0    2065   372.5    2295    3715   372.5    4145    4860   372.5
 6818.9417543.94   372.5
Permanent Ineff=
       F       F       F       F
Bank Sta=5964.02,6129.55
XS Rating Curve= 0 ,0
Exp/Cntr=0.5,0.3

Type RM Length L Ch R = 1 ,61008   ,1142.5,1211.73,1352.69
BEGIN DESCRIPTION:
ROB - Kaufman LID10
END DESCRIPTION:
XS GIS Cut Line= 3
2594336.441617316919286.755261642593052.01341188 6919836.3673514
2578387.745824476922559.55055331
#Sta/Elev= 30
       0  425.67   597.9  415.05  928.06  392.58 1047.81   371.5 1577.08     371
 1627.08  378.88 1737.08  358.39 1996.36  354.16 2592.07  350.77 2677.07  363.66
 2732.07  353.35 3916.25  358.42 5192.04  348.86 5267.04  362.42 5812.14  353.11
 5882.48   334.3 5958.82  352.94 6317.03  355.94 6372.03  347.71 6736.21  361.17
 6802.02  353.47   12272  355.74   12892  365.2513435.23  404.11   13527  398.79
   13737  415.33   14072  417.4615109.12  406.74   15202  400.65   16312  420.88
#Mann= 9 ,-1 , 0
       0     .07       0   597.9     .06       0 1996.36     .05       0
 3916.25      .1       0 5812.14    .045       0 5958.82      .1       0
 6736.21     .05       013435.23     .06       015109.12     .05       0
Levee=0,,,-1,6717.02,366.29,,
#XS Ineff= 4 ,-1
       0 1828.11     372 2264.67 3529.53     372  4104.3 4662.68     372
 6717.02   16312     372
Permanent Ineff=
       F       F       F       F
Bank Sta=5812.14,5958.82
XS Rating Curve= 0 ,0
Exp/Cntr=0.3,0.1

Type RM Length L Ch R = 1 ,59796   ,966.46,1028.06,1097.97
BEGIN DESCRIPTION:
ROB - Kaufman LID10
END DESCRIPTION:
XS GIS Cut Line= 2
2594279.149737136918630.505261812578471.192179896920887.38263781
#Sta/Elev= 30
       0  420.43   63.08  420.49 1119.88  419.87 1965.58  372.35 3319.63  350.46
 3454.62  360.29 3724.59  351.11 4573.28  360.03 4644.49  352.85 4684.49  360.45
 4994.46     356 5059.45  346.36 5134.44  363.07 5189.44  355.53 5734.38  354.61
 5818.88  334.58 5909.37  354.82  6604.3  350.17 6651.09  364.47 6769.28  353.53
12678.61  354.2513213.55   370.513278.54  364.5113478.52  382.5113720.39  381.57
14438.41  390.6714763.37  410.3515283.31  406.28 15933.3  419.1815968.22  419.16
#Mann= 9 ,-1 , 0
       0     .07       0   63.08     .06       0 1965.58     .05       0
 4573.28      .1       0 5734.38    .045       0 5909.37      .1       0
 6651.09     .05       013720.39     .06       0 15933.3     .05       0
Levee=0,,,-1,6664.29,366.53,,
#XS Ineff= 2 ,-1
                         6664.2915968.22     372
Permanent Ineff=
       F       F
Bank Sta=5734.38,5909.37
XS Rating Curve= 0 ,0
Exp/Cntr=0.3,0.1

Type RM Length L Ch R = 1 ,58768   ,995.35,1220.81,1240.8
BEGIN DESCRIPTION:
ROB - Kaufman LID10
END DESCRIPTION:
XS GIS Cut Line= 3
2594331.233294386917927.380355732591470.356470216918107.56076965
2578627.442195486919550.57724056
#Sta/Elev= 30
       0  419.81  129.38  419.44 2162.04  392.95 2422.08   399.3 2981.54  363.89
 3371.51  353.83 4758.75  355.68 4831.38  348.41 5216.35  353.81 5261.35   342.8
 5341.34  363.13 5486.33  351.67  5771.3  354.96  5860.8  334.82 5956.29  354.55
 6141.27   354.8 6176.27  345.96 6296.26  355.27 6796.21  350.07 6835.42  363.37
  6906.2  353.75 13605.3  353.1513715.28  366.1513910.25  364.1714137.73   391.3
14360.18  407.2714720.13  391.8614840.11  408.1115371.36  418.3815789.97  419.19
#Mann= 9 ,-1 , 0
       0     .07       0  129.38     .06       0 2162.04     .05       0
 4758.75      .1       0  5771.3    .045       0 5956.29      .1       0
 6835.42     .05       014137.73     .06       015371.36     .05       0
Levee=0,,,-1,6846.21,364.63,,
#XS Ineff= 1 ,-1
 6846.2115789.97     372
Permanent Ineff=
       F
Bank Sta=5771.3,5956.29
XS Rating Curve= 0 ,0
Exp/Cntr=0.3,0.1

Type RM Length L Ch R = 1 ,57547   ,837.69,1091.62,1276.98
BEGIN DESCRIPTION:
ROB - Kaufman LID10
END DESCRIPTION:
XS GIS Cut Line= 5
2594326.024971476917661.755230812591898.227989816917634.89307982
2588885.705799646917144.938679142588193.448982066917317.00920114
2578809.733825646918100.92429997
#Sta/Elev= 30
       0  418.98  171.57  418.24  819.31  411.71 1348.86  394.95 2233.37  412.92
 3117.28  369.11 3272.13   368.2 3441.97  352.99 4800.67  355.17 4895.57  347.66
 4980.49  358.98 5055.42  352.29 5469.52  352.03 5819.22  353.37 5879.08  335.35
 5968.87  335.08 6028.73  353.03  6588.2  354.52 6618.19  348.63 6653.62  358.95
 6673.17  364.84 6748.15  353.99 9082.28  359.03 13885.4  353.4413970.37  363.58
 14140.3  360.33 14476.1  386.1214890.01     41215485.07  418.0715609.73  418.52
#Mann= 9 ,-1 , 0
       0     .07       0  171.57     .06       0 2233.37     .05       0
 5469.52      .1       0 5819.22    .045       0 6028.73      .1       0
 6653.62     .05       0 14476.1     .06       015485.07     .05       0
Levee=0,,,-1,6673.17,364.84,,
#XS Ineff= 1 ,-1
 6673.1715609.73     372
Permanent Ineff=
       F
Bank Sta=5819.22,6028.73
XS Rating Curve= 0 ,0
Exp/Cntr=0.3,0.1

Type RM Length L Ch R = 1 ,56456   ,1050.99,1649.02,1533
BEGIN DESCRIPTION:
ROB - Kaufman LID10
END DESCRIPTION:
XS GIS Cut Line= 5
2594336.441617316917515.921861072592019.932142726917189.06621556
 2588521.1225393 6916124.10509092587948.01082464 6916251.7918434
2579038.787501386916385.50515865
#Sta/Elev= 30
       0  418.48  214.12  418.53 1979.53  415.14 2352.61  405.73 2714.17  373.65
 3003.95  355.42 4178.08  353.95    4283  347.63 4357.95  361.42 4462.87  348.97
 4862.76   353.3 6265.43  351.95 6300.26  335.86 6350.02  334.06 6399.78  335.47
 6444.57  351.62 6598.88  353.22 6668.84  347.66 6763.26  361.36 6813.76  353.64
 9297.36     35813789.86  352.9913869.82  362.7813969.76  357.5314384.53  392.83
14779.46  414.4414924.23  413.2515029.17  404.4415199.08  416.8815493.92  417.27
#Mann= 8 ,-1 , 0
       0     .07       0  214.12     .06       0 2352.61     .05       0
 4862.76      .1       0 6265.43    .045       0 6444.57      .1       0
 6763.26     .05       014779.46     .06       0
Levee=0,,,-1,6753.8,362.83,,
#XS Ineff= 1 ,-1
  6753.815493.92     372
Permanent Ineff=
       F
Bank Sta=6265.43,6444.57
XS Rating Curve= 0 ,0
Exp/Cntr=0.3,0.1

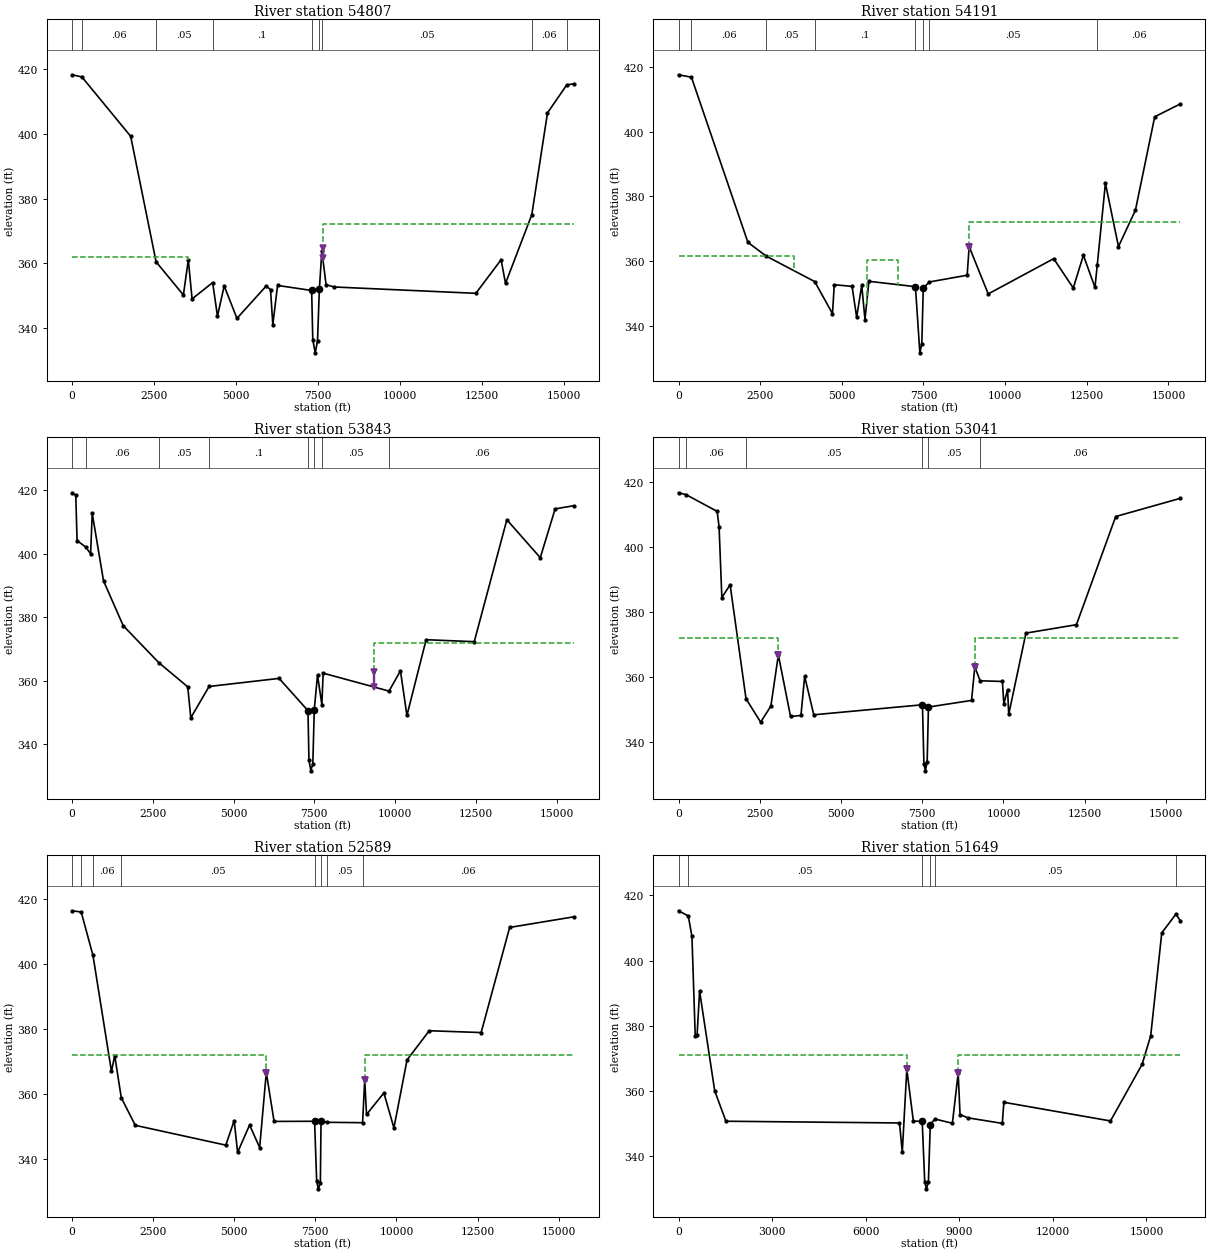
Type RM Length L Ch R = 1 ,54807   ,343.73,615.72,961.48
BEGIN DESCRIPTION:
ROB - Kaufman LID10
LOB IFA Station 3546.4: flow contraction due to natural high ground
END DESCRIPTION:
XS GIS Cut Line= 4
2594361.759808146917054.116354232592180.812398396916601.35708915
2588073.222844566914846.860926232579461.964476566914605.99132922
#Sta/Elev= 30
       0  418.24  299.19  417.58 1787.96  399.24 2563.43  360.47 3396.56  350.22
 3546.44  361.09 3661.36  349.02 4288.79  354.05 4435.77   343.7 4640.62  353.04
 5030.33  343.01 5924.66  353.02 6054.56  351.86 6124.51  341.07  6269.4  353.18
 7309.04  351.62 7344.04  336.42 7419.04  332.36 7489.03  336.14 7544.03  351.93
 7620.78  363.83 7749.02  353.42    7994   352.712318.99  350.7413088.99  361.11
13223.99  353.8114025.72  375.0214503.99  406.4515091.26  415.1115308.99  415.45
#Mann= 9 ,-1 , 0
       0     .07       0  299.19     .06       0 2563.43     .05       0
 4288.79      .1       0 7309.04    .045       0 7544.03      .1       0
 7620.78     .05       014025.72     .06       015091.26     .05       0
Levee=0,,,-1,7649.02,364.66,,
#XS Ineff= 2 ,-1
       0  3546.4     362 7649.0215308.99     372
Permanent Ineff=
       F       F
Bank Sta=7309.04,7544.03
XS Rating Curve= 0 ,0
Exp/Cntr=0.5,0.3

Type RM Length L Ch R = 1 ,54191   ,340.54,347.69,879.16
BEGIN DESCRIPTION:
ROB - Kaufman LID10
LOB IFA Station 3531.8: flow contraction due to natural high ground upstream
LOB IFA Station 5759-6715: flow contraction due to natural high ground downstream
END DESCRIPTION:
XS GIS Cut Line= 4
2594417.912911066916815.486582152592178.329463726916341.52821247
2586841.523864396913971.736364142579640.135051976913270.34767506
#Sta/Elev= 30
       0  417.47  394.86  416.72 2124.25  365.88 2684.15  361.65 4168.99  353.81
 4713.93  343.94 4768.92  352.85 5313.86  352.32 5453.85  342.83 5608.83  352.64
 5708.82  342.13 5828.81  353.89 7253.65  352.24 7388.64  331.87 7448.63  334.68
 7493.63  351.85 7683.61  353.69 8838.14  355.77 8898.11  364.57 9482.76  350.01
11486.59  360.8612086.24  351.8312396.06  361.9112750.85  352.0112820.81  358.88
13070.66  384.0813470.43  364.5913990.12   375.814579.78  404.5415364.32   408.5
#Mann= 8 ,-1 , 0
       0     .07       0  394.86     .06       0 2684.15     .05       0
 4168.99      .1       0 7253.65    .045       0 7493.63      .1       0
 7683.61     .05       012820.81     .06       0
Levee=0,,,-1,8898.11,364.57,,
#XS Ineff= 3 ,-1
       0  3531.8   361.6    5759    6715   360.5 8898.1115364.32     372
Permanent Ineff=
       F       F       F
Bank Sta=7253.65,7493.63
XS Rating Curve= 0 ,0
Exp/Cntr=0.5,0.3

Type RM Length L Ch R = 1 ,53843   ,1413.54,802.88,201.58
BEGIN DESCRIPTION:
ROB - Kaufman LID10
END DESCRIPTION:
XS GIS Cut Line= 4
2594458.982054646916640.921970652592239.655128466916177.40550923
2585711.877173566913031.572233972579776.634450886912001.82462156
#Sta/Elev= 30
       0  419.28  114.86  418.49  154.81  404.22   417.3  402.23  574.29  400.08
  624.23   412.8   973.8  391.54 1583.05  377.42 2683.57  365.79 3581.54  358.15
 3676.49  348.39 4242.17  358.27 6410.11  360.81 7304.66  350.65 7334.65  335.05
 7394.62  331.69 7454.59     334 7499.57  350.95 7599.52  361.86 7734.38  352.55
 7774.43  362.46 9814.35  356.8110168.32  363.1910368.28  349.1310963.16     373
12452.87  372.3713462.67  410.7814497.47  398.8314957.38  414.2115537.27  415.21
#Mann= 8 ,-1 , 0
       0     .07       0   417.3     .06       0 2683.57     .05       0
 4242.17      .1       0 7304.66    .045       0 7499.57      .1       0
 7734.38     .05       0 9814.35     .06       0
Levee=0,,,-1,9348.54,362.89,,
#XS Ineff= 1 ,-1
 9348.5415537.27     372
Permanent Ineff=
       F
Bank Sta=7304.66,7499.57
XS Rating Curve= 0 ,0
Exp/Cntr=0.8,0.6

Type RM Length L Ch R = 1 ,53041   ,887.56,451.48,215
BEGIN DESCRIPTION:
LOB - Kaufman 5 East, ROB - Kaufman 5 West
END DESCRIPTION:
XS GIS Cut Line= 6
2594327.634876396916055.069795892592563.746015716915687.01442964
2587658.814880716913145.118266732587098.468232396913242.56984347
2585772.079480986912839.792105732579695.69038706 6911825.9030574
#Sta/Elev= 30
       0  416.78   229.6  416.21 1187.94  411.06 1247.84  406.25 1332.69  384.51
 1587.25  388.43 2076.85  353.29 2526.81   346.1 2841.78  351.07 3071.76  366.81
 3446.73  347.85  3766.7  348.16 3881.69  360.21 4161.66  348.37 7505.91  351.46
 7550.82  333.36 7595.72   331.1  7650.6  333.79 7690.52  350.76    9017   352.8
 9116.72  363.14 9281.27  358.85 9965.74  358.64 10010.7  351.7610125.61  356.14
10160.59   348.510690.17  373.5412243.96  376.1313453.01  409.4615441.46  415.07
#Mann= 6 ,-1 , 0
       0     .07       0   229.6     .06       0 2076.85     .05       0
 7505.91    .045       0 7690.52     .05       0 9281.27     .06       0
Levee=-1,3071.76,366.81,-1,9116.72,363.14,,
#XS Ineff= 2 ,-1
       0 3071.76     372 9116.7215441.46     372
Permanent Ineff=
       F       F
Bank Sta=7505.91,7690.52
XS Rating Curve= 0 ,0
Exp/Cntr=0.5,0.3

Type RM Length L Ch R = 1 ,52589   ,1237.78,939.78,994.4
BEGIN DESCRIPTION:
LOB - Kaufman 5 East, ROB - Kaufman 5 West
END DESCRIPTION:
XS GIS Cut Line= 4
2594264.537561646915609.672064652587522.424733556912700.27696481
2586980.75816597 6912825.27704292579505.367276896911622.05044673
#Sta/Elev= 30
       0  416.45  281.37  416.07   644.9  402.67 1214.68  366.92 1314.65  371.83
 1516.82  358.83 1949.48  350.31 4738.75   344.2 4998.68  351.75 5103.65  341.97
 5473.54  350.41 5783.46  343.46  5988.4  366.58 6228.33  351.51 7477.03  351.56
 7541.55  333.01 7591.19  330.73 7655.71   332.6 7675.57  351.66 7872.82  351.24
 8956.65  351.12 9023.46  364.39 9078.43  353.65 9613.22   360.3 9923.09  349.52
10327.92  370.4711012.64  379.4712611.99  378.9113491.63  411.3215470.82  414.59
#Mann= 8 ,-1 , 0
       0     .07       0  281.37     .05       0   644.9     .06       0
 1516.82     .05       0 7477.03    .045       0 7675.57     .05       0
 7872.82     .05       0 8956.65     .06       0
Levee=-1,5988.4,366.58,-1,9023.46,364.39,,
#XS Ineff= 2 ,-1
       0  5988.4     372 9023.4615470.82     372
Permanent Ineff=
       F       F
Bank Sta=7477.03,7675.57
XS Rating Curve= 0 ,0
Exp/Cntr=0.3,0.1

Type RM Length L Ch R = 1 ,51649   ,976.98,1004.9,1121.02
BEGIN DESCRIPTION:
LOB - Kaufman 5 East, ROB - Kaufman 5 West
END DESCRIPTION:
XS GIS Cut Line= 5
2594550.648537966914266.963463982588652.855215486912067.51970014
2587215.985057736911850.876432642586709.924718146911887.77694939
2578983.345026976910609.60496506
#Sta/Elev= 30
       0  415.23  313.12  413.65  429.97  407.36  534.96  376.97  594.96  377.24
  674.95  390.66 1159.92  360.07 1519.89  350.79 7083.55  350.26 7173.43  341.38
 7318.25  366.65 7527.98  350.84 7812.37  350.74 7891.97  332.27 7946.69  330.09
 8011.36   332.3 8071.05  349.79 8218.76  351.47 8779.91  350.17 8964.83  365.51
 9024.81  352.85 9269.72  351.8410379.28  350.1310429.26  356.5913847.93  350.88
14862.53  368.2215137.42  376.9615492.28  408.4715943.32  414.1716087.05  412.22
#Mann= 6 ,-1 , 0
       0     .07       0  313.12     .05       0 7812.37    .045       0
 8071.05     .05       0 8218.76     .05       015943.32     .06       0
Levee=-1,7318.25,366.65,-1,8964.83,365.51,,
#XS Ineff= 2 , 0
       0 7318.25     371 8964.83       0     371
Permanent Ineff=
       F       F
Bank Sta=7812.37,8071.05
XS Rating Curve= 0 ,0
Exp/Cntr=0.3,0.1