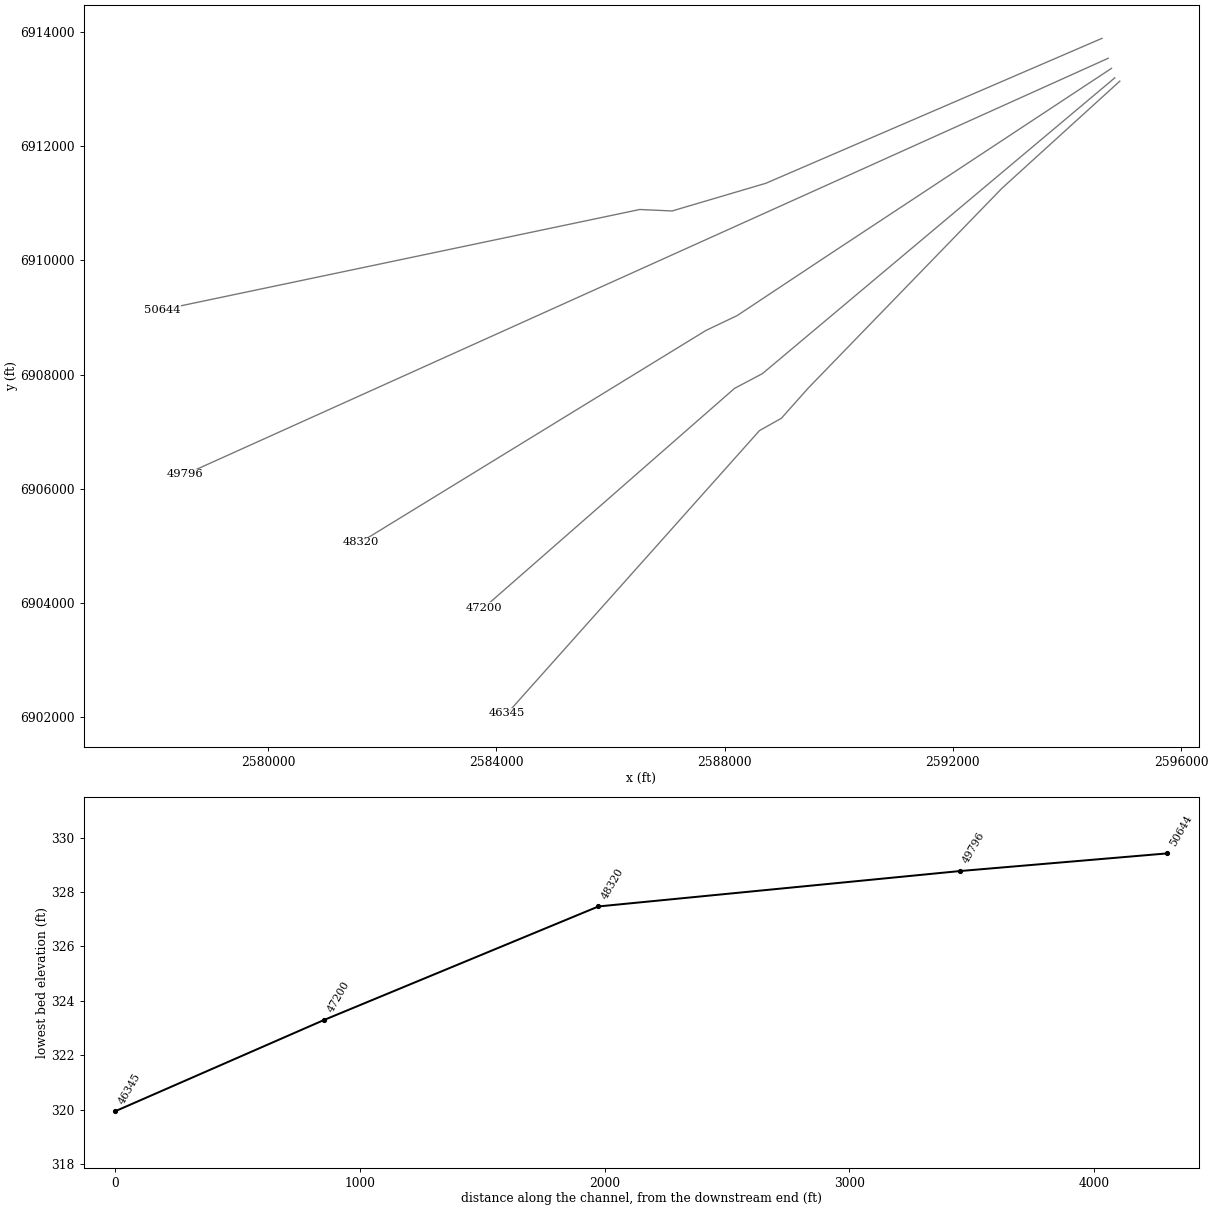
HEC-RAS study EF_FEMA.prj: East_Fork_FEMA

--- EF_FEMA.g06 (geometry) --- (continued)

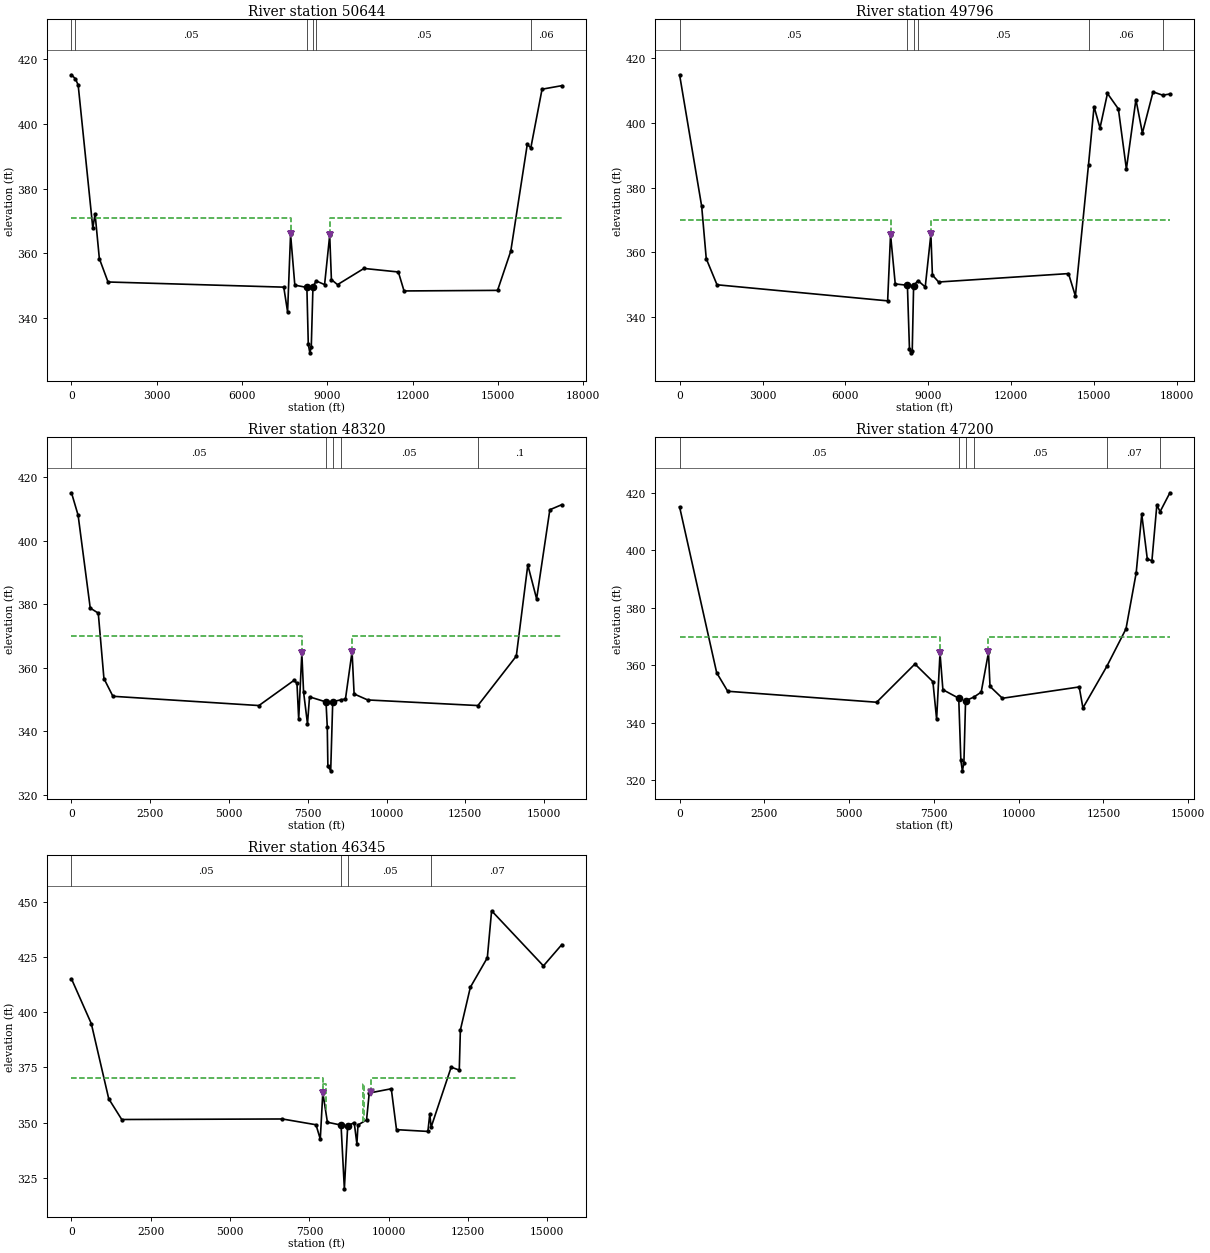
Type RM Length L Ch R = 1 ,50644   ,692.75,848.13,1501.09
BEGIN DESCRIPTION:
LOB - Kaufman 5 East, ROB - Kaufman 5 West
END DESCRIPTION:
XS GIS Cut Line= 5
2594613.148741056913891.96355781 2588721.42922536911351.62054139
2587079.716301386910866.943689232586513.192171986910892.49875623
2578149.030422646909137.24143998
#Sta/Elev= 30
       0  415.01  139.84  413.74  234.86  411.84  749.54  367.84  829.49  372.16
   979.4  358.44 1284.21  351.23 7464.13  349.64 7598.88  342.03 7703.68  365.95
  7853.4  350.26 8277.12  349.55 8326.87  332.07 8381.59  329.42 8431.34  331.13
 8491.03  349.78 8603.38  351.56 8899.91  350.42 9079.84  365.62 9139.82  351.96
 9354.73  350.4110284.37   355.4 11493.9  354.3111693.82  348.4714982.53  348.65
15447.35  360.7416027.12  393.5916151.85  392.5216546.92  410.5717241.65  411.66
#Mann= 6 ,-1 , 0
       0     .07       0  139.84     .05       0 8277.12    .045       0
 8491.03     .05       0 8603.38     .05       016151.85     .06       0
Levee=-1,7703.74,365.94,-1,9079.84,365.62,,
#XS Ineff= 2 , 0
       0 7703.74     371 9079.84       0     371
Permanent Ineff=
       F       F
Bank Sta=8277.12,8491.03
XS Rating Curve= 0 ,0
Exp/Cntr=0.3,0.1

Type RM Length L Ch R = 1 ,49796   ,1452.91,1476.31,1787.04
BEGIN DESCRIPTION:
LOB - Kaufman 5 East, ROB - Kaufman 5 West
END DESCRIPTION:
XS GIS Cut Line= 2
 2594722.52352236913543.005266232578550.505997646906250.95653014
#Sta/Elev= 30
       0  414.94  799.77  374.16  964.73  357.95 1354.62  349.86 7527.86  344.88
 7632.83  365.42 7802.79  350.12 8242.66  349.71 8317.64  329.84 8362.63  328.77
 8417.62  329.43  8467.6   349.6 8625.57  351.16  8887.5  349.18 9092.44  365.52
 9147.43  352.88 9372.37  350.7214071.18  353.3314321.12  346.38 14795.5   387.1
14995.95  405.0815210.89  398.4515480.82  409.1515875.72  404.3616165.65  385.74
16510.54  407.2616745.45  396.88 17130.3  409.6317483.55  408.6117740.06  408.99
#Mann= 6 ,-1 , 0
       0     .05       0 8242.66    .045       0  8467.6     .05       0
 8625.57     .05       0 14795.5     .06       017483.55     .07       0
Levee=-1,7632.84,365.42,-1,9092.44,365.52,,
#XS Ineff= 2 , 0
       0 7632.84     370 9092.44       0     370
Permanent Ineff=
       F       F
Bank Sta=8242.66,8467.6
XS Rating Curve= 0 ,0
Exp/Cntr=0.3,0.1

Type RM Length L Ch R = 1 ,48320   ,1117.07,1120.41,1502.42
BEGIN DESCRIPTION:
LOB - Kaufman 5 East, ROB - Kaufman 5 West
END DESCRIPTION:
XS GIS Cut Line= 5
2594779.815402466913365.921958982589704.538479556910018.63075331
2588220.341316716909033.61041364 2587673.45494336908773.21264048
2581622.233778066905062.72990398
#Sta/Elev= 30
       0  415.16  209.99  408.08  594.97   378.8  849.96  377.21 1029.95  356.57
 1314.93  350.98 5949.71  348.06 7062.67     356 7157.47   355.1 7212.36  343.75
 7312.15  364.63 7367.04  352.38 7491.78  342.27 7556.64   350.8 8079.47   349.2
 8119.19  341.41 8139.05  328.94 8228.42  327.47 8292.96  349.28  8540.6  349.84
 8696.68   350.1 8906.64  365.05 8971.62  351.72 9401.54  349.83 12901.2  348.06
14120.54  363.6614485.46  392.38 14765.4  381.7115185.32  409.8115565.24  411.41
#Mann= 5 ,-1 , 0
       0     .05       0 8079.47    .045       0 8292.96     .05       0
  8540.6     .05       0 12901.2      .1       0
Levee=-1,7312.18,364.63,-1,8906.64,365.05,,
#XS Ineff= 2 , 0
       0 7312.18     370 8906.64       0     370
Permanent Ineff=
       F       F
Bank Sta=8079.47,8292.96
XS Rating Curve= 0 ,0
Exp/Cntr=0.3,0.1

Type RM Length L Ch R = 1 ,47200   ,849.08,854.74,1118.27
BEGIN DESCRIPTION:
LOB - Kaufman 5 East, ROB - Kaufman 5 West
END DESCRIPTION:
XS GIS Cut Line= 4
2594837.106954566913199.255297562588663.692136056908017.22104223
2588173.46641047 6907757.56867442583775.011624726903908.21613689
#Sta/Elev= 30
       0  415.14 1094.33  357.42 1419.13  350.99 5811.45  347.17 6940.76  360.48
 7470.43  354.33 7580.36  341.23  7680.3  364.24 7765.25  351.53 8232.54  348.56
 8294.96  326.94 8339.95   323.3 8384.93  326.08 8434.05   347.7 8676.88  348.95
 8894.84  350.69 9109.84   364.5 9154.84  352.67 9519.84  348.5511784.84  352.49
11894.84  345.1912598.24  359.6313164.84   372.713464.84  392.1113629.84  412.57
13794.84  396.8713929.84  396.4714074.84  415.7714171.05  413.4814459.84  420.05
#Mann= 6 ,-1 , 0
       0     .05       0 8232.54    .045       0 8434.05     .05       0
 8676.88     .05       012598.24     .07       014171.05      .1       0
Levee=-1,7680.23,364.24,-1,9109.84,364.5,,
#XS Ineff= 2 , 0
       0 7680.23     370 9109.84       0     370
Permanent Ineff=
       F       F
Bank Sta=8232.54,8434.05
XS Rating Curve= 0 ,0
Exp/Cntr=0.5,0.3

Type RM Length L Ch R = 1 ,46345   ,777.22,761,653.03
BEGIN DESCRIPTION:
US Bridge
LOB - Kaufman 5 East, ROB - Kaufman 5 West
END DESCRIPTION:
XS GIS Cut Line= 6
2594925.64877222 6913141.96341742592858.618785566911263.34611164
2589469.304369976907767.00107023 2588993.98773536907233.66191381
2588610.966519716907017.985507892584191.103968386902062.58859456
#Sta/Elev= 30
       0  415.15  624.59  394.86 1174.23  360.77 1583.96  351.38 6647.79  351.62
 7707.65     349 7842.53  342.49 7922.46  363.58 8067.34  350.14 8496.97  348.85
 8601.87  319.94 8706.76  348.58 8912.49  349.94 8996.52  340.32 9031.49  348.89
 9301.28   351.2 9386.21  363.3910080.67  365.3210245.54  346.7811234.77  345.97
11294.72  353.9111336.75   347.911969.19  375.1312223.99  373.7712258.97  391.98
12573.72  411.36 13108.3  424.72 13243.2  446.0314876.92  421.0415456.47  430.69
#Mann= 4 ,-1 , 0
       0     .05       0 8496.97    .045       0 8706.76     .05       0
11336.75     .07       0
Levee=-1,7922.46,363.58,-1,9441.17,363.87,,
#XS Ineff= 4 ,-1
       0 7922.46     370 7922.46    8018   367.5  9176.9 9212.61   367.5
 9441.17   14000     370
Permanent Ineff=
       F       F       F       F
Bank Sta=8496.97,8706.76
XS Rating Curve= 0 ,0
Exp/Cntr=0.5,0.3