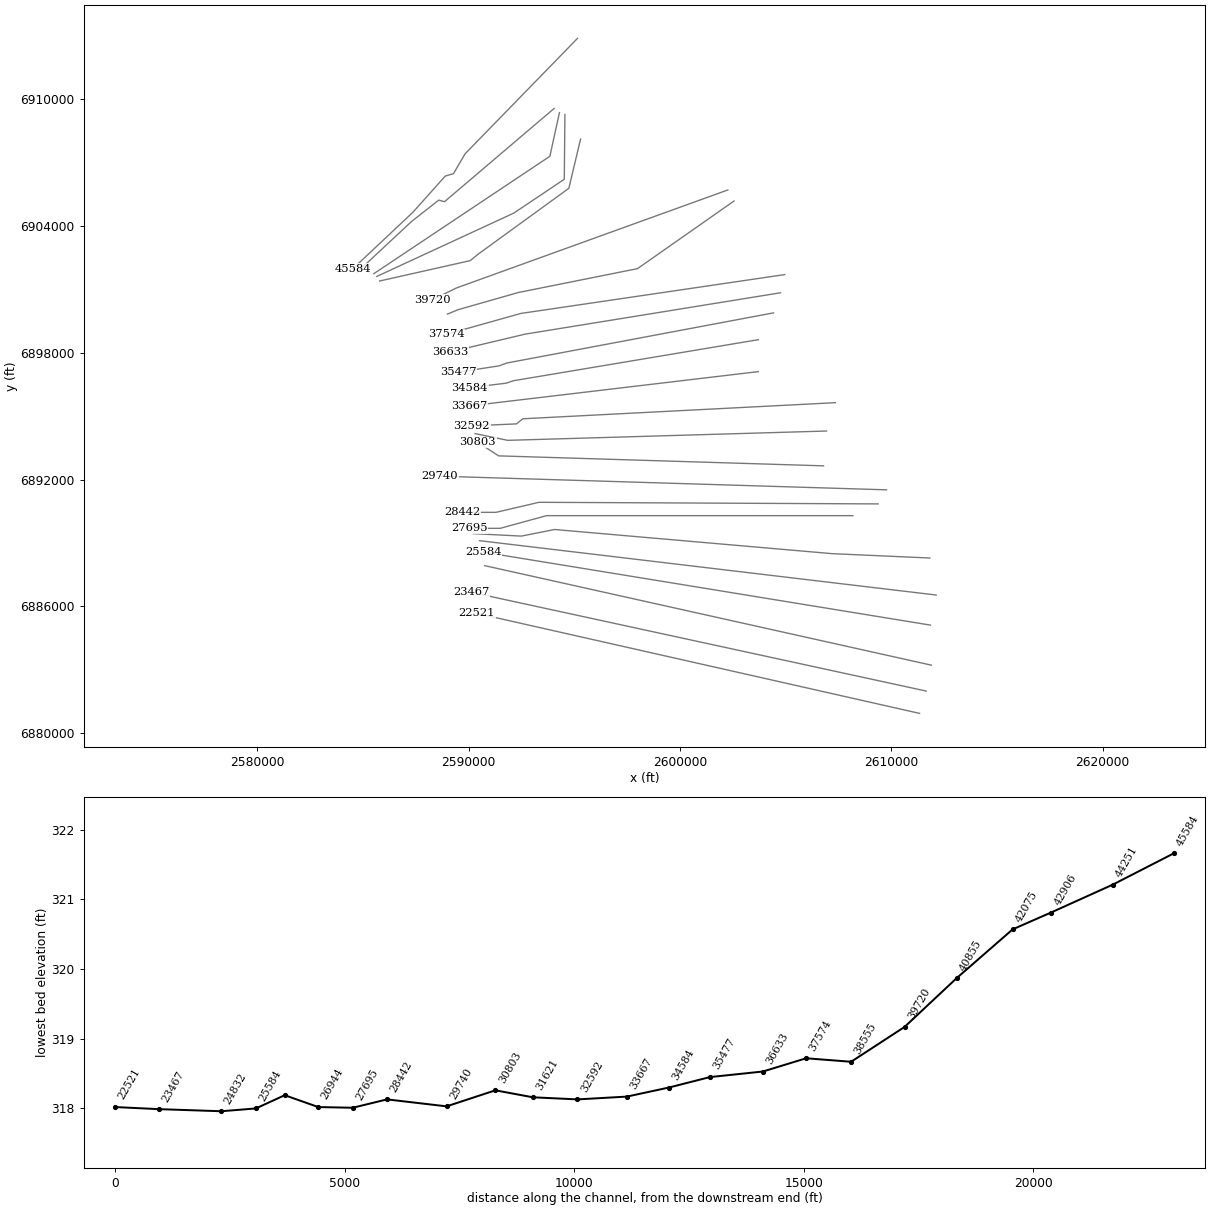
HEC-RAS study EF_FEMA.prj: East_Fork_FEMA

--- EF_FEMA.g06 (geometry) --- (continued)

Type RM Length L Ch R = 4 ,45988   ,,,
BEGIN DESCRIPTION:
FM 3039 - bridge deck outside surveyed area is cut from LiDAR of road
END DESCRIPTION:
Node Name=FM 3039
Bridge Culvert--1,0,-1,-1, 0
Deck Dist Width WeirC Skew NumUp NumDn MinLoCord MaxHiCord MaxSubmerge Is_Ogee
334,43,2.6,0, 52, 52, , , 0.98, 0, 0,0,,
       0 104.975 304.927 499.881 704.832 904.7841104.7361304.6891504.6411704.593
1904.5452104.498 2304.452504.4022904.3073504.1644004.0444303.9734373.9564418.945
 4438.944628.8954998.8076503.4487103.304 7418.42  7446.8 8008.058401.985  8416.8
  8419.1  8419.1  8686.4  8775.8  8775.88886.1579100.695 9400.059604.60910503.89
11003.84 11502.711904.4312504.3313404.2813514.2713704.2114003.4314302.6614801.36
15200.3215434.71
 415.663 414.311 410.054 402.984 394.008 384.643 376.494 367.711  360.76 357.283
  356.63 356.883 356.463   357.4 357.234 357.638 357.684 357.397   356.9 357.059
 357.504 357.912 357.882  356.87 356.864  358.99  359.26 366.034 367.328   367.5
   367.5   367.5   367.5   367.5   367.5 367.145 364.368 357.545 356.937 356.572
 356.571 366.287 379.999 407.747 441.458 443.346 442.039 438.679 434.498 431.011
 429.583 428.988
           363.5   363.9   363.9
       0 104.975 304.927 499.881 704.832 904.7841104.7361304.6891504.6411704.593
1904.5452104.498 2304.452504.4022904.3073504.1644004.0444303.9734373.9564418.945
 4438.944628.8954998.8076503.4487103.304 7418.42  7771.8 8333.058726.985  8741.8
  8744.1  8744.1  9011.4  9100.8  9100.89211.1579425.695 9725.059734.60910503.89
11003.84 11502.711904.4312504.3313404.2813514.2713704.2114003.4314302.6614801.36
15200.3215434.71
 415.663 414.311 410.054 402.984 394.008 384.643 376.494 367.711  360.76 357.283
  356.63 356.883 356.463   357.4 357.234 357.638 357.684 357.397   356.9 357.059
 357.504 357.912 357.882  356.87 356.864  358.99  359.26 366.034 367.328   367.5
   367.5   367.5   367.5   367.5   367.5 367.145 364.368 357.545 356.937 356.572
 356.571 366.287 379.999 407.747 441.458 443.346 442.039 438.679 434.498 431.011
 429.583 428.988
           363.5   363.9   363.9
Pier Skew, UpSta & Num, DnSta & Num=  ,8477.6, 2 ,8802.6, 2 , 0 , 0 , 0 ,,
     2.5     2.5
       0     365
     2.5     2.5
       0     365
Pier Skew, UpSta & Num, DnSta & Num=  ,8557.5, 2 ,8882.5, 2 , 0 , 0 , 0 ,,
     2.5     2.5
       0     365
     2.5     2.5
       0     365
Pier Skew, UpSta & Num, DnSta & Num=  ,8637, 2 ,8962, 2 , 0 , 0 , 0 ,,
     2.5     2.5
       0     365
     2.5     2.5
       0     365
Pier Skew, UpSta & Num, DnSta & Num=  ,8715.4, 2 ,9040.4, 2 , 0 , 0 , 0 ,,
     2.5     2.5
       0     365
     2.5     2.5
       0     365
Abutment Skew #Up #Dn= , 2 , 2
  8419.1  8458.1
   363.5   349.7
  8744.1  8783.1
   363.5  348.73
Abutment Skew #Up #Dn= , 2 , 2
  8736.5  8775.8
     350   363.9
  9061.5  9100.8
     350   363.9
BR Coef=-1 , 0 , 0 ,, 0 ,,,0.8,-1,,0,
WSPro=,,,, 1 ,,,, 0 ,,,, 0 ,,,,-1 ,-1 ,-1 , 0 , 0 , 0 , 0 , 0
Multiple Barrel Culv=2,8,9,69.8,0.013,0.4,1,8,1,345.75,345.86, 3,Culvert #3  , 0 ,228
  4382.4  4406.5  4392.4  4416.5  4402.4  4426.5
BC Culvert Barrel=1,Barrel #1,0
BC Culvert Barrel=2,Barrel #2,0
BC Culvert Barrel=3,Barrel #3,0
Culvert Bottom n=0.013
Multiple Barrel Culv=2,9,9,51.8,0.013,0.4,1,8,1,345.37,345.25, 2,Culvert #1  , 0 ,210
 7440.38 7440.56 7449.77 7450.29
BC Culvert Barrel=1,Barrel #1,0
BC Culvert Barrel=2,Barrel #2,0
Culvert Bottom n=0.013
Multiple Barrel Culv=2,9,10,57.6,0.013,0.4,1,8,1,346.14,346.19, 3,Culvert #2  , 0 ,433
 9682.67 9683.92 9693.28 9694.52 9703.94 9705.19
BC Culvert Barrel=1,Barrel #1,0
BC Culvert Barrel=2,Barrel #2,0
BC Culvert Barrel=3,Barrel #3,0
Culvert Bottom n=0.013
BC Mult= 2 ,0,7425,0,7427
BC Mult= 2 ,4438,8410,4449,8735
BC Mult= 3 ,7465,9665,7465,9665
BC Mult= 2 ,8785,15456.47,9110,15333.25
BR U #Sta/Elev= 493
       0  415.15   54.96  414.79   64.96  414.84  139.91  414.26  184.88  413.56
  219.86  412.32  264.83  409.42  289.81  408.03  334.78  405.73  384.75  403.57
  449.71  401.04  489.68  399.99  564.63  397.28  594.61   395.9  624.59  394.86
  659.57   392.7  689.55  390.59  704.54   389.7  744.51  385.68  774.49  383.93
  809.47  382.25  859.44  378.49  904.41  376.66   919.4   375.8  939.38   374.2
  959.37  371.99  984.35  370.63 1089.29  366.72 1099.28  366.65 1144.25   363.3
 1169.23  361.02 1174.23  360.77  1219.2   359.5 1329.13  355.73 1354.11  355.02
 1414.07  354.05 1464.04  354.54 1489.02  354.22 1514.01  352.67 1553.98  351.99
 1563.97  351.63 1583.96  351.38  1673.9  350.79 1753.85  350.41 1843.79  350.21
 1903.75  349.97 1918.74  349.22 1928.73  350.02 1943.72  350.12 1958.71  349.07
 1973.71  349.79 2008.68  349.87  2138.6  349.53 2238.53  349.58 2328.48  349.76
 2428.41  350.07 2458.39  349.96 2488.37  350.08 2798.18     350 2913.16  349.79
 2973.16  349.82 3083.14  350.19 3208.13  350.06 3268.12  350.24 3363.11  350.21
 3423.11  350.12  3468.1  350.28  3483.1  350.72  3493.1  350.21  3533.1  350.44
 3553.09  350.81 3568.09  350.41 3623.09  350.57 3633.08  350.46 3648.08  349.84
 3728.07  348.71 3803.07  347.08 3818.06  346.62 3858.06  347.47 3888.06  347.95
 3938.05  348.33 3983.05  349.39 4008.04  349.63 4098.03  349.94 4148.03  349.93
 4173.03   349.8 4348.01  349.47 4374.17   345.6  4409.3   345.6  4437.9   349.2
    4478  350.39 4512.99  349.63 4537.99  348.86 4567.99  348.84 4702.98  349.37
 4767.97   349.3 4822.96  349.53 4887.96  349.46 4957.95   348.4 4997.95  349.39
 5017.94  349.54 5067.94  347.96 5102.94  348.95 5112.94  349.09 5172.93  348.72
 5187.93  349.18 5197.93  348.74 5207.93  349.09 5222.92  349.03 5297.92  349.28
 5412.91  348.35  5502.9  348.42 5587.89  348.06 5622.89  347.97 5657.88  346.83
 5702.88  348.21 5717.88  348.11 5767.87   346.7 5772.87  346.66 5832.86  348.51
 5872.86  348.52 5927.86  348.06 5947.85  348.09 5987.85  347.67 6002.85  348.24
 6027.85  347.51 6042.84   347.8 6082.84  347.58 6147.83  347.66 6202.83  347.57
 6257.82  347.72 6327.82  347.61 6372.81  347.61 6407.81  347.85 6427.81  348.25
  6462.8  348.17  6472.8  348.41  6502.8  348.61  6517.8  348.54 6572.79  348.72
 6597.79  349.21 6622.79  350.29 6642.79  351.59 6647.79  351.62 6687.78  350.44
 6702.78  349.71 6712.78  348.58 6722.78   346.9 6732.78  346.05 6752.77  345.88
 6762.77  346.15 6777.77  347.07 6787.77  348.12 6832.77   349.1 6847.77   349.6
 6867.76  349.49 6882.76  349.12 6907.76  349.09 7012.75  349.32 7072.74  349.03
 7192.73     349 7307.72  349.04 7367.71   349.4 7392.71  349.47 7432.71  349.29
 7435.88  345.37 7454.27  345.37 7457.71  349.21 7652.69  348.94 7707.65     349
 7737.62  348.38 7752.61  348.33 7772.59  347.57 7777.59  346.69 7787.58  344.01
 7797.57  342.71 7842.53  342.49 7857.52  344.74 7862.52  346.81  7877.5  350.85
 7887.49  354.06 7902.48  359.66 7912.47     360 7922.46  361.58 7937.45  361.27
 7947.44  360.76 7972.42  356.49  7992.4  353.68 8022.38  351.94 8067.34  350.14
 8102.31  350.04 8137.28  349.75 8152.27  349.83 8192.23  349.74 8212.22  350.27
 8257.18  349.79 8332.12  350.46  8362.1  350.31 8402.06  350.69    8462   349.5
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BR U #Mann= 5
       0     .05 8496.97    .035 8706.76     .05 8912.49     .0511336.75     .07
BR D #Sta/Elev= 457
       0  414.27  179.92     411  264.88     409 304.927 408.054 499.881 400.984
 704.832 392.008 904.784 382.6431104.736 374.4941304.689 365.7111504.641  358.76
1704.593 355.283 1719.24     355 1729.24  354.22 1744.23  354.39 1749.23  354.07
 1779.22  353.58 1834.19  353.02 1934.15  351.63 1969.13  351.07 2019.11  350.67
  2034.1  350.41 2094.08  349.93 2239.02  349.41 2348.97  349.31 2378.95  351.36
 2393.95  349.62 2398.95  349.35 2413.94  349.85 2483.91  348.71  2503.9  348.62
 2538.88  348.96 2613.85  348.97 2673.83  349.19 2713.81  349.23  2723.8  348.86
  2733.8  349.16 2853.75  349.21 2893.73  349.07 2928.72  348.54  2958.7  348.43
 2978.69  348.61 2998.69  348.38 3043.67   348.1 3113.63  348.14 3158.62  347.96
 3178.61  348.22 3223.59  347.94 3313.55  347.97 3368.52  348.13 3458.49     348
 3563.44  348.13 3703.38  347.95 3858.31  347.99 3963.27  348.09 4038.23  347.92
 4143.19  348.09 4193.16   348.3 4283.12  348.33 4308.11  347.85 4318.11  348.05
 4353.09  350.15 4388.07  348.26 4393.07  348.15 4401.85   345.6  4431.5   345.6
  4438.8  349.15 4473.03  349.84 4503.02  349.79    4543  349.23 4562.99   349.4
 4592.98  348.83 4617.97  348.54 4642.96  347.61 4702.93  347.59 4737.91  347.95
  4762.9  348.39 4802.88   348.6 4817.88  348.02 4827.87  348.46 4867.85  348.57
 4907.83  348.09 4952.81  348.45 4967.81  347.84  4982.8  348.36 5002.79     348
 5022.78  348.16 5057.77  348.08 5067.76  347.63 5077.76  347.72 5097.75  348.42
 5107.74  347.86 5117.74  347.92 5127.73  348.44 5147.72  348.22 5162.72  348.42
  5202.7  348.28 5212.69  347.68 5227.69  348.41 5257.67  347.67 5312.65  347.53
 5337.64  347.61 5372.62  347.49  5407.6  348.08 5447.59  347.27 5462.58   347.6
 5477.57  347.06 5512.56  346.75 5527.55  347.08 5542.54  346.61 5582.52  346.98
 5617.51  346.84 5682.48  348.04 5707.47  348.16 5742.45   348.1 5912.37  348.14
 5942.36   348.2 6087.29  347.04 6102.29  347.02 6237.22  347.19 6357.17  346.92
 6397.15   347.1 6487.11  346.87 6537.09  347.03 6602.06  347.38 6687.02   347.5
 6761.98  347.24 6796.97  347.21 6906.92  347.43 6956.89  347.61 7036.86  348.11
 7066.84  348.16 7136.81  348.02  7161.8  348.11 7261.75  347.82 7306.73  347.57
 7426.68  347.67 7436.06  345.25 7454.79  345.29 7456.66  347.79 7486.65  348.01
 7546.62  348.29 7576.61  347.89 7636.58  347.72 7706.52  348.14 7721.51  348.16
 7776.47  348.74  7856.4  348.12 7876.39  347.69 7941.33   346.7 7961.32  346.19
 7971.31  345.62 7996.29  343.28 8006.28  342.75 8011.28  343.03 8021.27  344.54
 8036.26  348.77 8041.25  350.58 8056.24   353.5 8066.23  354.91 8086.22  358.26
 8096.21  360.83  8106.2     361 8121.19     360 8131.18     359 8146.17  358.08
 8156.16  356.46 8176.15  354.84 8206.12  354.29 8256.08  352.88 8296.05  352.84
 8326.03  353.26 8351.01  353.22 8436.37  353.99 8450.93  353.74 8460.92  353.01
 8475.91  350.56 8480.91  350.35 8500.89  351.06 8520.88  349.32 8545.86  349.01
 8555.85  349.59 8565.84  349.15 8575.83  349.54 8585.83  349.15 8595.82  349.46
 8610.81  348.95  8620.8  349.34 8635.79  348.74 8655.77  348.64 8670.76  348.27
 8685.75  349.08 8700.74   348.9 8710.73  349.63 8720.72  348.67 8735.68  348.55
 8755.63  349.36  8765.6  348.78 8780.56  348.68 8800.51     349 8815.47  348.79
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BR D #Mann= 5
       0     .05 8436.37      .1 8823.08    .035 9084.76     .05 11217.9     .07
BC Design=,, 0 ,, 0 ,,,,,,
BC Use User HTab Curves=0
BC User HTab FreeFlow(D)= 0

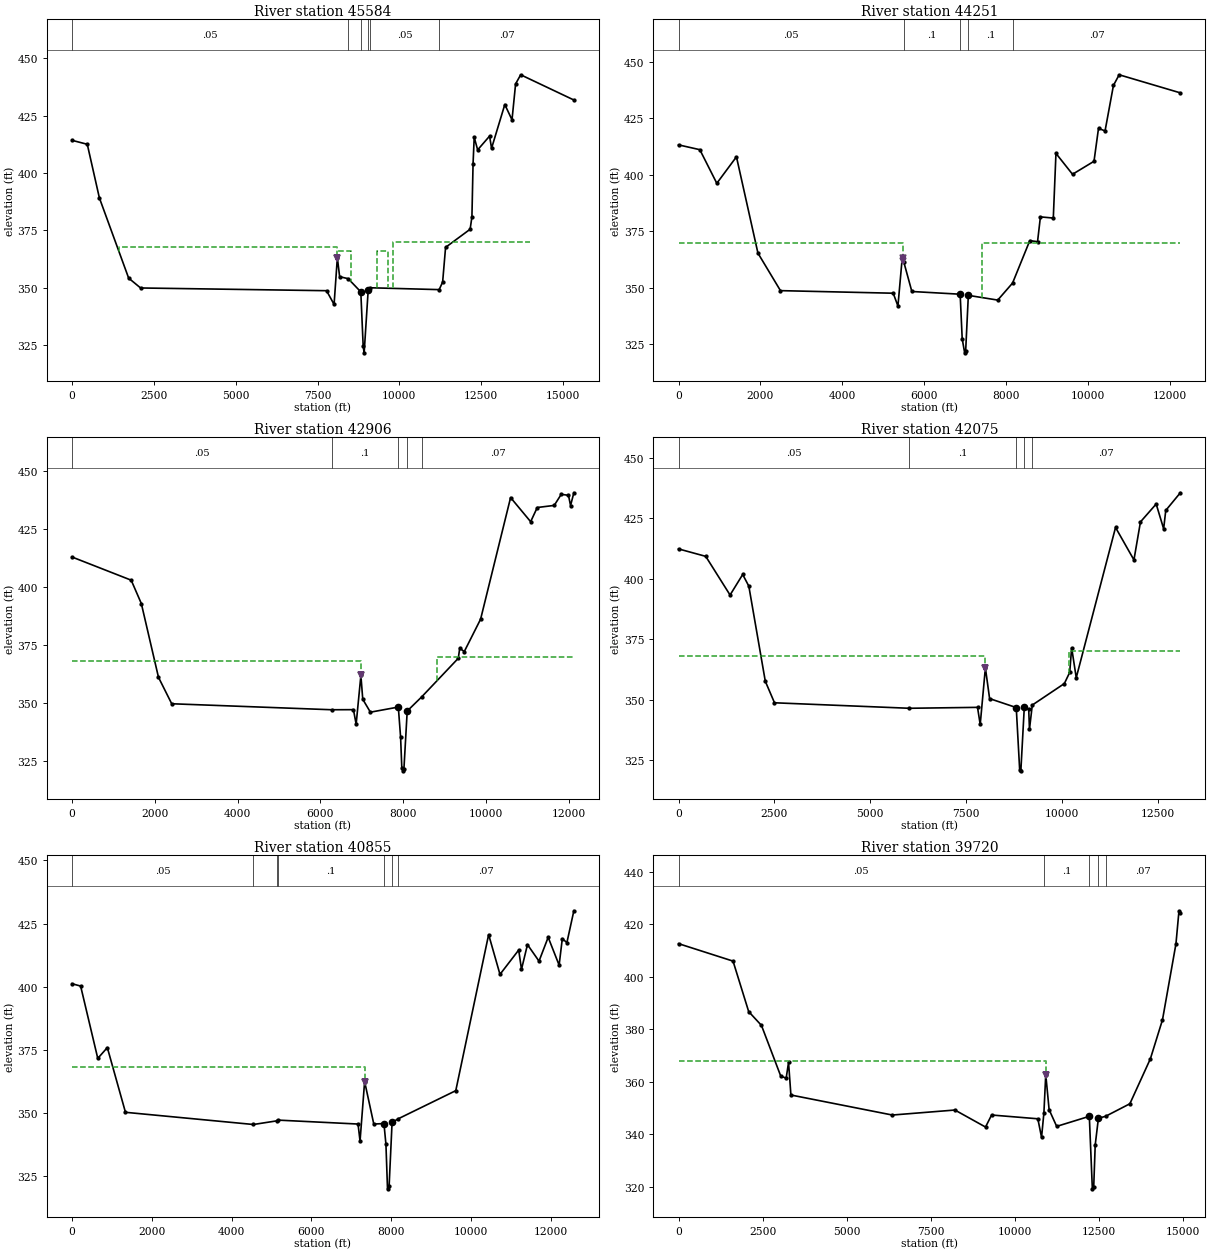
Type RM Length L Ch R = 1 ,45584   ,967.31,1332.53,361.44
BEGIN DESCRIPTION:
DS Bridge
LOB - Kaufman 5 East
ROB IFA station 9792: flow expansion due to Kaufman 5 West levee upstream
END DESCRIPTION:
XS GIS Cut Line= 6
2595154.815308636912891.963589312589835.605474646907426.51093756
2589282.320491976906482.568599732588894.303223396906370.30307622
 2587378.35317136904669.299588472584516.62497088 6901975.7829939
#Sta/Elev= 30
       0  414.27  464.79  412.55  834.63  389.18 1729.24  354.22 2094.08  349.93
 7776.47  348.74 8006.28  342.75  8106.2  363.12 8176.15  354.84 8436.37  353.99
 8823.08  348.23 8895.26  324.59 8925.18  321.66 9048.47  348.95 9106.64  350.02
 11217.9  349.21 11323.3   352.511413.25  367.6212163.25  375.5212218.25  380.88
12253.25  404.1712288.25  415.6112393.25  410.1212758.25  416.1212818.25   410.8
13223.25  429.8713443.25  423.2113553.25  438.8813708.25  442.8415333.25  431.85
#Mann= 6 ,-1 , 0
       0     .05       0 8436.37      .1       0 8823.08    .045       0
 9048.47      .1       0 9106.64     .05       0 11217.9     .07       0
Levee=-1,8106.29,363.12,0,,,,
#XS Ineff= 4 ,-1
    1440 8106.29     368 8106.29    8533     366    9327    9668     366
    9792   14000     370
Permanent Ineff=
       F       F       F       F
Bank Sta=8823.08,9048.47
XS Rating Curve= 0 ,0
Exp/Cntr=0.5,0.3

Type RM Length L Ch R = 1 ,44251   ,1282.65,1345.57,1145.65
BEGIN DESCRIPTION:
LOB - Kaufman 5 East
ROB IFA station 7410: flow expansion due to Kaufman 5 West levee upstream
END DESCRIPTION:
XS GIS Cut Line= 5
2594046.035702056909571.283878982588856.799689476905154.18346123
2588587.650949556905231.111456982587301.419270056904220.50422622
2584722.787944396901813.02249265
#Sta/Elev= 30
       0  413.19  519.97  411.06  934.95  396.19 1414.92  407.91 1939.89   365.3
 2489.86  348.72 5244.72  347.58 5359.71   341.9  5464.7  363.24  5501.6  361.48
 5699.69  348.34  6879.6  347.14 6929.58  327.44 6989.57  321.21 7014.56  322.15
 7079.55  346.63 7797.73  344.54 8160.12  352.07 8580.72  370.83 8770.32  370.38
 8840.28  381.34 9155.09  380.82 9220.05  409.42 9624.81  400.1810149.49  405.93
10259.43   420.510419.33  419.3510624.21  439.4910764.12  444.1912258.23  436.19
#Mann= 5 ,-1 , 0
       0     .05       0  5501.6      .1       0  6879.6    .045       0
 7079.55      .1       0 8160.12     .07       0
Levee=-1,5489.75,363.16,0,,,,
#XS Ineff= 2 ,-1
       0 5489.75     370    7410   14000     370
Permanent Ineff=
       F       F
Bank Sta=6879.6,7079.55
XS Rating Curve= 0 ,0
Exp/Cntr=0.3,0.1

Type RM Length L Ch R = 1 ,42906   ,907.64,831.04,782.67
BEGIN DESCRIPTION:
LOB - Kaufman 5 East
ROB IFA station 8821: flow expansion due to Kaufman 5 West levee upstream
END DESCRIPTION:
XS GIS Cut Line= 3
2594297.772075226909371.631391142593845.622388976907306.79825048
2585514.888722396901747.91862023
#Sta/Elev= 30
       0  412.86 1429.16  402.89 1674.02  392.84 2088.78  361.07 2408.61  349.69
  6275.2  347.11 6801.43  347.15  6866.4  340.89 6981.34  361.89 7026.32  351.62
 7211.23  346.06  7885.9  348.27 7940.87  335.31 7970.86  321.87 7995.85  320.81
 8020.83   321.5 8100.79  346.56 8448.57  352.61 9335.21  369.26  9370.2  373.59
 9480.15  372.16 9874.96  386.1110599.62  438.46 11084.4  428.0711244.32  434.18
11654.13  435.0811824.05  439.8611998.97  439.4312048.95  435.0212128.91  440.52
#Mann= 5 ,-1 , 0
       0     .05       0  6275.2      .1       0  7885.9    .045       0
 8100.79      .1       0 8448.57     .07       0
Levee=-1,6981.34,361.89,0,,,,
#XS Ineff= 2 , 0
       0 6981.34     368    8821       0     370
Permanent Ineff=
       F       F
Bank Sta=7885.9,8100.79
XS Rating Curve= 0 ,0
Exp/Cntr=0.3,0.1

Type RM Length L Ch R = 1 ,42075   ,1066.9,1219.97,1124.41
BEGIN DESCRIPTION:
LOB - Kaufman 5 East
ROB IFA station 10178: flow expansion due to Kaufman 5 West levee upstream
END DESCRIPTION:
XS GIS Cut Line= 4
2594558.188549136909284.82579048 2594527.03572436906218.12949607
2592143.249809476904619.118914562585655.947823466901617.71021923
#Sta/Elev= 30
       0  412.37  709.27  409.29 1343.62   393.3 1673.28  401.79 1833.12  396.96
 2262.68  357.62 2502.44  348.72 6018.52  346.45 7796.83  346.83 7866.81  339.75
 8001.77  363.17 8111.75  350.45 8806.54  346.75 8896.52  320.78 8926.51  320.57
 9016.48  346.92 9131.45  345.99 9151.44  337.76 9224.91  347.7810061.18  356.67
10201.14  361.3110251.12  371.4910371.09   359.111395.79  421.2411875.65  407.82
 12045.6  423.5412455.48  430.9412650.42   420.712705.41  428.29 13085.3  435.59
#Mann= 5 ,-1 , 0
       0     .05       0 6018.52      .1       0 8806.54    .045       0
 9016.48      .1       0 9224.91     .07       0
Levee=-1,8001.7,363.18,0,,,,
#XS Ineff= 2 , 0
       0  8001.7     368   10178       0     370
Permanent Ineff=
       F       F
Bank Sta=8806.54,9016.48
XS Rating Curve= 0 ,0
Exp/Cntr=0.3,0.1

Type RM Length L Ch R = 1 ,40855   ,1237.08,1134.33,1039.8
BEGIN DESCRIPTION:
LOB - Kaufman 5 East
END DESCRIPTION:
XS GIS Cut Line= 5
2595299.352093066908122.994780812594743.397824396905789.94596922
2590440.123622556902663.953205482590079.021982556902366.42296064
2585786.156224476901400.69621757
#Sta/Elev= 30
       0  401.15  214.85  400.23  644.56  371.57   884.4  375.85 1339.09   350.2
 4547.89  345.37 5137.78  346.82 5162.77  347.11 7172.37  345.55 7222.36   338.8
 7337.34  362.39  7567.3  345.55 7821.79  345.74 7871.57  337.61 7911.39  319.87
 7951.21  320.82 8025.87   346.2 8185.15  347.67 9623.49  358.7810447.53  420.63
10732.21  404.8611201.66  414.5111271.58  406.8511421.41  416.6611711.07  410.11
11940.81  419.5612215.49  408.5212295.39  419.0212410.26  417.4412585.06  430.07
#Mann= 7 ,-1 , 0
       0     .05       0 4547.89      .1       0 5137.78     .05       0
 5162.77      .1       0 7821.79    .045       0 8025.87      .1       0
 8185.15     .07       0
Levee=-1,7337.34,362.39,0,,,,
#XS Ineff= 2 , 0
       0 7337.34     368               0
Permanent Ineff=
       F       F
Bank Sta=7821.79,8025.87
XS Rating Curve= 0 ,0
Exp/Cntr=0.3,0.1

Type RM Length L Ch R = 1 ,39720   ,1143.14,1165.48,1067.03
BEGIN DESCRIPTION:
LOB - Kaufman MUD1
END DESCRIPTION:
XS GIS Cut Line= 3
2602267.662631476905711.986807562589421.712929736901070.54235031
2588296.712883136900514.98670289
#Sta/Elev= 30
       0  412.69 1619.85  406.03  2084.8  386.78 2464.77   381.5 3039.71  362.12
  3199.7  361.42 3269.69  367.41 3339.69  354.96 6354.37  347.32 8214.17  349.23
 9124.13  342.74 9304.13  347.3310679.08  345.8910789.08  338.8110859.07  348.11
10914.07  362.7611014.07  349.3611239.06  342.9912209.03  346.8312299.02  319.17
12339.02  319.7212384.02  335.9112479.02  346.0912694.01  346.8513413.98  351.62
 14023.9  368.7814383.83  383.6614783.76  412.6214873.74  425.2314913.73   424.2
#Mann= 5 ,-1 , 0
       0     .05       010859.07      .1       012209.03    .045       0
12479.02      .1       012694.01     .07       0
Levee=-1,10914.07,362.76,0,,,,
#XS Ineff= 2 , 0
       010914.07     368               0
Permanent Ineff=
       F       F
Bank Sta=12209.03,12479.02
XS Rating Curve= 0 ,0
Exp/Cntr=0.3,0.1

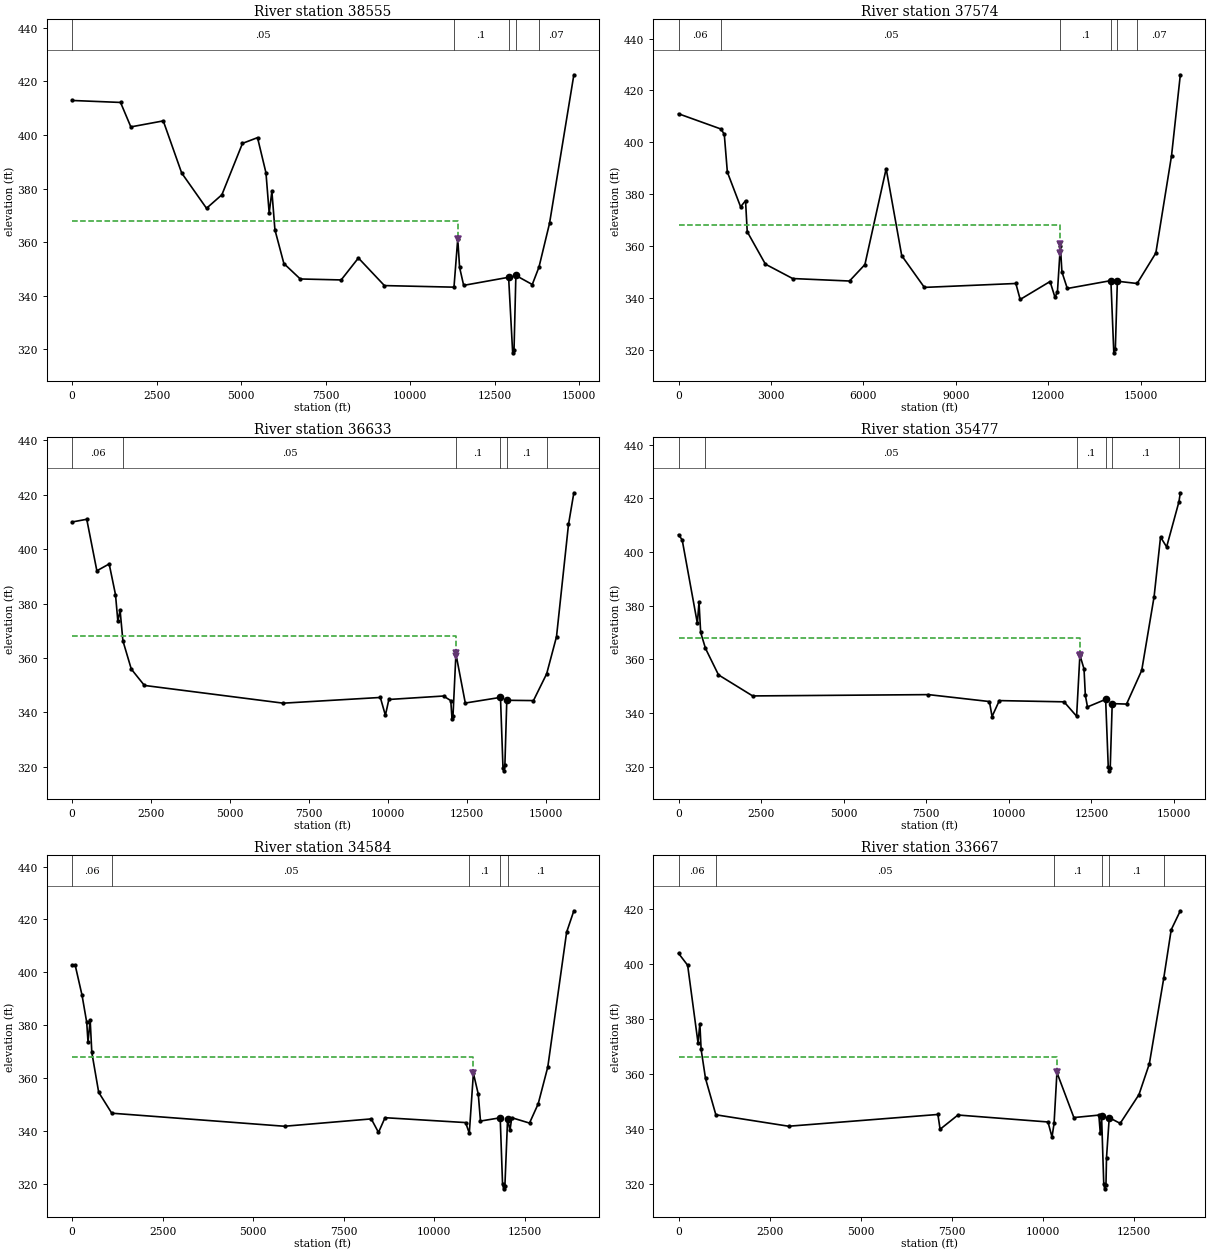
Type RM Length L Ch R = 1 ,38555   ,983.25,981.1,978.78
BEGIN DESCRIPTION:
LOB - Kaufman MUD1
END DESCRIPTION:
XS GIS Cut Line= 5
2602562.801476886905191.153531642597993.476297976901987.08710514
 2592347.91212986900854.886613642589502.070708636900042.74683373
2588998.101900316899834.43130548
#Sta/Elev= 30
       0   412.9 1433.91  412.16 1738.68  403.03 2697.96  405.27 3242.55  385.81
    3977  372.64 4431.64  377.69 5041.17  396.88 5485.82  399.02 5735.69  385.88
 5830.66  370.86 5910.63  378.99  6000.6  364.61  6265.5  352.01 6750.32  346.25
 7959.88  345.89 8469.69  354.08 9239.39  343.78 11297.2  343.1911408.55  361.21
11463.54  350.5511583.52  343.8612913.26  346.8813033.23  318.6713073.23   319.7
13128.22  347.5613613.12  344.1813812.12  350.7114123.02  366.9914843.32  422.49
#Mann= 5 ,-1 , 0
       0     .05       0 11297.2      .1       012913.26    .045       0
13128.22      .1       013812.12     .07       0
Levee=-1,11408.55,361.21,0,,,,
#XS Ineff= 2 , 0
       011408.55     368               0
Permanent Ineff=
       F       F
Bank Sta=12913.26,13128.22
XS Rating Curve= 0 ,0
Exp/Cntr=0.3,0.1

Type RM Length L Ch R = 1 ,37574   ,972.94,940.81,923.97
BEGIN DESCRIPTION:
LOB - Kaufman MUD1
END DESCRIPTION:
XS GIS Cut Line= 3
2604962.107045736901705.042393642592475.634643396899865.98472007
2588949.490777066898876.09792031
#Sta/Elev= 30
       0     411 1379.29   405.1 1484.55  403.07 1584.52  388.47 2014.38  375.08
 2174.34  377.46 2229.32  365.47 2819.14  352.95 3703.87   347.4  5548.3  346.44
 6048.15  352.79 6737.93  389.81 7242.77  356.24 7977.55  343.9810946.83  345.49
 11086.8  339.3212056.57  346.2512216.53  340.1412296.51  342.2912391.32  360.05
12441.48  349.9412616.44  343.5614030.51   346.614125.45  318.7214175.41  320.39
14240.37  346.3614882.48  345.4915489.55  357.2615999.21  394.8516284.03  426.05
#Mann= 6 ,-1 , 0
       0     .06       0 1379.29     .05       012391.32      .1       0
14030.51    .045       014240.37      .1       014882.48     .07       0
Levee=-1,12376.53,360.89,0,,,,
#XS Ineff= 2 , 0
       012376.53     368               0
Permanent Ineff=
       F       F
Bank Sta=14030.51,14240.37
XS Rating Curve= 0 ,0
Exp/Cntr=0.3,0.1

Type RM Length L Ch R = 1 ,36633   ,1154.27,1155.74,1172.84
BEGIN DESCRIPTION:
LOB - Kaufman MUD1
END DESCRIPTION:
XS GIS Cut Line= 3
2604760.718012816900843.931254982592673.594221226898885.19435881
2589130.046190226898042.76461323
#Sta/Elev= 30
       0  409.99  464.99  410.99  784.99  392.06 1174.98  394.57 1374.98  383.29
 1449.98  373.45 1519.98  377.61 1609.26  366.34 1874.97  355.93 2289.97  349.92
 6684.81   343.4 9759.74   345.5 9919.74  338.9510029.74  344.7611759.74  346.03
11989.74  344.3312029.74  337.6212059.74  338.5712152.89  361.5212449.58  343.45
13563.71  345.5313643.65  319.4413668.63  318.53 13703.6  320.7913763.55  344.46
14607.89  344.3515026.13   354.215337.32  367.8215717.03  409.0815886.89  420.73
#Mann= 6 ,-1 , 0
       0     .06       0 1609.26     .05       012152.89      .1       0
13563.71    .045       013763.55      .1       015026.13     .07       0
Levee=-1,12164.74,361.79,0,,,,
#XS Ineff= 2 , 0
       012164.74     368               0
Permanent Ineff=
       F       F
Bank Sta=13563.71,13763.55
XS Rating Curve= 0 ,0
Exp/Cntr=0.3,0.1

Type RM Length L Ch R = 1 ,35477   ,895.92,893.6,873.34
BEGIN DESCRIPTION:
LOB - Kaufman MUD1
END DESCRIPTION:
XS GIS Cut Line= 4
2604429.717034386899892.728432982591809.015241716897517.95693581
2591440.133105476897382.915867312589505.046424466897084.43122806
#Sta/Elev= 30
       0  406.47  109.98   404.6  569.88  373.49  619.86  381.32  669.85  370.08
  816.01   364.1 1209.73  354.23  2244.5  346.38 7568.38  346.87 9413.01  344.29
    9493   338.7 9712.95  344.6411672.57  344.1812053.05  338.8112152.48   361.6
12277.45  356.4412317.45  346.6112382.43  342.2812931.85   345.113011.41  319.89
13041.25  318.4513071.08  319.6513130.76  343.5213564.86  343.3414024.41   355.9
14399.04  383.3914593.85  405.5914778.67  401.9615150.79  418.7615193.27  422.13
#Mann= 6 ,-1 , 0
       0     .06       0  816.01     .05       012053.05      .1       0
12931.85    .045       013130.76      .1       015150.79     .07       0
Levee=-1,12157.47,361.55,0,,,,
#XS Ineff= 2 , 0
       012157.47     368               0
Permanent Ineff=
       F       F
Bank Sta=12931.85,13130.76
XS Rating Curve= 0 ,0
Exp/Cntr=0.3,0.1

Type RM Length L Ch R = 1 ,34584   ,965.72,916.32,871.52
BEGIN DESCRIPTION:
LOB - Kaufman MUD1
END DESCRIPTION:
XS GIS Cut Line= 4
2603713.571485066898623.197179392592125.906668316896679.66792998
2591781.105192566896562.77708764 2590054.35175636896352.83426607
#Sta/Elev= 30
       0  402.75      85   402.8  274.99  391.41  404.98  381.12  439.98  373.75
  499.98  382.01  544.98  369.81  734.97  354.74 1095.71  346.86 5864.76  341.93
 8259.65  344.71 8459.65   339.6 8639.65  345.1610864.65  343.3210966.45  339.31
11079.65  361.9411214.65  354.0311274.65  343.8911819.47  345.13 11884.3  320.18
11914.23   318.311949.14  319.4112023.95  344.8412088.78  340.3312138.71  345.16
12628.52  343.1312868.42  350.3913133.32  364.3213653.12  415.2113853.04  423.29
#Mann= 5 ,-1 , 0
       0     .06       0 1095.71     .05       010966.45      .1       0
11819.47    .045       012023.95      .1       0
Levee=-1,11079.65,361.94,0,,,,
#XS Ineff= 2 , 0
       011079.65     368               0
Permanent Ineff=
       F       F
Bank Sta=11819.47,12023.95
XS Rating Curve= 0 ,0
Exp/Cntr=0.3,0.1

Type RM Length L Ch R = 1 ,33667   ,956.52,1075.45,1196.68
BEGIN DESCRIPTION:
LOB - Kaufman MUD1
END DESCRIPTION:
XS GIS Cut Line= 2
2603705.758836646897109.742201062590039.768452146895487.20902881
#Sta/Elev= 30
       0  403.89  249.95  399.55  534.88  371.25  584.87  378.29  619.86   368.9
  739.84  358.34 1023.68  345.12 3019.33  340.96  7113.4  345.24 7173.39  339.85
 7663.27  345.0410132.77  342.5110242.75  337.0110299.28  341.9910377.72  360.52
10842.63  344.11 11527.5  345.0111567.49  338.3311602.49  344.5311662.47   319.8
11687.47  318.1711722.46  319.4611737.46   329.511812.44  344.0812112.39  341.99
12627.29  352.4612912.23  363.6813306.29  394.7513512.11  412.4813762.06  419.38
#Mann= 6 ,-1 , 0
       0     .06       0 1023.68     .05       010299.28      .1       0
11602.49    .045       011812.44      .1       013306.29     .07       0
Levee=-1,10377.72,360.52,0,,,,
#XS Ineff= 2 , 0
       010377.72     366               0
Permanent Ineff=
       F       F
Bank Sta=11602.49,11812.44
XS Rating Curve= 0 ,0
Exp/Cntr=0.3,0.1

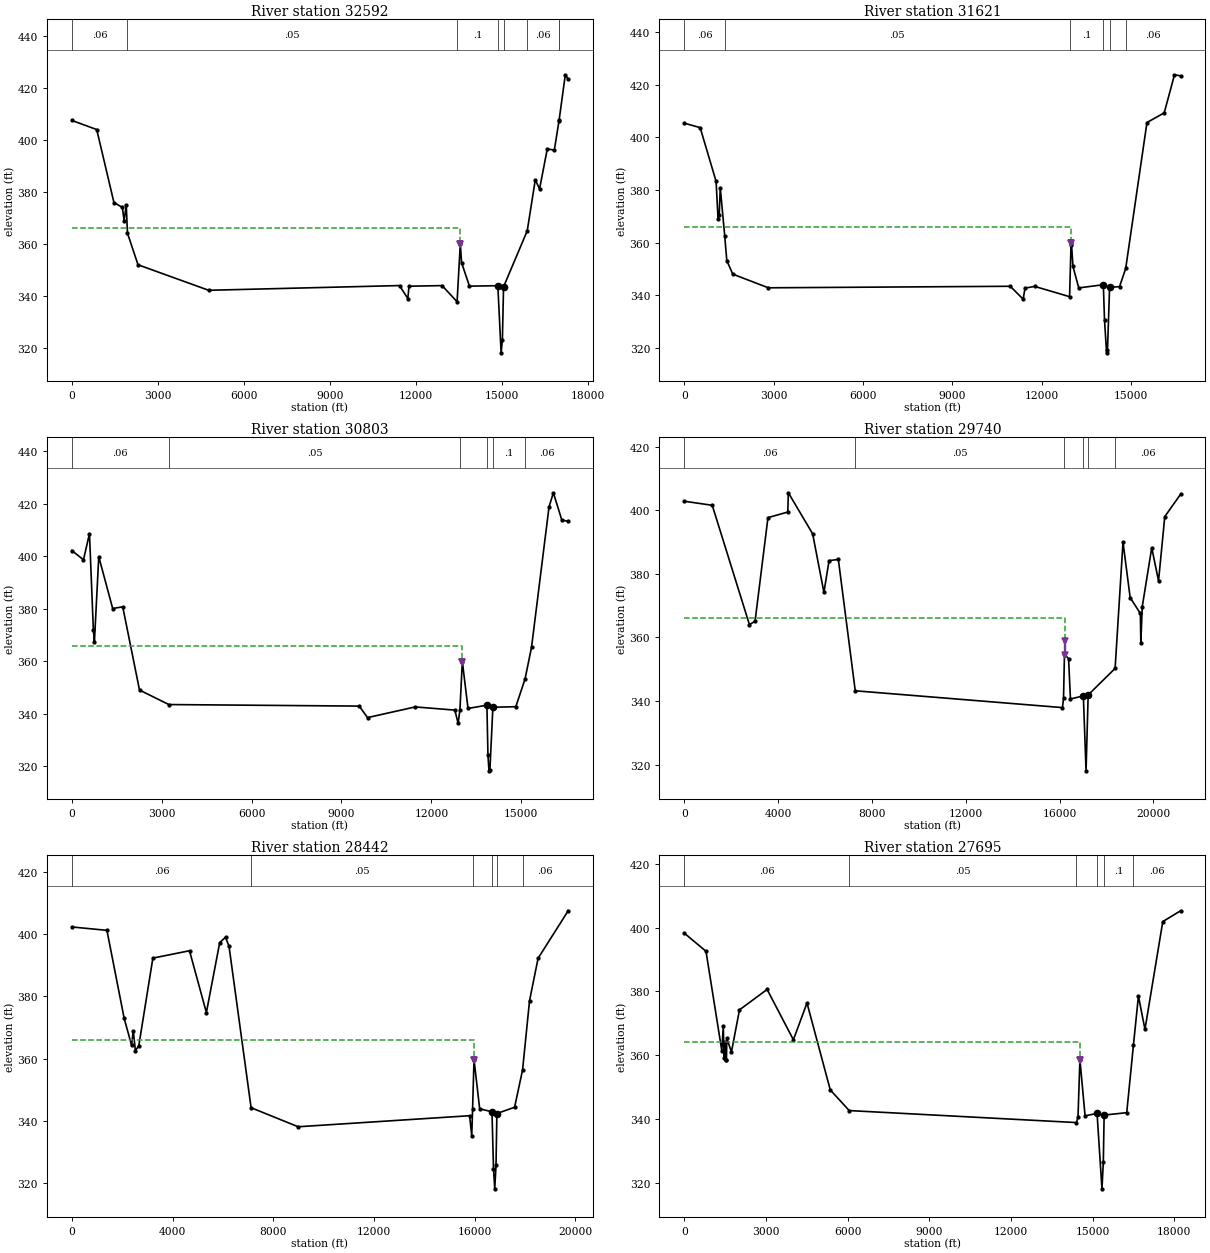
Type RM Length L Ch R = 1 ,32592   ,1033.05,970.38,903.65
BEGIN DESCRIPTION:
LOB - Kaufman MUD1
END DESCRIPTION:
XS GIS Cut Line= 4
2607358.431977476895639.950521232592563.657433236894877.43629822
2592266.782370816894635.248790472590148.135361396894543.05737381
#Sta/Elev= 30
       0  407.41  869.97   403.9 1469.94  375.87 1764.93  373.98 1824.93  368.93
 1899.93  374.88 1941.71  364.14 2309.91  351.96 4774.79  342.1611434.53  343.97
11724.53  338.9811764.53  343.7212919.53  343.96 13442.5  337.7513554.53  359.94
13599.53  352.7513874.53  343.7514864.29  343.9214978.73  318.1315023.51  323.08
15063.31  343.4715890.45  365.0116170.65  384.6116320.34  381.0816589.81   396.5
16834.33  395.9716998.81  407.25   17001  407.4417218.58  424.9417318.38  423.28
#Mann= 8 ,-1 , 0
       0     .06       0 1941.71     .05       0 13442.5      .1       0
14864.29    .045       015063.31      .1       015890.45     .06       0
16998.81      .1       0   17001     .07       0
Levee=-1,13554.53,359.94,0,,,,
#XS Ineff= 2 , 0
       013554.53     366               0
Permanent Ineff=
       F       F
Bank Sta=14864.29,15063.31
XS Rating Curve= 0 ,0
Exp/Cntr=0.3,0.1

Type RM Length L Ch R = 1 ,31621   ,826.23,818.59,801.59
BEGIN DESCRIPTION:
LOB - Kaufman MUD1
END DESCRIPTION:
XS GIS Cut Line= 3
2606934.925606646894297.242248642591852.420666726893856.31957406
2590310.895534566894174.13389906
#Sta/Elev= 30
       0  405.43  534.96  403.73 1069.93  383.31 1134.92   369.2 1174.92  370.53
 1209.92  380.94 1360.52  362.45  1429.9  353.19 1629.89  348.06 2824.81  342.87
 10944.2  343.4511379.16  338.5411439.15  342.7511764.12   343.412935.99   339.5
12983.99  359.0912998.99  359.8413048.98  351.0313243.96  342.8314068.88  344.04
14108.87  330.5714178.86  318.1614208.86  319.2114278.85  343.0314613.82  343.32
 14819.8  350.2215533.51  405.6716113.17  409.3516457.95  423.8116662.79  423.41
#Mann= 6 ,-1 , 0
       0     .06       0 1360.52     .05       012935.99      .1       0
14068.88    .045       014278.85      .1       0 14819.8     .06       0
Levee=-1,12998.99,359.84,0,,,,
#XS Ineff= 2 , 0
       012998.99     366               0
Permanent Ineff=
       F       F
Bank Sta=14068.88,14278.85
XS Rating Curve= 0 ,0
Exp/Cntr=0.3,0.1

Type RM Length L Ch R = 1 ,30803   ,1047.94,1062.87,1071.08
BEGIN DESCRIPTION:
LOB - Kaufman MUD1
END DESCRIPTION:
XS GIS Cut Line= 3
 2606794.78677936892649.117264062591417.311956886893120.90962756
2590430.253235476893772.65799598
#Sta/Elev= 30
       0  402.17  389.99  398.67  589.99  408.62  719.99  371.94  754.99  367.48
  899.98  399.83 1364.97  380.09 1699.97  380.75 2259.96  349.03 3240.56  343.51
 9594.75  342.92 9869.75  338.5411464.75  342.6112784.75  341.3912894.75  336.35
12954.41   341.513034.75  359.8913224.75  342.0213854.75  343.2713889.75  324.24
13924.75  318.2613954.75   318.614054.75  342.4814819.75  342.6915127.73  353.24
15344.75  365.3515928.72  418.8216073.45  424.1816352.92  413.88 16567.5  413.25
#Mann= 6 ,-1 , 0
       0     .06       0 3240.56     .05       012954.41      .1       0
13854.75    .045       014054.75      .1       015127.73     .06       0
Levee=-1,13034.75,359.89,0,,,,
#XS Ineff= 2 , 0
       013034.75     366               0
Permanent Ineff=
       F       F
Bank Sta=13854.75,14054.75
XS Rating Curve= 0 ,0
Exp/Cntr=0.3,0.1

Type RM Length L Ch R = 1 ,29740   ,1181.37,1297.72,1407.87
BEGIN DESCRIPTION:
LOB - Kaufman MUD1
ROB IFA station 18701.54: flow contraction due to natural high ground
END DESCRIPTION:
XS GIS Cut Line= 2
2609776.730946636891513.006347312588630.897582226892158.83970131
#Sta/Elev= 30
       0  402.87 1194.75  401.59 2779.43  364.03 3019.38  365.11 3569.27  397.71
 4414.09  399.47 4439.09  405.53 5473.87  392.62 5953.77   374.2 6173.72  384.17
 6568.64  384.56 7289.66  343.2216121.74  337.9316166.73  340.8516206.39  354.69
16381.69  353.3216461.69  340.6517011.65  341.6117126.64  318.0317216.63  341.91
18365.07  350.2618701.54  390.0119006.51  372.5419441.48  367.5519461.48  358.33
19521.48  369.6519926.45  388.2420216.43  377.8120481.41  398.0221156.37  405.08
#Mann= 6 ,-1 , 0
       0     .06       0 7289.66     .05       016206.39      .1       0
17011.65    .045       017216.63      .1       018365.07     .06       0
Levee=-1,16246.72,358.96,0,,,,
#XS Ineff= 2 , 0
       016246.72     36618701.54       0  390.01
Permanent Ineff=
       F       F
Bank Sta=17011.65,17216.63
XS Rating Curve= 0 ,0
Exp/Cntr=0.3,0.1

Type RM Length L Ch R = 1 ,28442   ,723.51,747.4,763.07
BEGIN DESCRIPTION:
LOB - Kaufman MUD1
END DESCRIPTION:
XS GIS Cut Line= 4
 2609380.89774886890846.339701642593331.783849726890922.40582247
2591296.384049136890446.987481982589721.86980972 6890446.3395174
#Sta/Elev= 30
       0  402.33 1394.94  401.24 2079.91  372.94  2374.9  364.27  2439.9  368.95
 2524.89   362.6 2659.89  364.08 3219.87  392.31 4674.79  394.68 5344.73  374.81
 5874.69   397.3 6104.67  399.03 6244.66  396.09 7120.82  344.21 8989.51  338.09
15799.51  341.6415884.51  335.1715917.22  343.6615974.51  359.6916199.16  343.86
16688.01   342.916747.87  324.6616797.75  318.1316847.63  325.6416882.55  342.35
 17585.9  344.3617902.84  356.3818179.58  378.6418519.45  392.2619713.98  407.53
#Mann= 6 ,-1 , 0
       0     .06       0 7120.82     .05       015917.22      .1       0
16688.01    .045       016882.55      .1       017902.84     .06       0
Levee=-1,15974.51,359.69,0,,,,
#XS Ineff= 2 , 0
       015974.51     366               0
Permanent Ineff=
       F       F
Bank Sta=16688.01,16882.55
XS Rating Curve= 0 ,0
Exp/Cntr=0.3,0.1

Type RM Length L Ch R = 1 ,27695   ,712.16,750.47,644.52
BEGIN DESCRIPTION:
LOB - Kaufman MUD1
END DESCRIPTION:
XS GIS Cut Line= 4
2608185.411622726890290.089501812593686.855974216890290.07801889
2591493.238314236889689.177645892590034.369840896889691.13138214
#Sta/Elev= 30
       0   398.3  799.92  392.58 1379.86  361.43 1434.86  368.98 1464.85  359.16
 1499.85  364.23 1519.85  358.38 1549.85  358.31 1564.84  365.21 1734.83     361
  2029.8   374.2  3044.7  380.61 4009.61  364.81 4509.56  376.35 5364.48  349.07
 6059.67  342.5814407.11  338.81 14463.6  340.5214533.59  358.6114723.55  340.92
15163.45   341.715343.41  318.01 15393.4  326.4115423.39  341.1716253.21  341.92
16501.62  363.3116683.06  378.5216922.91  368.07 17577.4   401.918231.88   405.3
#Mann= 6 ,-1 , 0
       0     .06       0 6059.67     .05       014407.11      .1       0
15163.45    .045       015423.39      .1       016501.62     .06       0
Levee=-1,14533.59,358.61,0,,,,
#XS Ineff= 2 , 0
       014533.59     364               0
Permanent Ineff=
       F       F
Bank Sta=15163.45,15423.39
XS Rating Curve= 0 ,0
Exp/Cntr=0.3,0.1

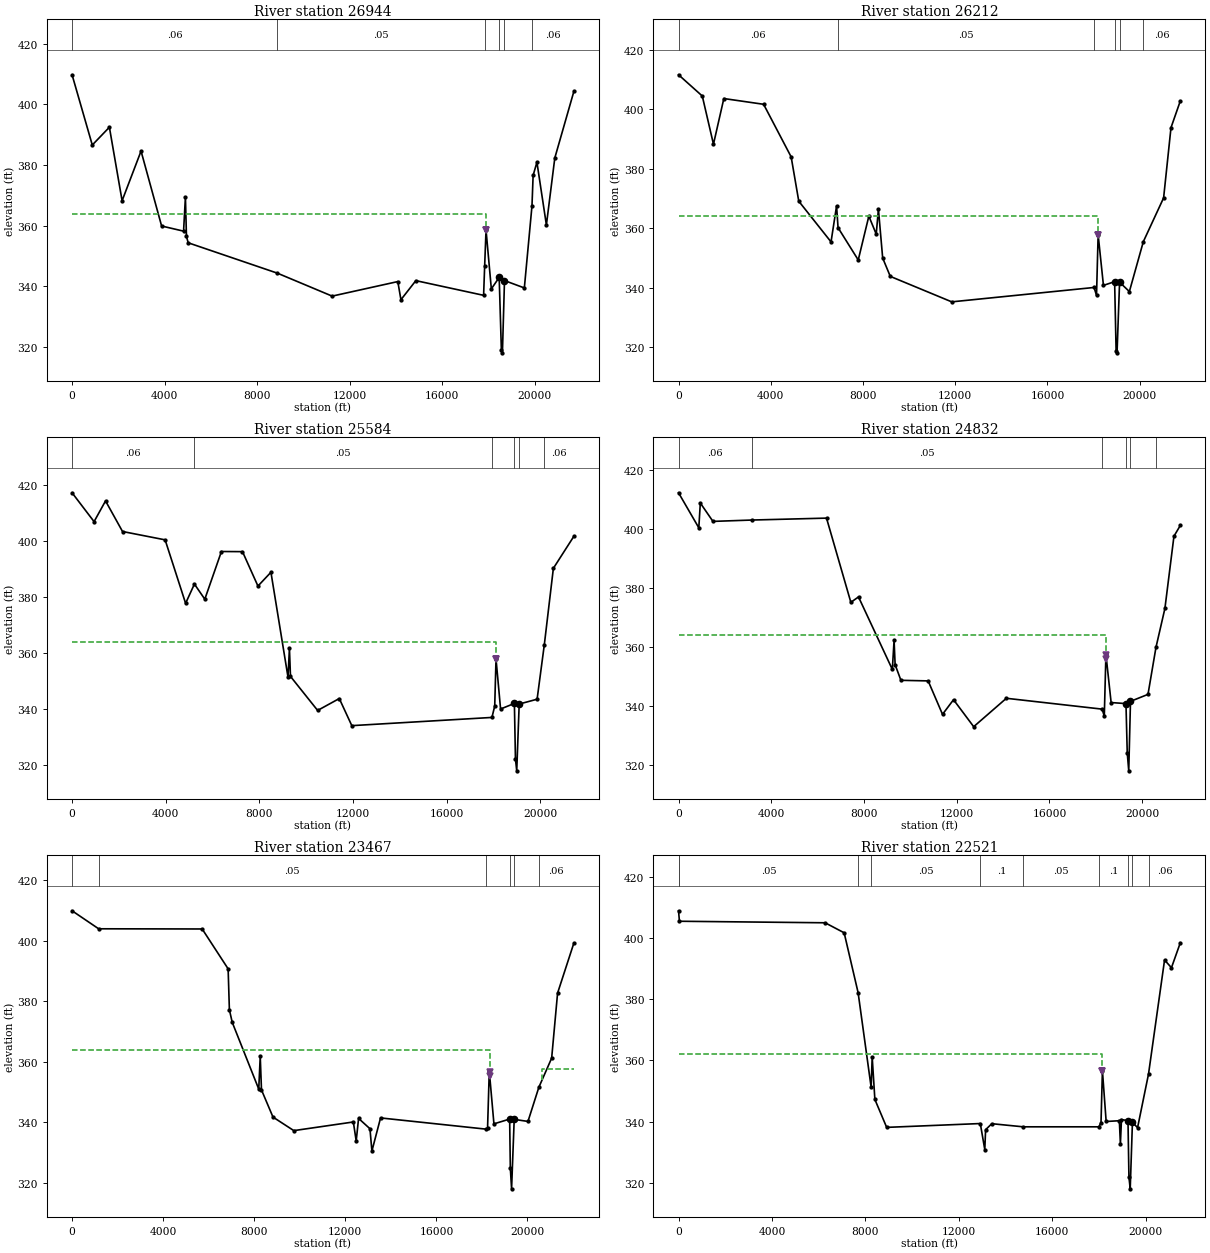
Type RM Length L Ch R = 1 ,26944   ,799.77,731.95,575.72
BEGIN DESCRIPTION:
LOB - Kaufman MUD1
END DESCRIPTION:
XS GIS Cut Line= 5
2611827.732093976888284.035443072607196.270884476888490.88050181
2594067.997600396889634.380839482592496.817015726889321.88080831
2590219.274326736889437.78444789
#Sta/Elev= 30
       0  409.79  874.26  386.61 1613.63  392.48 2163.16  368.22 2982.48  384.61
 3871.74  359.88 4821.05  358.18 4901.03  369.45 4946.02  356.43 5021.01  354.34
 8878.68  344.3111244.86  336.7414084.31  341.5414219.28  335.5514864.16  341.85
17793.86     33717839.72  346.7417898.69  358.5618128.24  339.1218467.58  342.91
18562.39  318.9518607.31  318.0218697.13  341.8719555.45  339.4419885.43  366.51
19934.71  376.5720099.39  380.9220508.59  360.2320872.87  382.3521696.26  404.29
#Mann= 6 ,-1 , 0
       0     .06       0 8878.68     .05       017839.72      .1       0
18467.58    .045       018697.13      .1       019885.43     .06       0
Levee=-1,17898.69,358.56,0,,,,
#XS Ineff= 2 , 0
       017898.69     364               0
Permanent Ineff=
       F       F
Bank Sta=18467.58,18697.13
XS Rating Curve= 0 ,0
Exp/Cntr=0.3,0.1

Type RM Length L Ch R = 1 ,26212   ,640.76,628.96,608.64
BEGIN DESCRIPTION:
LOB - Kaufman MUD1
END DESCRIPTION:
XS GIS Cut Line= 2
2612128.934903646886531.613422972590517.650370396889104.86680664
#Sta/Elev= 30
       0  411.56 1029.95  404.43 1514.93  388.25 1964.91  403.58 3689.84  401.65
 4884.78  383.99 5214.76  369.11 6614.68  355.44 6854.67  367.54  6918.6  360.22
 7794.61  349.37 8254.59  364.09 8574.59  358.06 8669.59  366.43 8854.59  350.02
 9184.59  343.8611849.59  335.3118022.85  340.1418129.59  337.4718199.59  357.86
18429.59  340.8418914.59  342.0918979.59  318.7719019.59  318.1919129.59  341.91
19554.59  338.7720159.86  355.5221039.59  370.2221359.59   393.821764.59  402.78
#Mann= 6 ,-1 , 0
       0     .06       0  6918.6     .05       018022.85      .1       0
18914.59    .045       019129.59      .1       020159.86     .06       0
Levee=-1,18199.59,357.86,0,,,,
#XS Ineff= 2 , 0
       018199.59     364               0
Permanent Ineff=
       F       F
Bank Sta=18914.59,19129.59
XS Rating Curve= 0 ,0
Exp/Cntr=0.3,0.1

Type RM Length L Ch R = 1 ,25584   ,776.67,751.9,730.89
BEGIN DESCRIPTION:
LOB - Kaufman MUD1
END DESCRIPTION:
XS GIS Cut Line= 2
2611853.773708556885106.951902232590701.603086476888562.36821973
#Sta/Elev= 30
       0  417.24  939.89  406.94 1429.84  414.34 2154.76  403.42 3974.57  400.44
 4849.48  377.78 5225.59  384.66  5669.4  379.26 6379.32  396.28 7279.23  396.23
 7939.16  383.95 8494.08  388.87 9223.93  351.41 9283.92  361.73 9328.91   351.7
10488.69  339.5611413.51   343.8 11948.4  334.1317933.65  337.0618052.54  341.12
18107.54  357.9418302.54  340.0718892.54  342.0618937.54  322.2718992.54     318
19097.54  341.8419862.54  343.56 20170.7  363.0120557.54  390.2921432.54   401.7
#Mann= 6 ,-1 , 0
       0     .06       0 5225.59     .05       017933.65      .1       0
18892.54    .045       019097.54      .1       0 20170.7     .06       0
Levee=-1,18107.54,357.94,0,,,,
#XS Ineff= 2 , 0
       018107.54     364               0
Permanent Ineff=
       F       F
Bank Sta=18892.54,19097.54
XS Rating Curve= 0 ,0
Exp/Cntr=0.3,0.1

Type RM Length L Ch R = 1 ,24832   ,1358.25,1364.88,1358.12
BEGIN DESCRIPTION:
LOB - Kaufman MUD1
END DESCRIPTION:
XS GIS Cut Line= 2
2611894.422905476883211.363173722590766.707286976887922.17724289
#Sta/Elev= 30
       0  412.32  874.86  400.43  939.85  408.84 1484.76  402.61 3171.52  403.07
 6383.98  403.72 7433.81  375.14 7763.76  376.98 9223.49  352.37 9298.48  362.23
 9343.47     354 9593.42  348.6810768.19  348.4811388.07  337.1311862.98   342.1
12732.81  332.9414142.53  342.5818273.67   338.918367.09  336.5118437.09  357.46
18662.09  341.1319302.09  340.7819357.09   324.119422.09  317.9619497.09  341.54
20252.09  343.9120597.19  359.8920982.09  373.0721372.09  397.5721647.09  401.25
#Mann= 6 ,-1 , 0
       0     .06       0 3171.52     .05       018273.67      .1       0
19302.09    .045       019497.09      .1       020597.19     .06       0
Levee=-1,18457.09,357.37,0,,,,
#XS Ineff= 2 , 0
       018457.09     364               0
Permanent Ineff=
       F       F
Bank Sta=19302.09,19497.09
XS Rating Curve= 0 ,0
Exp/Cntr=0.3,0.1

Type RM Length L Ch R = 1 ,23467   ,942.26,945.95,935.47
BEGIN DESCRIPTION:
LOB - Kaufman MUD1
ROB IFA station 20632.04: flow contraction due to natural high ground
END DESCRIPTION:
XS GIS Cut Line= 2
2611653.252456056881984.744563982590119.055367056886662.84905289
#Sta/Elev= 30
       0  409.98 1167.46  404.02 5714.05  403.96 6853.86  390.77 6908.85  377.22
 7033.83  373.08 8198.63  350.99 8263.62  361.83 8318.61  350.71 8823.51  341.73
 9738.33  337.2512352.82  340.11 12477.8  333.8212582.78  341.2913082.68  337.87
13167.66   330.513547.59  341.4518167.38  337.7518247.04  338.0518322.04  356.98
18527.04  339.4919217.04  341.0719247.04  324.8619302.04  317.9919417.04  340.97
20022.04  340.29 20497.7  351.5521062.04  361.2321322.04  382.7422037.04  399.29
#Mann= 6 ,-1 , 0
       0     .06       0 1167.46     .05       018167.38      .1       0
19217.04    .045       019417.04      .1       0 20497.7     .06       0
Levee=-1,18342.04,356.76,0,,,,
#XS Ineff= 2 , 0
       018342.04     36420632.04       0  357.77
Permanent Ineff=
       F       F
Bank Sta=19217.04,19417.04
XS Rating Curve= 0 ,0
Exp/Cntr=0.3,0.1

Type RM Length L Ch R = 1 ,22521   ,792.48,799.63,800.35
BEGIN DESCRIPTION:
LOB - Kaufman MUD1
END DESCRIPTION:
XS GIS Cut Line= 2
2611339.689106816880927.524893642590389.888814886885662.84908439
#Sta/Elev= 30
       0  408.81   38.57  405.39 6274.47  404.89 7089.39  401.62 7686.85  382.07
 8244.63  351.19 8289.28  361.02 8404.28  347.21 8909.26  338.0912917.72  339.34
13109.14  330.8413144.14  337.3313409.13  339.2914752.93  338.2717994.29  338.27
18084.05  339.6718144.05  356.6418304.05  340.0118869.05  340.2618914.05  332.68
18959.05  340.6519239.05  340.2819279.05  321.8419334.05  318.0219429.05  339.74
19649.05  337.9920117.21  355.4920804.05  392.7321099.05  390.2221479.05  398.37
#Mann= 10 ,-1 , 0
       0     .06       0   38.57     .05       0 7686.85     .06       0
 8244.63     .05       012917.72      .1       014752.93     .05       0
17994.29      .1       019239.05    .045       019429.05      .1       0
20117.21     .06       0
Levee=-1,18144.05,356.64,0,,,,
#XS Ineff= 2 , 0
       018144.05     362               0
Permanent Ineff=
       F       F
Bank Sta=19239.05,19429.05
XS Rating Curve= 0 ,0
Exp/Cntr=0.3,0.1