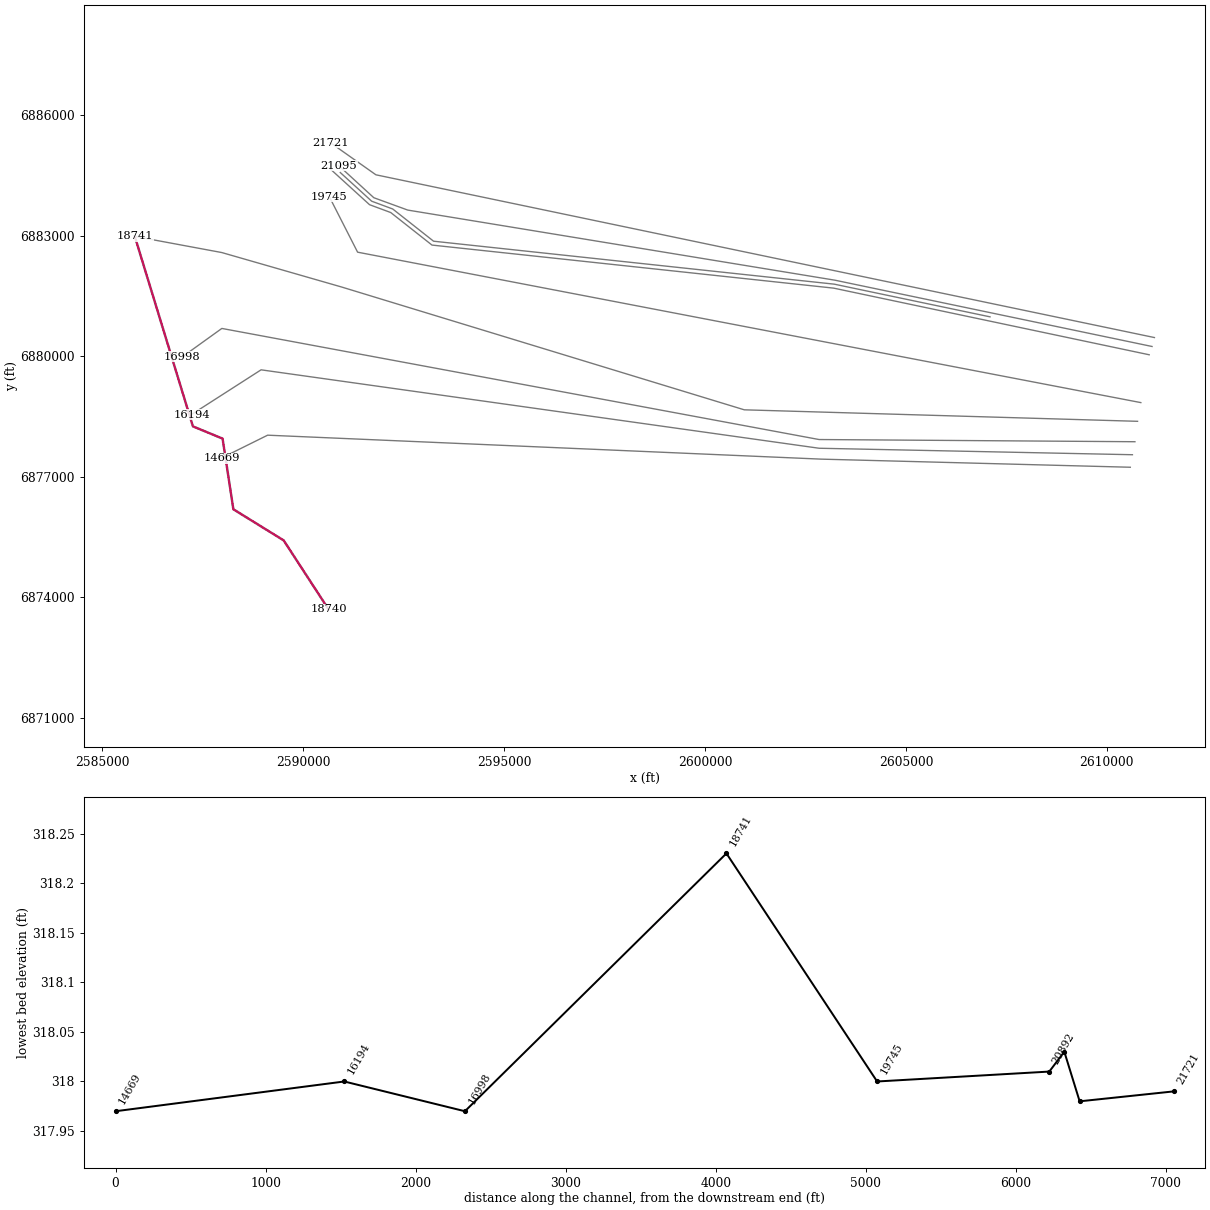
HEC-RAS study EF_FEMA.prj: East_Fork_FEMA

--- EF_FEMA.g06 (geometry) --- (continued)

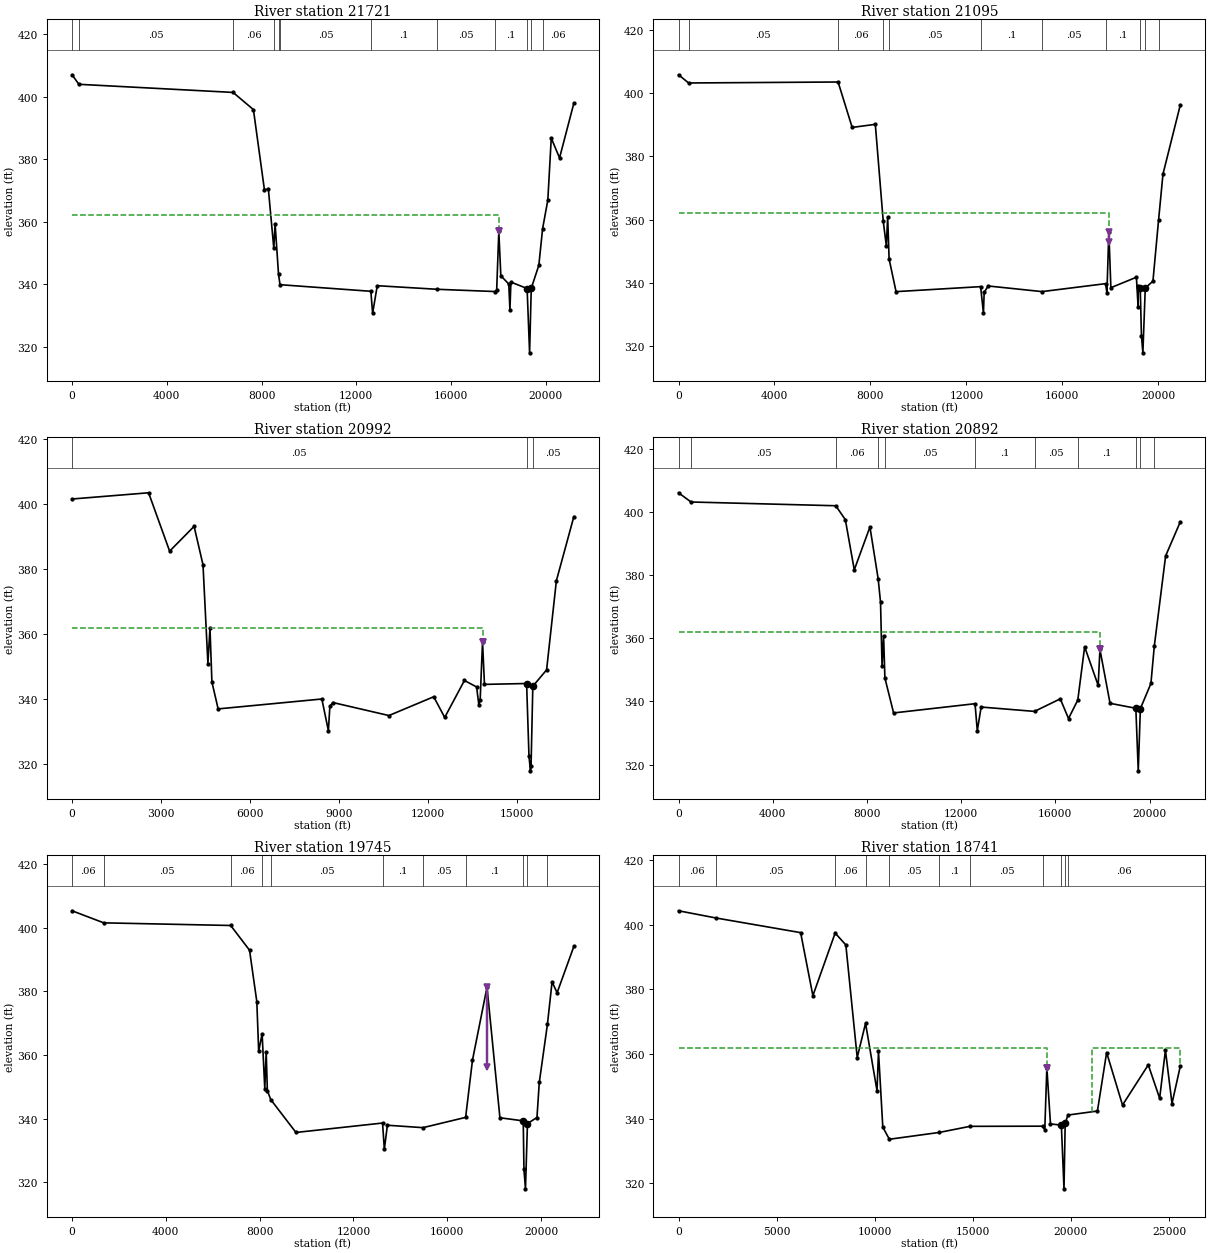
Type RM Length L Ch R = 1 ,21721   ,755.29,626.6,592.48
BEGIN DESCRIPTION:
LOB - Kaufman MUD1
END DESCRIPTION:
XS GIS Cut Line= 3
2611183.935481316880465.104230572591806.664852726884518.53313155
2590667.666474556885322.57122165
#Sta/Elev= 30
       0  407.03  287.68  403.98 6799.59  401.38 7658.83  395.88 8123.76  370.18
 8288.74  370.52 8519.83  351.47 8573.68  359.34 8718.85  343.16 8781.81  339.81
12617.68   337.712692.88  330.6512887.84  339.4915418.59  338.34 17864.8  337.62
17931.95  338.1418021.93  356.8718106.92  342.6818441.88  340.0318491.87  331.78
18531.87  340.6519216.77  338.5919321.76  317.9919391.75  338.6419711.71  346.03
19871.54  357.7720091.57  366.9220236.51  386.7620586.37   380.421191.12  397.93
#Mann= 12 ,-1 , 0
       0     .06       0  287.68     .05       0 6799.59     .06       0
 8519.83     .05       0 8718.85      .1       0 8781.81     .05       0
12617.68      .1       015418.59     .05       0 17864.8      .1       0
19216.77    .045       019391.75      .1       019871.54     .06       0
Levee=-1,18021.93,356.87,0,,,,
#XS Ineff= 2 , 0
       018021.93     362               0
Permanent Ineff=
       F       F
Bank Sta=19216.77,19391.75
XS Rating Curve= 0 ,0
Exp/Cntr=0.3,0.1

Type RM Length L Ch R = 1 ,21095   ,102.18,102.18,101.29
BEGIN DESCRIPTION:
LOB - Kaufman MUD1
END DESCRIPTION:
XS GIS Cut Line= 5
2611124.633762646880242.536106142603231.653485646881893.62401131
2592599.012677486883639.824259062591754.477949226883947.93551947
2590882.944259236884746.18228257
#Sta/Elev= 30
       0   405.8  420.69  403.21 6652.16  403.52 7239.07  389.17 8203.92  390.15
 8532.87  359.63 8663.72  351.75 8718.69  360.96 8778.66  347.61 9068.54  337.31
12594.37  338.89 12711.9  330.5112741.89  337.0412906.81   339.115154.62  337.32
17803.39  339.8317859.68  336.9417939.65  356.2218024.61  338.55   19089  341.86
19158.92  332.57 19173.9  339.0419248.81  338.4719298.76  323.3719358.69  317.98
19458.57  338.4619778.13  340.6120012.64  359.9120196.98  374.45   20920  396.31
#Mann= 11 ,-1 , 0
       0     .06       0  420.69     .05       0 6652.16     .06       0
 8532.87      .1       0 8778.66     .05       012594.37      .1       0
15154.62     .05       017803.39      .1       019248.81    .045       0
19458.57      .1       020012.64     .06       0
Levee=-1,17954.6,356.14,0,,,,
#XS Ineff= 2 , 0
       0 17954.6     362               0
Permanent Ineff=
       F       F
Bank Sta=19248.81,19458.57
XS Rating Curve= 0 ,0
Exp/Cntr=0.3,0.1

Type RM Length L Ch R = 1 ,20992   ,100.04,100.18,100.47
BEGIN DESCRIPTION:
LOB - Kaufman MUD1
END DESCRIPTION:
XS GIS Cut Line= 6
2607092.583099726880980.739354152603216.006863396881794.72886789
2593241.707258226882864.644378982592225.466180476883666.69986148
2591701.437372896883860.947504482590920.187294976884574.48905639
#Sta/Elev= 30
       0  401.51 2577.48  403.42 3286.79  385.49 4111.09  393.11 4410.99  381.29
 4575.94  350.98 4645.92  361.85  4710.9  345.32 4920.83  337.05  8414.7  340.09
 8634.61  330.35 8684.59  337.85 8789.55     33910673.82  335.0112183.23  340.78
12553.08  334.4313217.82  345.7813627.66  343.7913702.63  338.3213747.61  339.86
13827.58   357.713892.56  344.5815312.07  344.8515391.92  322.5915441.82  318.03
15461.78  319.4515521.66     34415985.78  349.0416315.19  376.4116904.05   396.1
#Mann= 3 , 0 , 0
       0     .05       015312.07    .045       015521.66     .05       0
Levee=-1,13827.64,357.7,0,,,,
#XS Ineff= 2 , 0
       013827.64     362               0
Permanent Ineff=
       F       F
Bank Sta=15312.07,15521.66
XS Rating Curve= 0 ,0
Exp/Cntr=0.3,0.1

Type RM Length L Ch R = 1 ,20892   ,1089.95,1147.33,1182.64
BEGIN DESCRIPTION:
LOB - Kaufman MUD1
END DESCRIPTION:
XS GIS Cut Line= 6
2611054.003326486880036.169720982603200.360241136881695.83372448
2593202.381221386882768.289256722592175.905912136883578.42182282
2591648.396796556883773.959489482590647.701291386884685.41829647
#Sta/Elev= 30
       0  406.14  530.05  403.22 6675.33  402.03 7082.44  397.63  7462.3  381.72
 8127.05   395.3 8476.64  378.86 8576.87  371.46 8641.85  351.09 8706.82  360.86
 8762.77  347.42 9131.66  336.36 12589.4  339.2912685.27  330.76 12850.2  338.23
15114.79  336.8516208.89  340.8316558.75  334.5916952.69  340.4417243.48  357.32
17818.26  345.0917893.23  356.4918322.69  339.4119417.79  337.8419520.04  318.01
19609.65  337.7120058.05   345.720200.98  357.5120682.31  386.1321306.58  396.95
#Mann= 11 ,-1 , 0
       0     .06       0  530.05     .05       0 6675.33     .06       0
 8476.64      .1       0 8762.77     .05       0 12589.4      .1       0
15114.79     .05       016952.69      .1       019417.79    .045       0
19609.65      .1       020200.98     .06       0
Levee=-1,17893.24,356.49,0,,,,
#XS Ineff= 2 , 0
       017893.24     362               0
Permanent Ineff=
       F       F
Bank Sta=19417.79,19609.65
XS Rating Curve= 0 ,0
Exp/Cntr=0.3,0.1

Type RM Length L Ch R = 1 ,19745   ,1044.98,1004.29,1000.61
BEGIN DESCRIPTION:
LOB - Kaufman MUD1
END DESCRIPTION:
XS GIS Cut Line= 3
2610845.619884976878844.942444642591350.935777316882591.44971539
2590647.810871216883971.65791298
#Sta/Elev= 30
       0  405.35 1349.35  401.56 6764.94  400.73 7568.71  392.96 7878.66  376.83
 7958.65  361.23 8105.38  366.69  8218.6  349.51 8278.59  361.03 8328.58  348.87
 8473.78  346.03 9548.34  335.7113241.05  338.6713317.61  330.4613447.58  337.98
14965.53  337.2216783.66  340.4517076.86  358.4417696.73  381.3618246.62  340.33
19241.41  339.35 19271.4  324.1119336.39     31819421.37  338.5119826.29   340.4
19926.22  351.46 20273.4  369.73 20470.8  383.0120685.63   379.621400.07  394.16
#Mann= 11 ,-1 , 0
       0     .06       0 1349.35     .05       0 6764.94     .06       0
 8105.38      .1       0 8473.78     .05       013241.05      .1       0
14965.53     .05       016783.66      .1       019241.41    .045       0
19421.37      .1       0 20273.4     .06       0
Levee=-1,17696.51,356.2,0,,,,
#XS Ineff= 2 , 0
       017696.51     362               0
Permanent Ineff=
       F       F
Bank Sta=19241.41,19421.37
XS Rating Curve= 0 ,0
Exp/Cntr=0.3,0.1

Type RM Length L Ch R = 1 ,18741   ,1655.65,1742.82,1950.26
BEGIN DESCRIPTION:
LOB - Kaufman MUD1
ROB IFA station 211097: flow expansion due to natural high ground upstream
END DESCRIPTION:
XS GIS Cut Line= 5
2610763.852660066878378.988652142600975.607472816878665.28499556
2590955.961501646881722.923565312587971.051132896882582.00747706
 2585804.89962536882984.95319347
#Sta/Elev= 30
       0  404.36 1899.51  402.14 6223.41  397.59 6848.26  378.06 7982.98  397.46
 8527.83  393.79 9107.67  358.91 9532.54   369.510117.34  348.6210192.31   360.8
10412.23  337.3310747.09  333.59 13291.1   335.714855.49  337.5918569.04  337.64
   18669  336.5118773.96  355.8118958.89  338.3419513.67  337.9619648.62  318.23
19708.59  338.5719853.54  341.09 21352.1  342.3321821.55  360.46 22630.6  344.18
23944.29  356.6324523.83  346.29 24818.6  361.1525153.34  344.6625578.01  356.27
#Mann= 11 ,-1 , 0
       0     .06       0 1899.51     .05       0 7982.98     .06       0
 9532.54      .1       010747.09     .05       0 13291.1      .1       0
14855.49     .05       018569.04      .1       019513.67    .045       0
19708.59      .1       019853.54     .06       0
Levee=-1,18773.96,355.81,0,,,,
#XS Ineff= 2 , 0
       018773.96     362 21097.4       0     362
Permanent Ineff=
       F       F
Bank Sta=19513.67,19708.59
XS Rating Curve= 0 ,0
Exp/Cntr=0.3,0.1

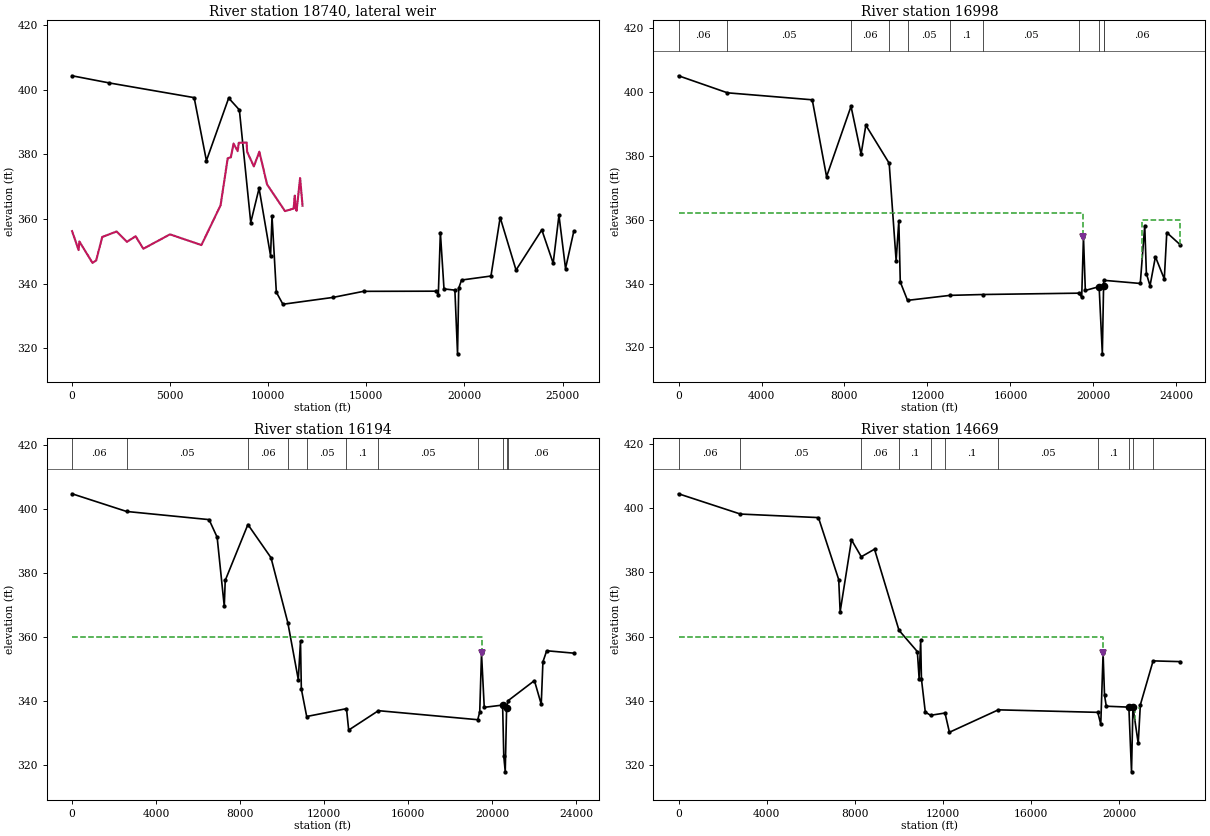
Type RM Length L Ch R = 6 ,18740   ,,,
BEGIN DESCRIPTION:
Spill to Trinity River
END DESCRIPTION:
Lateral Weir Pos= 3
Lateral Weir Distance=0
Lateral Weir TW Multiple XS=0
Lateral Weir WD=10
Lateral Weir Coef=0.8
LW OverFlow Method 2D=-1
LW OverFlow Use Velocity Into 2D=0
Lateral Weir WSCriteria=-1
Lateral Weir Flap Gates= 0
Lateral Weir Hagers EQN= 0 ,,,,,
Lateral Weir SS=0.05,0.05,
Lateral Weir Type= 0
Lateral Weir Connection Pos and Dist= 3 ,
Lateral Weir SE= 30
       0  356.25  332.53  350.37   371.6  353.03  1041.9   346.4 1230.38  347.18
 1537.82  354.43 2270.43  356.13 2793.53  352.94 3240.91  354.64  3631.1  350.78
 4990.21  355.24 6593.92  351.92 7570.23  364.25 7933.66  378.82 8093.81   379.1
 8230.79  383.36 8442.26  381.02 8496.95  383.61 8898.18   383.7 8923.29   380.8
 9265.93   376.3 9547.22  380.84 9940.53  370.6910854.54  362.4411294.72  363.23
11354.82  367.2611376.08  363.6911443.15  362.5311624.27  372.6711748.17   364.1
Lateral Weir Centerline= 6
2585804.899634426882984.953209122587251.912076566878253.03769988
2587990.309067316877948.335732282588258.879669166876188.25399038
2589511.295401726875412.822347912590625.797712836873699.69922657
LW Div RC= 0 ,False,,

Type RM Length L Ch R = 1 ,16998   ,770.11,804.03,805.59
BEGIN DESCRIPTION:
LOB - Kaufman MUD1
ROB IFA station 22350: flow expansion due to natural high ground upstream
END DESCRIPTION:
XS GIS Cut Line= 4
2610698.685139466877870.605482562602837.471859316877925.18050465
2587972.020619146880692.107385472586988.65152289 6879984.7285509
#Sta/Elev= 30
       0  405.13 2358.92  399.79 6447.14   397.6 7136.85  373.52 8316.41  395.55
 8801.27  380.56  9031.2  389.6310155.87  377.7110490.77  347.1610620.74  359.69
10690.72   340.511040.61  334.7313090.02   336.314689.55  336.5719297.92  336.99
19437.86  335.7219522.83  354.6719612.79  337.8420277.54  339.0320432.47  317.97
20492.45  339.1320497.45  341.0222261.76  340.0322476.68  358.1722556.64  343.12
22731.58  339.3122991.45   348.4 23420.1  341.4323539.73  355.9924192.68  352.13
#Mann= 11 ,-1 , 0
       0     .06       0 2358.92     .05       0 8316.41     .06       0
10155.87      .1       011040.61     .05       013090.02      .1       0
14689.55     .05       019297.92      .1       020277.54    .045       0
20492.45      .1       020497.45     .06       0
Levee=-1,19522.83,354.67,0,,,,
#XS Ineff= 2 , 0
       019522.83     362   22350       0     360
Permanent Ineff=
       F       F
Bank Sta=20277.54,20492.45
XS Rating Curve= 0 ,0
Exp/Cntr=0.3,0.1

Type RM Length L Ch R = 1 ,16194   ,1459.55,1524.39,1548.01
BEGIN DESCRIPTION:
LOB - Kaufman MUD1
END DESCRIPTION:
XS GIS Cut Line= 4
2610636.035986566877546.874502732602837.471859316877708.16650298
2588948.582970476879661.291533722587214.015245396878546.99454972
#Sta/Elev= 30
       0  404.83 2593.41  399.31 6520.94  396.76  6905.7  391.27 7245.48  369.67
 7290.45  377.77 8369.93  395.23  9469.5  384.8710269.19  364.6110768.99  346.81
10873.95  358.8410913.94  343.8711168.84  335.28 13063.1  337.7313168.06  331.04
 14582.5   337.119310.66  334.2819405.62  336.6919490.59  354.9719620.54  338.14
20495.19  338.8520550.17  322.9120620.14     31820685.12  338.0920760.09  340.24
22009.38  346.4922333.88  339.0922413.75  352.3522593.47  355.8123886.45  355.06
#Mann= 11 ,-1 , 0
       0     .06       0 2593.41     .05       0 8369.93     .06       0
10269.19      .1       011168.84     .05       0 13063.1      .1       0
 14582.5     .05       019310.66      .1       020495.19    .045       0
20685.12      .1       020760.09     .06       0
Levee=-1,19490.59,354.97,0,,,,
#XS Ineff= 2 , 0
        19490.59     360
Permanent Ineff=
       F       F
Bank Sta=20495.19,20685.12
XS Rating Curve= 0 ,0
Exp/Cntr=0.3,0.1

Type RM Length L Ch R = 1 ,14669   ,1925.16,2040.36,2071.02
BEGIN DESCRIPTION:
LOB - Kaufman MUD1
END DESCRIPTION:
XS GIS Cut Line= 4
2610583.787731476877234.965021572602891.72535972 6877436.8990009
2589111.343471726878033.687505482587959.75128672 6877462.1194229
#Sta/Elev= 30
       0  404.48  2809.9  398.17 6349.68  397.07 7269.61  377.78  7334.6  367.79
 7849.56  390.13  8294.5  384.88 8894.38  387.2410004.17  362.02   10839  355.37
10918.99  346.9810988.97  358.9411023.97  346.8511198.93  336.5711438.88  335.56
12093.76  336.2712293.72  330.2814513.28  337.2619027.92  336.4819162.92  332.74
19267.92  354.8319332.92  341.8319412.92  338.3920437.92   338.120557.92  317.97
20622.92  338.1920862.92  326.8120957.92  338.7921537.74  352.4922773.38  352.26
#Mann= 11 ,-1 , 0
       0     .06       0  2809.9     .05       0  8294.5     .06       0
10004.17      .1       011438.88     .05       012093.76      .1       0
14513.28     .05       019027.92      .1       020437.92    .045       0
20622.92      .1       021537.74     .06       0
Levee=-1,19267.92,354.83,0,,,,
#XS Ineff= 2 ,-1
       019267.92     36020712.92 20952.5  337.85
Permanent Ineff=
       F       F
Bank Sta=20437.92,20622.92
XS Rating Curve= 0 ,0
Exp/Cntr=0.3,0.1