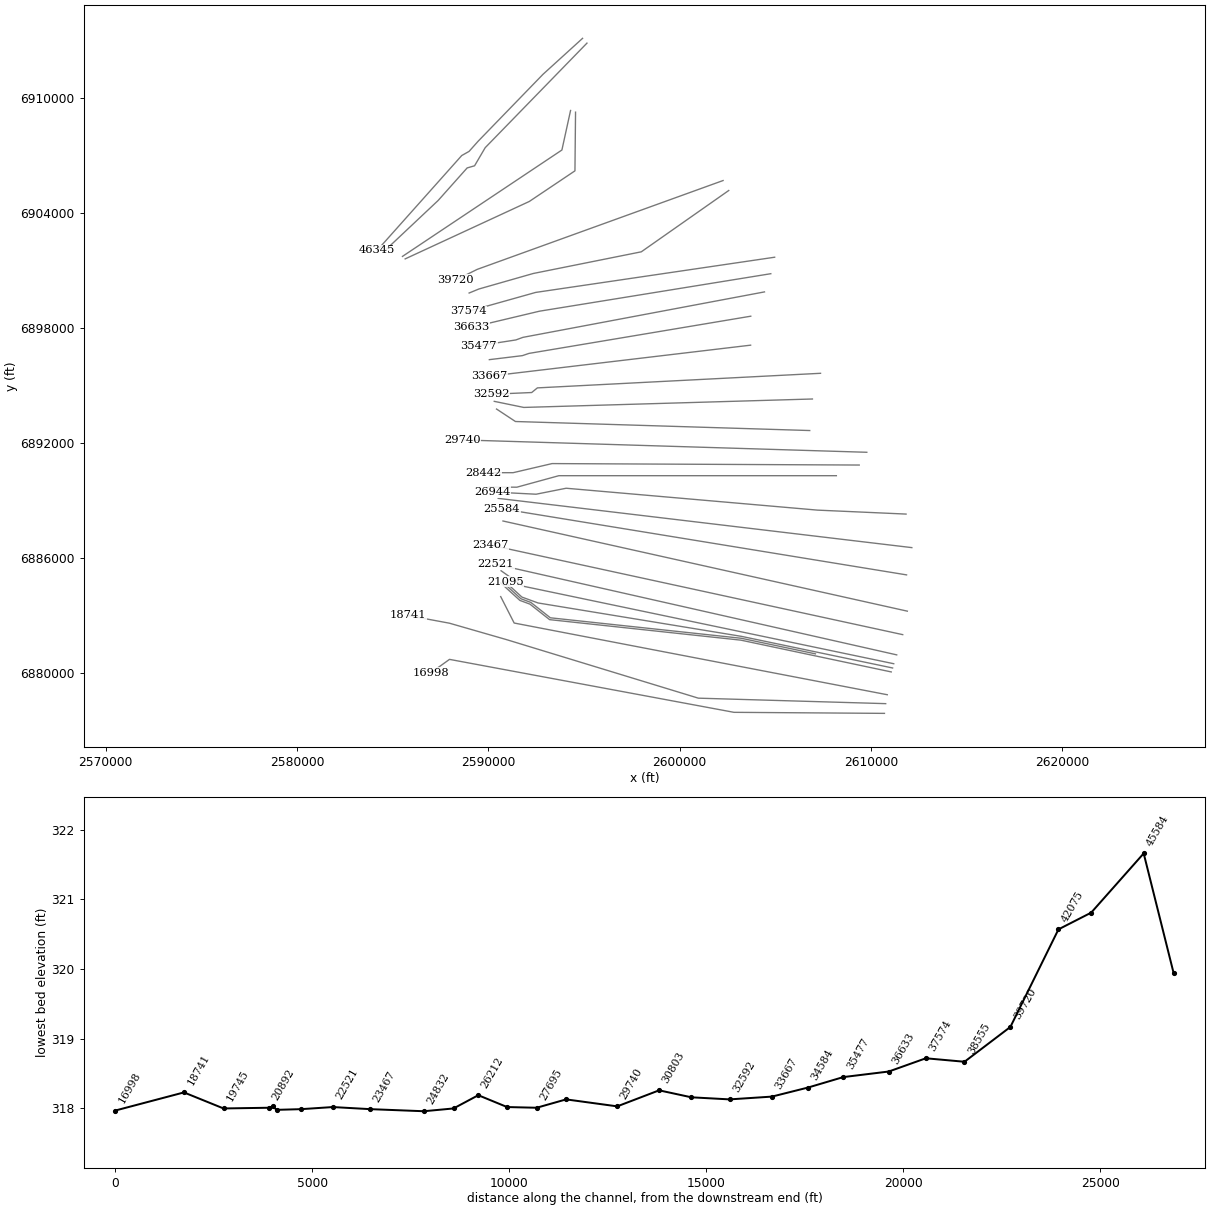
HEC-RAS study EF_FEMA.prj: East_Fork_FEMA

--- EF_FEMA.g01 (geometry) --- (continued)

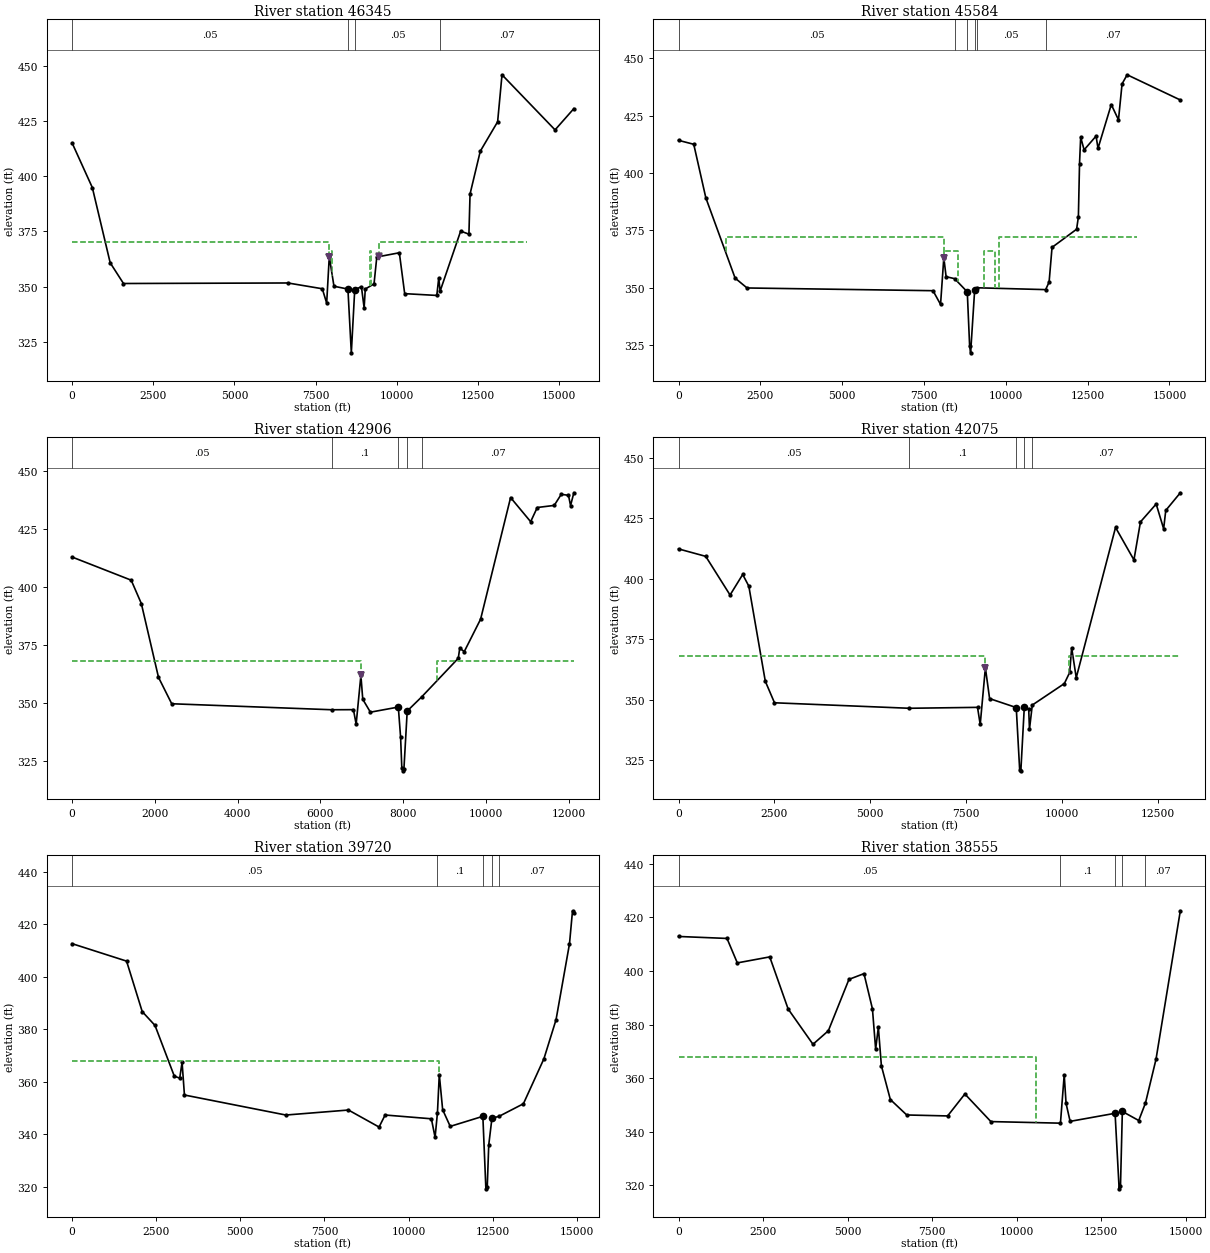
Type RM Length L Ch R = 1 ,46345   ,777.22,761,653.03
BEGIN DESCRIPTION:
US Bridge
LOB - Kaufman 5 East, ROB - Kaufman 5 West
END DESCRIPTION:
XS GIS Cut Line= 6
2594925.64877222 6913141.96341742592858.618785566911263.34611164
2589469.304369976907767.00107023 2588993.98773536907233.66191381
2588610.966519716907017.985507892584191.103968386902062.58859456
#Sta/Elev= 30
       0  415.15  624.59  394.86 1174.23  360.77 1583.96  351.38 6647.79  351.62
 7707.65     349 7842.53  342.49 7922.46  363.58 8067.34  350.14 8496.97  348.85
 8601.87  319.94 8706.76  348.58 8912.49  349.94 8996.52  340.32 9031.49  348.89
 9301.28   351.2 9386.21  363.3910080.67  365.3210245.54  346.7811234.77  345.97
11294.72  353.9111336.75   347.911969.19  375.1312223.99  373.7712258.97  391.98
12573.72  411.36 13108.3  424.72 13243.2  446.0314876.92  421.0415456.47  430.69
#Mann= 4 ,-1 , 0
       0     .05       0 8496.97    .045       0 8706.76     .05       0
11336.75     .07       0
Levee=-1,7922.46,363.58,-1,9441.17,363.87,,
#XS Ineff= 4 ,-1
       0 7922.46     370 7922.46    8018     366  9176.9 9212.61     366
 9441.17   14000     370
Permanent Ineff=
       F       F       F       F
Bank Sta=8496.97,8706.76
XS Rating Curve= 0 ,0
Exp/Cntr=0.5,0.3

Type RM Length L Ch R = 1 ,45584   ,967.31,1332.53,361.44
BEGIN DESCRIPTION:
DS Bridge
LOB - Kaufman 5 East
ROB IFA station 9792: flow expansion due to Kaufman 5 West levee upstream
END DESCRIPTION:
XS GIS Cut Line= 6
2595154.815308636912891.963589312589835.605474646907426.51093756
2589282.320491976906482.568599732588894.303223396906370.30307622
 2587378.35317136904669.299588472584516.62497088 6901975.7829939
#Sta/Elev= 30
       0  414.27  464.79  412.55  834.63  389.18 1729.24  354.22 2094.08  349.93
 7776.47  348.74 8006.28  342.75  8106.2  363.12 8176.15  354.84 8436.37  353.99
 8823.08  348.23 8895.26  324.59 8925.18  321.66 9048.47  348.95 9106.64  350.02
 11217.9  349.21 11323.3   352.511413.25  367.6212163.25  375.5212218.25  380.88
12253.25  404.1712288.25  415.6112393.25  410.1212758.25  416.1212818.25   410.8
13223.25  429.8713443.25  423.2113553.25  438.8813708.25  442.8415333.25  431.85
#Mann= 6 ,-1 , 0
       0     .05       0 8436.37      .1       0 8823.08    .045       0
 9048.47      .1       0 9106.64     .05       0 11217.9     .07       0
Levee=-1,8106.29,363.12,0,,,,
#XS Ineff= 4 ,-1
    1440 8106.29     372 8106.29    8533     366    9327    9668     366
    9792   14000     372
Permanent Ineff=
       F       F       F       F
Bank Sta=8823.08,9048.47
XS Rating Curve= 0 ,0
Exp/Cntr=0.5,0.3

Type RM Length L Ch R = 1 ,42906   ,907.64,831.04,782.67
BEGIN DESCRIPTION:
LOB - Kaufman 5 East
ROB IFA station 8821: flow expansion due to Kaufman 5 West levee upstream
END DESCRIPTION:
XS GIS Cut Line= 3
2594297.772075226909371.631391142593845.622388976907306.79825048
2585514.888722396901747.91862023
#Sta/Elev= 30
       0  412.86 1429.16  402.89 1674.02  392.84 2088.78  361.07 2408.61  349.69
  6275.2  347.11 6801.43  347.15  6866.4  340.89 6981.34  361.89 7026.32  351.62
 7211.23  346.06  7885.9  348.27 7940.87  335.31 7970.86  321.87 7995.85  320.81
 8020.83   321.5 8100.79  346.56 8448.57  352.61 9335.21  369.26  9370.2  373.59
 9480.15  372.16 9874.96  386.1110599.62  438.46 11084.4  428.0711244.32  434.18
11654.13  435.0811824.05  439.8611998.97  439.4312048.95  435.0212128.91  440.52
#Mann= 5 ,-1 , 0
       0     .05       0  6275.2      .1       0  7885.9    .045       0
 8100.79      .1       0 8448.57     .07       0
Levee=-1,6981.34,361.89,0,,,,
#XS Ineff= 2 , 0
       0 6981.34     368    8821       0     368
Permanent Ineff=
       F       F
Bank Sta=7885.9,8100.79
XS Rating Curve= 0 ,0
Exp/Cntr=0.3,0.1

Type RM Length L Ch R = 1 ,42075   ,1066.9,1219.97,1124.41
BEGIN DESCRIPTION:
LOB - Kaufman 5 East
ROB IFA station 10178: flow expansion due to Kaufman 5 West levee upstream
END DESCRIPTION:
XS GIS Cut Line= 4
2594558.188549136909284.82579048 2594527.03572436906218.12949607
2592143.249809476904619.118914562585655.947823466901617.71021923
#Sta/Elev= 30
       0  412.37  709.27  409.29 1343.62   393.3 1673.28  401.79 1833.12  396.96
 2262.68  357.62 2502.44  348.72 6018.52  346.45 7796.83  346.83 7866.81  339.75
 8001.77  363.17 8111.75  350.45 8806.54  346.75 8896.52  320.78 8926.51  320.57
 9016.48  346.92 9131.45  345.99 9151.44  337.76 9224.91  347.7810061.18  356.67
10201.14  361.3110251.12  371.4910371.09   359.111395.79  421.2411875.65  407.82
 12045.6  423.5412455.48  430.9412650.42   420.712705.41  428.29 13085.3  435.59
#Mann= 5 ,-1 , 0
       0     .05       0 6018.52      .1       0 8806.54    .045       0
 9016.48      .1       0 9224.91     .07       0
Levee=-1,8001.7,363.18,0,,,,
#XS Ineff= 2 , 0
       0  8001.7     368   10178       0     368
Permanent Ineff=
       F       F
Bank Sta=8806.54,9016.48
XS Rating Curve= 0 ,0
Exp/Cntr=0.3,0.1

Type RM Length L Ch R = 1 ,39720   ,1143.14,1165.48,1067.03
BEGIN DESCRIPTION:
LOB IFA station 10914.07: flow expansion due to Kaufman 5 East levee upstream
END DESCRIPTION:
XS GIS Cut Line= 3
2602267.662631476905711.986807562589421.712929736901070.54235031
2588296.712883136900514.98670289
#Sta/Elev= 30
       0  412.69 1619.85  406.03  2084.8  386.78 2464.77   381.5 3039.71  362.12
  3199.7  361.42 3269.69  367.41 3339.69  354.96 6354.37  347.32 8214.17  349.23
 9124.13  342.74 9304.13  347.3310679.08  345.8910789.08  338.8110859.07  348.11
10914.07  362.7611014.07  349.3611239.06  342.9912209.03  346.8312299.02  319.17
12339.02  319.7212384.02  335.9112479.02  346.0912694.01  346.8513413.98  351.62
 14023.9  368.7814383.83  383.6614783.76  412.6214873.74  425.2314913.73   424.2
#Mann= 5 ,-1 , 0
       0     .05       010859.07      .1       012209.03    .045       0
12479.02      .1       012694.01     .07       0
#XS Ineff= 2 , 0
       010914.07     368               0
Permanent Ineff=
       F       F
Bank Sta=12209.03,12479.02
XS Rating Curve= 0 ,0
Exp/Cntr=0.3,0.1

Type RM Length L Ch R = 1 ,38555   ,983.25,981.1,978.78
BEGIN DESCRIPTION:
LOB IFA station 10565: flow expansion due to Kaufman 5 East levee upstream
END DESCRIPTION:
XS GIS Cut Line= 5
2602562.801476886905191.153531642597993.476297976901987.08710514
 2592347.91212986900854.886613642589502.070708636900042.74683373
2588998.101900316899834.43130548
#Sta/Elev= 30
       0   412.9 1433.91  412.16 1738.68  403.03 2697.96  405.27 3242.55  385.81
    3977  372.64 4431.64  377.69 5041.17  396.88 5485.82  399.02 5735.69  385.88
 5830.66  370.86 5910.63  378.99  6000.6  364.61  6265.5  352.01 6750.32  346.25
 7959.88  345.89 8469.69  354.08 9239.39  343.78 11297.2  343.1911408.55  361.21
11463.54  350.5511583.52  343.8612913.26  346.8813033.23  318.6713073.23   319.7
13128.22  347.5613613.12  344.1813812.12  350.7114123.02  366.9914843.32  422.49
#Mann= 5 ,-1 , 0
       0     .05       0 11297.2      .1       012913.26    .045       0
13128.22      .1       013812.12     .07       0
#XS Ineff= 2 , 0
           10565     368
Permanent Ineff=
       F       F
Bank Sta=12913.26,13128.22
XS Rating Curve= 0 ,0
Exp/Cntr=0.3,0.1

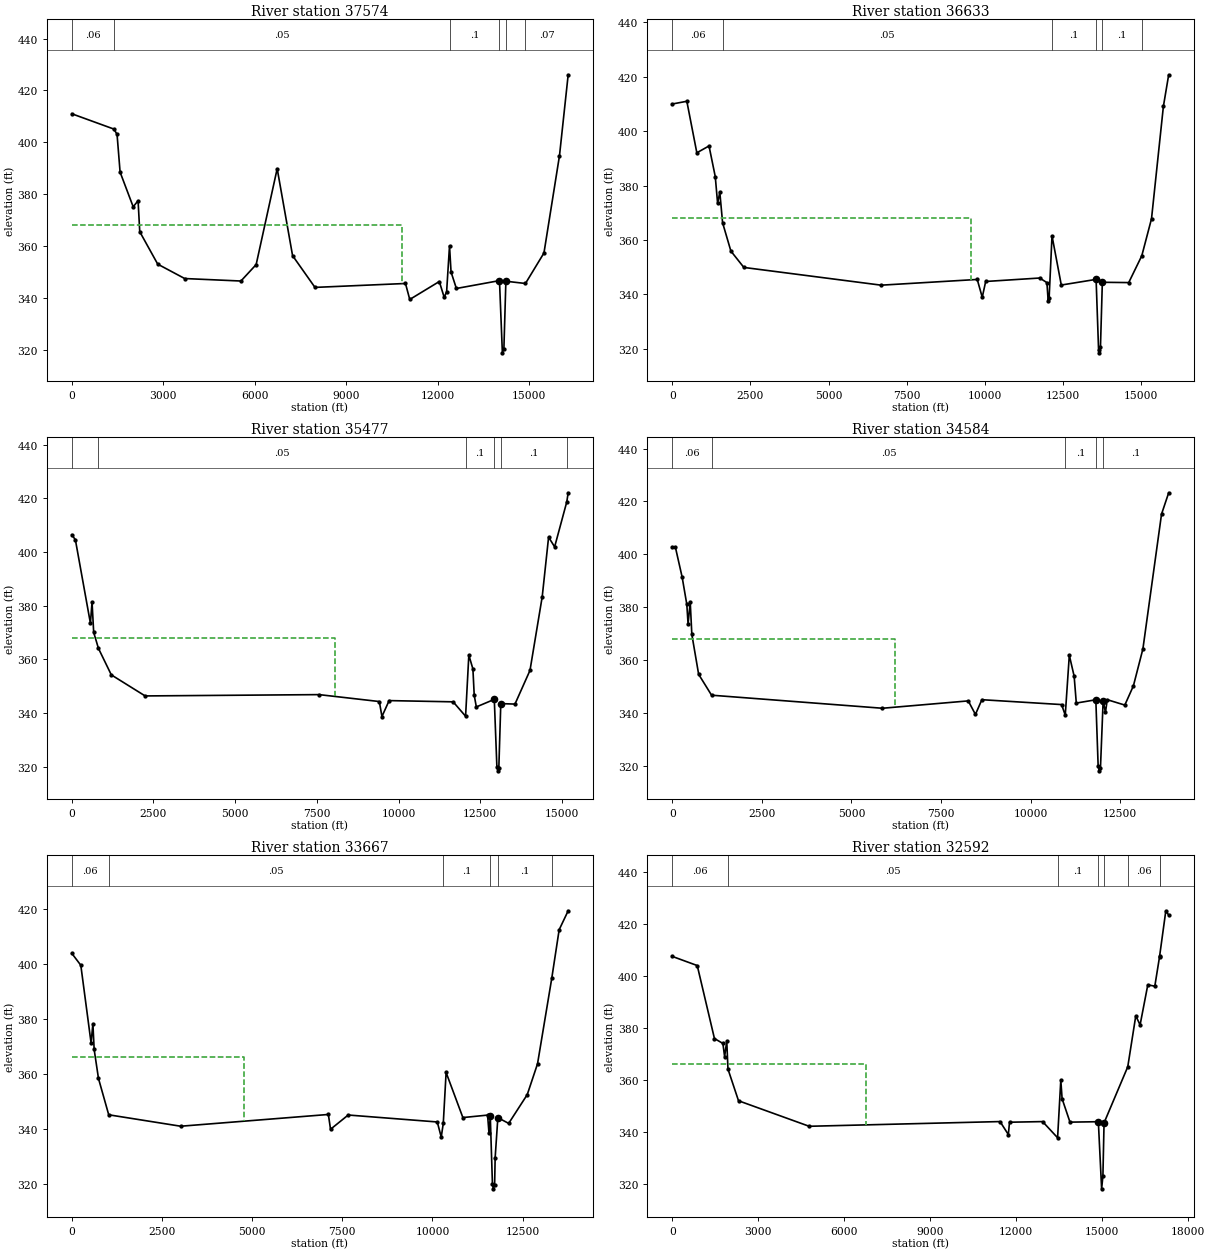
Type RM Length L Ch R = 1 ,37574   ,972.94,940.81,923.97
BEGIN DESCRIPTION:
LOB IFA station 10820: flow expansion due to Kaufman 5 East levee upstream
END DESCRIPTION:
XS GIS Cut Line= 3
2604962.107045736901705.042393642592475.634643396899865.98472007
2588949.490777066898876.09792031
#Sta/Elev= 30
       0     411 1379.29   405.1 1484.55  403.07 1584.52  388.47 2014.38  375.08
 2174.34  377.46 2229.32  365.47 2819.14  352.95 3703.87   347.4  5548.3  346.44
 6048.15  352.79 6737.93  389.81 7242.77  356.24 7977.55  343.9810946.83  345.49
 11086.8  339.3212056.57  346.2512216.53  340.1412296.51  342.2912391.32  360.05
12441.48  349.9412616.44  343.5614030.51   346.614125.45  318.7214175.41  320.39
14240.37  346.3614882.48  345.4915489.55  357.2615999.21  394.8516284.03  426.05
#Mann= 6 ,-1 , 0
       0     .06       0 1379.29     .05       012391.32      .1       0
14030.51    .045       014240.37      .1       014882.48     .07       0
#XS Ineff= 2 , 0
           10820     368
Permanent Ineff=
       F       F
Bank Sta=14030.51,14240.37
XS Rating Curve= 0 ,0
Exp/Cntr=0.3,0.1

Type RM Length L Ch R = 1 ,36633   ,1154.27,1155.74,1172.84
BEGIN DESCRIPTION:
LOB IFA station 9561: flow expansion due to Kaufman 5 East levee upstream
END DESCRIPTION:
XS GIS Cut Line= 3
2604760.718012816900843.931254982592673.594221226898885.19435881
2589130.046190226898042.76461323
#Sta/Elev= 30
       0  409.99  464.99  410.99  784.99  392.06 1174.98  394.57 1374.98  383.29
 1449.98  373.45 1519.98  377.61 1609.26  366.34 1874.97  355.93 2289.97  349.92
 6684.81   343.4 9759.74   345.5 9919.74  338.9510029.74  344.7611759.74  346.03
11989.74  344.3312029.74  337.6212059.74  338.5712152.89  361.5212449.58  343.45
13563.71  345.5313643.65  319.4413668.63  318.53 13703.6  320.7913763.55  344.46
14607.89  344.3515026.13   354.215337.32  367.8215717.03  409.0815886.89  420.73
#Mann= 6 ,-1 , 0
       0     .06       0 1609.26     .05       012152.89      .1       0
13563.71    .045       013763.55      .1       015026.13     .07       0
#XS Ineff= 2 , 0
            9561     368
Permanent Ineff=
       F       F
Bank Sta=13563.71,13763.55
XS Rating Curve= 0 ,0
Exp/Cntr=0.3,0.1

Type RM Length L Ch R = 1 ,35477   ,895.92,893.6,873.34
BEGIN DESCRIPTION:
LOB IFA station 8052: flow expansion due to Kaufman 5 East levee upstream
END DESCRIPTION:
XS GIS Cut Line= 4
2604429.717034386899892.728432982591809.015241716897517.95693581
2591440.133105476897382.915867312589505.046424466897084.43122806
#Sta/Elev= 30
       0  406.47  109.98   404.6  569.88  373.49  619.86  381.32  669.85  370.08
  816.01   364.1 1209.73  354.23  2244.5  346.38 7568.38  346.87 9413.01  344.29
    9493   338.7 9712.95  344.6411672.57  344.1812053.05  338.8112152.48   361.6
12277.45  356.4412317.45  346.6112382.43  342.2812931.85   345.113011.41  319.89
13041.25  318.4513071.08  319.6513130.76  343.5213564.86  343.3414024.41   355.9
14399.04  383.3914593.85  405.5914778.67  401.9615150.79  418.7615193.27  422.13
#Mann= 6 ,-1 , 0
       0     .06       0  816.01     .05       012053.05      .1       0
12931.85    .045       013130.76      .1       015150.79     .07       0
#XS Ineff= 2 , 0
            8052     368
Permanent Ineff=
       F       F
Bank Sta=12931.85,13130.76
XS Rating Curve= 0 ,0
Exp/Cntr=0.3,0.1

Type RM Length L Ch R = 1 ,34584   ,965.72,916.32,871.52
BEGIN DESCRIPTION:
LOB IFA station 6222: flow expansion due to Kaufman 5 East levee upstream
END DESCRIPTION:
XS GIS Cut Line= 4
2603713.571485066898623.197179392592125.906668316896679.66792998
2591781.105192566896562.77708764 2590054.35175636896352.83426607
#Sta/Elev= 30
       0  402.75      85   402.8  274.99  391.41  404.98  381.12  439.98  373.75
  499.98  382.01  544.98  369.81  734.97  354.74 1095.71  346.86 5864.76  341.93
 8259.65  344.71 8459.65   339.6 8639.65  345.1610864.65  343.3210966.45  339.31
11079.65  361.9411214.65  354.0311274.65  343.8911819.47  345.13 11884.3  320.18
11914.23   318.311949.14  319.4112023.95  344.8412088.78  340.3312138.71  345.16
12628.52  343.1312868.42  350.3913133.32  364.3213653.12  415.2113853.04  423.29
#Mann= 5 ,-1 , 0
       0     .06       0 1095.71     .05       010966.45      .1       0
11819.47    .045       012023.95      .1       0
#XS Ineff= 2 , 0
            6222     368
Permanent Ineff=
       F       F
Bank Sta=11819.47,12023.95
XS Rating Curve= 0 ,0
Exp/Cntr=0.3,0.1

Type RM Length L Ch R = 1 ,33667   ,956.52,1075.45,1196.68
BEGIN DESCRIPTION:
LOB IFA station 4788: flow expansion due to Kaufman 5 East levee upstream
END DESCRIPTION:
XS GIS Cut Line= 2
2603705.758836646897109.742201062590039.768452146895487.20902881
#Sta/Elev= 30
       0  403.89  249.95  399.55  534.88  371.25  584.87  378.29  619.86   368.9
  739.84  358.34 1023.68  345.12 3019.33  340.96  7113.4  345.24 7173.39  339.85
 7663.27  345.0410132.77  342.5110242.75  337.0110299.28  341.9910377.72  360.52
10842.63  344.11 11527.5  345.0111567.49  338.3311602.49  344.5311662.47   319.8
11687.47  318.1711722.46  319.4611737.46   329.511812.44  344.0812112.39  341.99
12627.29  352.4612912.23  363.6813306.29  394.7513512.11  412.4813762.06  419.38
#Mann= 6 ,-1 , 0
       0     .06       0 1023.68     .05       010299.28      .1       0
11602.49    .045       011812.44      .1       013306.29     .07       0
#XS Ineff= 2 , 0
            4788     366
Permanent Ineff=
       F       F
Bank Sta=11602.49,11812.44
XS Rating Curve= 0 ,0
Exp/Cntr=0.3,0.1

Type RM Length L Ch R = 1 ,32592   ,1033.05,970.38,903.65
BEGIN DESCRIPTION:
LOB IFA station 6774: flow expansion due to Kaufman 5 East levee upstream
END DESCRIPTION:
XS GIS Cut Line= 4
2607358.431977476895639.950521232592563.657433236894877.43629822
2592266.782370816894635.248790472590148.135361396894543.05737381
#Sta/Elev= 30
       0  407.41  869.97   403.9 1469.94  375.87 1764.93  373.98 1824.93  368.93
 1899.93  374.88 1941.71  364.14 2309.91  351.96 4774.79  342.1611434.53  343.97
11724.53  338.9811764.53  343.7212919.53  343.96 13442.5  337.7513554.53  359.94
13599.53  352.7513874.53  343.7514864.29  343.9214978.73  318.1315023.51  323.08
15063.31  343.4715890.45  365.0116170.65  384.6116320.34  381.0816589.81   396.5
16834.33  395.9716998.81  407.25   17001  407.4417218.58  424.9417318.38  423.28
#Mann= 8 ,-1 , 0
       0     .06       0 1941.71     .05       0 13442.5      .1       0
14864.29    .045       015063.31      .1       015890.45     .06       0
16998.81      .1       0   17001     .07       0
#XS Ineff= 2 , 0
            6774     366
Permanent Ineff=
       F       F
Bank Sta=14864.29,15063.31
XS Rating Curve= 0 ,0
Exp/Cntr=0.3,0.1

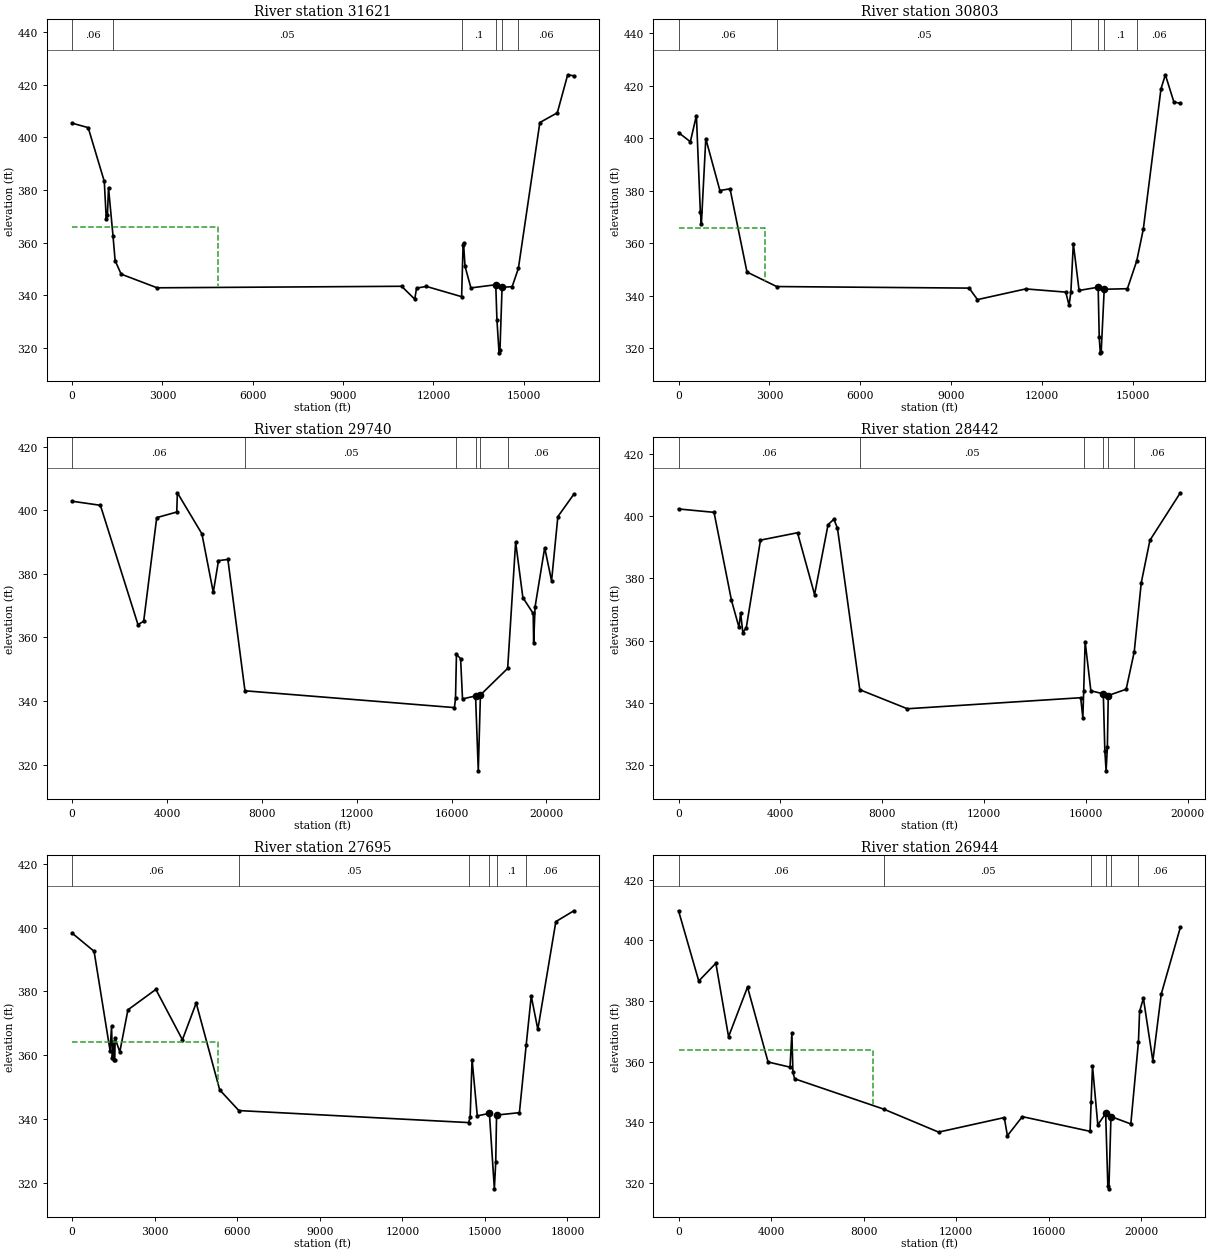
Type RM Length L Ch R = 1 ,31621   ,826.23,818.59,801.59
BEGIN DESCRIPTION:
LOB IFA station 4855: flow expansion due to Kaufman 5 East levee upstream
END DESCRIPTION:
XS GIS Cut Line= 3
2606934.925606646894297.242248642591852.420666726893856.31957406
2590310.895534566894174.13389906
#Sta/Elev= 30
       0  405.43  534.96  403.73 1069.93  383.31 1134.92   369.2 1174.92  370.53
 1209.92  380.94 1360.52  362.45  1429.9  353.19 1629.89  348.06 2824.81  342.87
 10944.2  343.4511379.16  338.5411439.15  342.7511764.12   343.412935.99   339.5
12983.99  359.0912998.99  359.8413048.98  351.0313243.96  342.8314068.88  344.04
14108.87  330.5714178.86  318.1614208.86  319.2114278.85  343.0314613.82  343.32
 14819.8  350.2215533.51  405.6716113.17  409.3516457.95  423.8116662.79  423.41
#Mann= 6 ,-1 , 0
       0     .06       0 1360.52     .05       012935.99      .1       0
14068.88    .045       014278.85      .1       0 14819.8     .06       0
#XS Ineff= 2 , 0
            4855     366
Permanent Ineff=
       F       F
Bank Sta=14068.88,14278.85
XS Rating Curve= 0 ,0
Exp/Cntr=0.3,0.1

Type RM Length L Ch R = 1 ,30803   ,1047.94,1062.87,1071.08
BEGIN DESCRIPTION:
LOB IFA station 2856: flow expansion due to Kaufman 5 East levee upstream
END DESCRIPTION:
XS GIS Cut Line= 3
 2606794.78677936892649.117264062591417.311956886893120.90962756
2590430.253235476893772.65799598
#Sta/Elev= 30
       0  402.17  389.99  398.67  589.99  408.62  719.99  371.94  754.99  367.48
  899.98  399.83 1364.97  380.09 1699.97  380.75 2259.96  349.03 3240.56  343.51
 9594.75  342.92 9869.75  338.5411464.75  342.6112784.75  341.3912894.75  336.35
12954.41   341.513034.75  359.8913224.75  342.0213854.75  343.2713889.75  324.24
13924.75  318.2613954.75   318.614054.75  342.4814819.75  342.6915127.73  353.24
15344.75  365.3515928.72  418.8216073.45  424.1816352.92  413.88 16567.5  413.25
#Mann= 6 ,-1 , 0
       0     .06       0 3240.56     .05       012954.41      .1       0
13854.75    .045       014054.75      .1       015127.73     .06       0
#XS Ineff= 2 , 0
            2856     366
Permanent Ineff=
       F       F
Bank Sta=13854.75,14054.75
XS Rating Curve= 0 ,0
Exp/Cntr=0.3,0.1

Type RM Length L Ch R = 1 ,29740   ,1181.37,1297.72,1407.87
BEGIN DESCRIPTION:
ROB IFA station 18701.54: flow contraction due to natural high ground
END DESCRIPTION:
XS GIS Cut Line= 2
2609776.730946636891513.006347312588630.897582226892158.83970131
#Sta/Elev= 30
       0  402.87 1194.75  401.59 2779.43  364.03 3019.38  365.11 3569.27  397.71
 4414.09  399.47 4439.09  405.53 5473.87  392.62 5953.77   374.2 6173.72  384.17
 6568.64  384.56 7289.66  343.2216121.74  337.9316166.73  340.8516206.39  354.69
16381.69  353.3216461.69  340.6517011.65  341.6117126.64  318.0317216.63  341.91
18365.07  350.2618701.54  390.0119006.51  372.5419441.48  367.5519461.48  358.33
19521.48  369.6519926.45  388.2420216.43  377.8120481.41  398.0221156.37  405.08
#Mann= 6 ,-1 , 0
       0     .06       0 7289.66     .05       016206.39      .1       0
17011.65    .045       017216.63      .1       018365.07     .06       0
#XS Ineff= 2 , 0
                        18701.54          390.01
Permanent Ineff=
       F       F
Bank Sta=17011.65,17216.63
XS Rating Curve= 0 ,0
Exp/Cntr=0.3,0.1

Type RM Length L Ch R = 1 ,28442   ,723.51,747.4,763.07
XS GIS Cut Line= 4
 2609380.89774886890846.339701642593331.783849726890922.40582247
2591296.384049136890446.987481982589721.86980972 6890446.3395174
#Sta/Elev= 30
       0  402.33 1394.94  401.24 2079.91  372.94  2374.9  364.27  2439.9  368.95
 2524.89   362.6 2659.89  364.08 3219.87  392.31 4674.79  394.68 5344.73  374.81
 5874.69   397.3 6104.67  399.03 6244.66  396.09 7120.82  344.21 8989.51  338.09
15799.51  341.6415884.51  335.1715917.22  343.6615974.51  359.6916199.16  343.86
16688.01   342.916747.87  324.6616797.75  318.1316847.63  325.6416882.55  342.35
 17585.9  344.3617902.84  356.3818179.58  378.6418519.45  392.2619713.98  407.53
#Mann= 6 ,-1 , 0
       0     .06       0 7120.82     .05       015917.22      .1       0
16688.01    .045       016882.55      .1       017902.84     .06       0
#XS Ineff= 2 , 0
Permanent Ineff=
       F       F
Bank Sta=16688.01,16882.55
XS Rating Curve= 0 ,0
Exp/Cntr=0.3,0.1

Type RM Length L Ch R = 1 ,27695   ,712.16,750.47,644.52
BEGIN DESCRIPTION:
LOB IFA station 5308: flow expansion due to natural high ground upstream
END DESCRIPTION:
XS GIS Cut Line= 4
2608185.411622726890290.089501812593686.855974216890290.07801889
2591493.238314236889689.177645892590034.369840896889691.13138214
#Sta/Elev= 30
       0   398.3  799.92  392.58 1379.86  361.43 1434.86  368.98 1464.85  359.16
 1499.85  364.23 1519.85  358.38 1549.85  358.31 1564.84  365.21 1734.83     361
  2029.8   374.2  3044.7  380.61 4009.61  364.81 4509.56  376.35 5364.48  349.07
 6059.67  342.5814407.11  338.81 14463.6  340.5214533.59  358.6114723.55  340.92
15163.45   341.715343.41  318.01 15393.4  326.4115423.39  341.1716253.21  341.92
16501.62  363.3116683.06  378.5216922.91  368.07 17577.4   401.918231.88   405.3
#Mann= 6 ,-1 , 0
       0     .06       0 6059.67     .05       014407.11      .1       0
15163.45    .045       015423.39      .1       016501.62     .06       0
#XS Ineff= 2 , 0
            5308     364
Permanent Ineff=
       F       F
Bank Sta=15163.45,15423.39
XS Rating Curve= 0 ,0
Exp/Cntr=0.3,0.1

Type RM Length L Ch R = 1 ,26944   ,799.77,731.95,575.72
BEGIN DESCRIPTION:
LOB IFA station 8402: flow contraction due to natural high ground downstream
END DESCRIPTION:
XS GIS Cut Line= 5
2611827.732093976888284.035443072607196.270884476888490.88050181
2594067.997600396889634.380839482592496.817015726889321.88080831
2590219.274326736889437.78444789
#Sta/Elev= 30
       0  409.79  874.26  386.61 1613.63  392.48 2163.16  368.22 2982.48  384.61
 3871.74  359.88 4821.05  358.18 4901.03  369.45 4946.02  356.43 5021.01  354.34
 8878.68  344.3111244.86  336.7414084.31  341.5414219.28  335.5514864.16  341.85
17793.86     33717839.72  346.7417898.69  358.5618128.24  339.1218467.58  342.91
18562.39  318.9518607.31  318.0218697.13  341.8719555.45  339.4419885.43  366.51
19934.71  376.5720099.39  380.9220508.59  360.2320872.87  382.3521696.26  404.29
#Mann= 6 ,-1 , 0
       0     .06       0 8878.68     .05       017839.72      .1       0
18467.58    .045       018697.13      .1       019885.43     .06       0
#XS Ineff= 2 , 0
            8402     364
Permanent Ineff=
       F       F
Bank Sta=18467.58,18697.13
XS Rating Curve= 0 ,0
Exp/Cntr=0.3,0.1

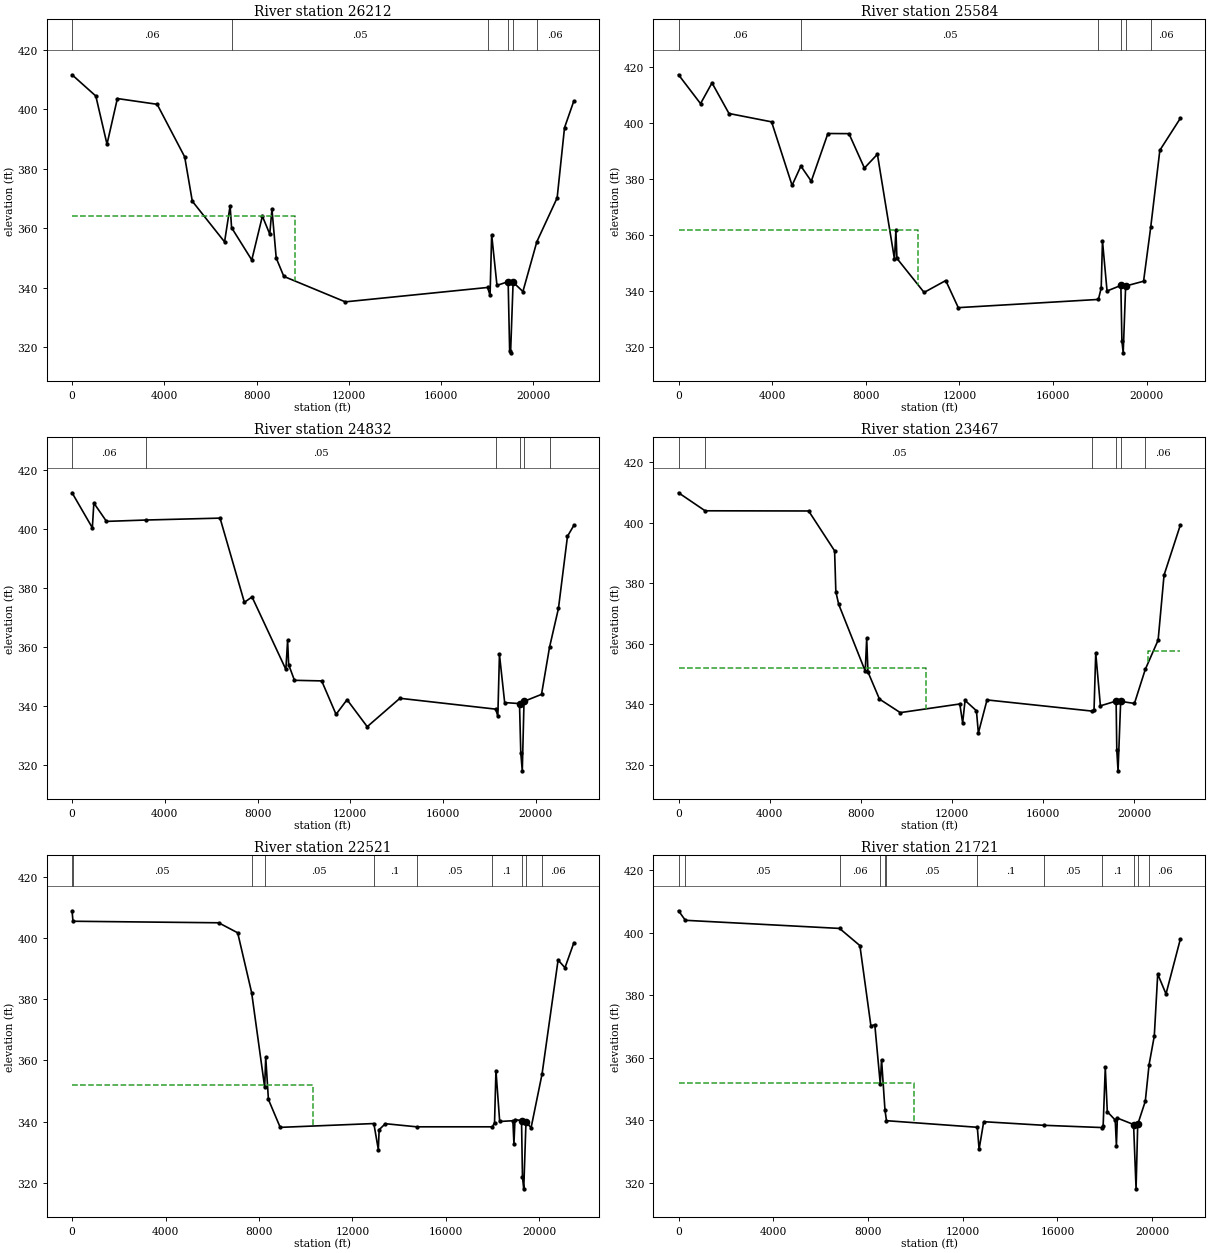
Type RM Length L Ch R = 1 ,26212   ,640.76,628.96,608.64
BEGIN DESCRIPTION:
LOB IFA station 9658: flow contraction due to natural high ground downstream
END DESCRIPTION:
XS GIS Cut Line= 2
2612128.934903646886531.613422972590517.650370396889104.86680664
#Sta/Elev= 30
       0  411.56 1029.95  404.43 1514.93  388.25 1964.91  403.58 3689.84  401.65
 4884.78  383.99 5214.76  369.11 6614.68  355.44 6854.67  367.54  6918.6  360.22
 7794.61  349.37 8254.59  364.09 8574.59  358.06 8669.59  366.43 8854.59  350.02
 9184.59  343.8611849.59  335.3118022.85  340.1418129.59  337.4718199.59  357.86
18429.59  340.8418914.59  342.0918979.59  318.7719019.59  318.1919129.59  341.91
19554.59  338.7720159.86  355.5221039.59  370.2221359.59   393.821764.59  402.78
#Mann= 6 ,-1 , 0
       0     .06       0  6918.6     .05       018022.85      .1       0
18914.59    .045       019129.59      .1       020159.86     .06       0
#XS Ineff= 2 , 0
            9658     364
Permanent Ineff=
       F       F
Bank Sta=18914.59,19129.59
XS Rating Curve= 0 ,0
Exp/Cntr=0.3,0.1

Type RM Length L Ch R = 1 ,25584   ,776.67,751.9,730.89
BEGIN DESCRIPTION:
LOB IFA station 10224: flow contraction due to natural high ground downstream
END DESCRIPTION:
XS GIS Cut Line= 2
2611853.773708556885106.951902232590701.603086476888562.36821973
#Sta/Elev= 30
       0  417.24  939.89  406.94 1429.84  414.34 2154.76  403.42 3974.57  400.44
 4849.48  377.78 5225.59  384.66  5669.4  379.26 6379.32  396.28 7279.23  396.23
 7939.16  383.95 8494.08  388.87 9223.93  351.41 9283.92  361.73 9328.91   351.7
10488.69  339.5611413.51   343.8 11948.4  334.1317933.65  337.0618052.54  341.12
18107.54  357.9418302.54  340.0718892.54  342.0618937.54  322.2718992.54     318
19097.54  341.8419862.54  343.56 20170.7  363.0120557.54  390.2921432.54   401.7
#Mann= 6 ,-1 , 0
       0     .06       0 5225.59     .05       017933.65      .1       0
18892.54    .045       019097.54      .1       0 20170.7     .06       0
#XS Ineff= 2 , 0
           10224     362
Permanent Ineff=
       F       F
Bank Sta=18892.54,19097.54
XS Rating Curve= 0 ,0
Exp/Cntr=0.3,0.1

Type RM Length L Ch R = 1 ,24832   ,1358.25,1364.88,1358.12
XS GIS Cut Line= 2
2611894.422905476883211.363173722590766.707286976887922.17724289
#Sta/Elev= 30
       0  412.32  874.86  400.43  939.85  408.84 1484.76  402.61 3171.52  403.07
 6383.98  403.72 7433.81  375.14 7763.76  376.98 9223.49  352.37 9298.48  362.23
 9343.47     354 9593.42  348.6810768.19  348.4811388.07  337.1311862.98   342.1
12732.81  332.9414142.53  342.5818273.67   338.918367.09  336.5118437.09  357.46
18662.09  341.1319302.09  340.7819357.09   324.119422.09  317.9619497.09  341.54
20252.09  343.9120597.19  359.8920982.09  373.0721372.09  397.5721647.09  401.25
#Mann= 6 ,-1 , 0
       0     .06       0 3171.52     .05       018273.67      .1       0
19302.09    .045       019497.09      .1       020597.19     .06       0
#XS Ineff= 2 , 0
Permanent Ineff=
       F       F
Bank Sta=19302.09,19497.09
XS Rating Curve= 0 ,0
Exp/Cntr=0.3,0.1

Type RM Length L Ch R = 1 ,23467   ,942.26,945.95,935.47
BEGIN DESCRIPTION:
LOB IFA station 10875: flow expansion due to natural high ground upstream
ROB IFA station 20632.04: flow contraction due to natural high ground
END DESCRIPTION:
XS GIS Cut Line= 2
2611653.252456056881984.744563982590119.055367056886662.84905289
#Sta/Elev= 30
       0  409.98 1167.46  404.02 5714.05  403.96 6853.86  390.77 6908.85  377.22
 7033.83  373.08 8198.63  350.99 8263.62  361.83 8318.61  350.71 8823.51  341.73
 9738.33  337.2512352.82  340.11 12477.8  333.8212582.78  341.2913082.68  337.87
13167.66   330.513547.59  341.4518167.38  337.7518247.04  338.0518322.04  356.98
18527.04  339.4919217.04  341.0719247.04  324.8619302.04  317.9919417.04  340.97
20022.04  340.29 20497.7  351.5521062.04  361.2321322.04  382.7422037.04  399.29
#Mann= 6 ,-1 , 0
       0     .06       0 1167.46     .05       018167.38      .1       0
19217.04    .045       019417.04      .1       0 20497.7     .06       0
#XS Ineff= 2 , 0
           10875     35220632.04          357.77
Permanent Ineff=
       F       F
Bank Sta=19217.04,19417.04
XS Rating Curve= 0 ,0
Exp/Cntr=0.3,0.1

Type RM Length L Ch R = 1 ,22521   ,792.48,799.63,800.35
BEGIN DESCRIPTION:
LOB IFA station 10301: flow expansion due to natural high ground upstream
END DESCRIPTION:
XS GIS Cut Line= 2
2611339.689106816880927.524893642590389.888814886885662.84908439
#Sta/Elev= 30
       0  408.81   38.57  405.39 6274.47  404.89 7089.39  401.62 7686.85  382.07
 8244.63  351.19 8289.28  361.02 8404.28  347.21 8909.26  338.0912917.72  339.34
13109.14  330.8413144.14  337.3313409.13  339.2914752.93  338.2717994.29  338.27
18084.05  339.6718144.05  356.6418304.05  340.0118869.05  340.2618914.05  332.68
18959.05  340.6519239.05  340.2819279.05  321.8419334.05  318.0219429.05  339.74
19649.05  337.9920117.21  355.4920804.05  392.7321099.05  390.2221479.05  398.37
#Mann= 10 ,-1 , 0
       0     .06       0   38.57     .05       0 7686.85     .06       0
 8244.63     .05       012917.72      .1       014752.93     .05       0
17994.29      .1       019239.05    .045       019429.05      .1       0
20117.21     .06       0
#XS Ineff= 2 , 0
           10301     352
Permanent Ineff=
       F       F
Bank Sta=19239.05,19429.05
XS Rating Curve= 0 ,0
Exp/Cntr=0.3,0.1

Type RM Length L Ch R = 1 ,21721   ,755.29,626.6,592.48
BEGIN DESCRIPTION:
LOB IFA station 9932: flow expansion due to natural high ground upstream
END DESCRIPTION:
XS GIS Cut Line= 3
2611183.935481316880465.104230572591806.664852726884518.53313155
2590667.666474556885322.57122165
#Sta/Elev= 30
       0  407.03  287.68  403.98 6799.59  401.38 7658.83  395.88 8123.76  370.18
 8288.74  370.52 8519.83  351.47 8573.68  359.34 8718.85  343.16 8781.81  339.81
12617.68   337.712692.88  330.6512887.84  339.4915418.59  338.34 17864.8  337.62
17931.95  338.1418021.93  356.8718106.92  342.6818441.88  340.0318491.87  331.78
18531.87  340.6519216.77  338.5919321.76  317.9919391.75  338.6419711.71  346.03
19871.54  357.7720091.57  366.9220236.51  386.7620586.37   380.421191.12  397.93
#Mann= 12 ,-1 , 0
       0     .06       0  287.68     .05       0 6799.59     .06       0
 8519.83     .05       0 8718.85      .1       0 8781.81     .05       0
12617.68      .1       015418.59     .05       0 17864.8      .1       0
19216.77    .045       019391.75      .1       019871.54     .06       0
#XS Ineff= 2 , 0
            9932     352
Permanent Ineff=
       F       F
Bank Sta=19216.77,19391.75
XS Rating Curve= 0 ,0
Exp/Cntr=0.3,0.1

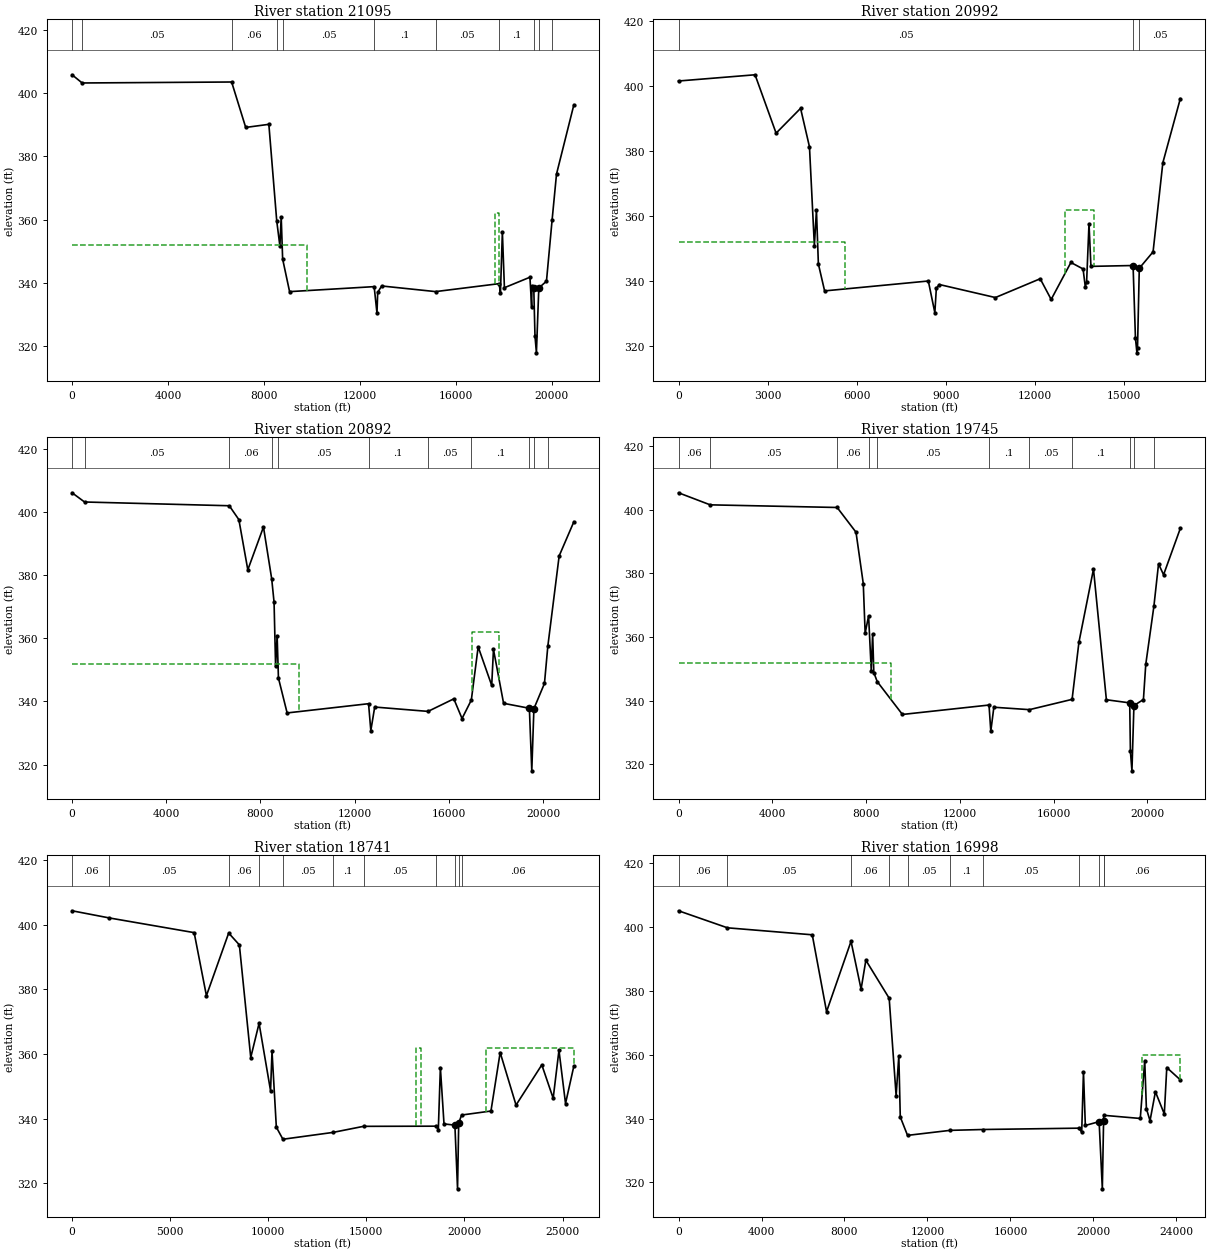
Type RM Length L Ch R = 1 ,21095   ,102.18,102.18,101.29
BEGIN DESCRIPTION:
LOB IFA station 9777: flow expansion due to natural high ground upstream
END DESCRIPTION:
XS GIS Cut Line= 5
2611124.633762646880242.536106142603231.653485646881893.62401131
2592599.012677486883639.824259062591754.477949226883947.93551947
2590882.944259236884746.18228257
#Sta/Elev= 30
       0   405.8  420.69  403.21 6652.16  403.52 7239.07  389.17 8203.92  390.15
 8532.87  359.63 8663.72  351.75 8718.69  360.96 8778.66  347.61 9068.54  337.31
12594.37  338.89 12711.9  330.5112741.89  337.0412906.81   339.115154.62  337.32
17803.39  339.8317859.68  336.9417939.65  356.2218024.61  338.55   19089  341.86
19158.92  332.57 19173.9  339.0419248.81  338.4719298.76  323.3719358.69  317.98
19458.57  338.4619778.13  340.6120012.64  359.9120196.98  374.45   20920  396.31
#Mann= 11 ,-1 , 0
       0     .06       0  420.69     .05       0 6652.16     .06       0
 8532.87      .1       0 8778.66     .05       012594.37      .1       0
15154.62     .05       017803.39      .1       019248.81    .045       0
19458.57      .1       020012.64     .06       0
#XS Ineff= 2 ,-1
       0    9777     352   17647   17813     362
Permanent Ineff=
       F       F
Bank Sta=19248.81,19458.57
XS Rating Curve= 0 ,0
Exp/Cntr=0.3,0.1

Type RM Length L Ch R = 1 ,20992   ,100.04,100.18,100.47
BEGIN DESCRIPTION:
LOB IFA station 5600: flow expansion due to natural high ground upstream
END DESCRIPTION:
XS GIS Cut Line= 6
2607092.583099726880980.739354152603216.006863396881794.72886789
2593241.707258226882864.644378982592225.466180476883666.69986148
2591701.437372896883860.947504482590920.187294976884574.48905639
#Sta/Elev= 30
       0  401.51 2577.48  403.42 3286.79  385.49 4111.09  393.11 4410.99  381.29
 4575.94  350.98 4645.92  361.85  4710.9  345.32 4920.83  337.05  8414.7  340.09
 8634.61  330.35 8684.59  337.85 8789.55     33910673.82  335.0112183.23  340.78
12553.08  334.4313217.82  345.7813627.66  343.7913702.63  338.3213747.61  339.86
13827.58   357.713892.56  344.5815312.07  344.8515391.92  322.5915441.82  318.03
15461.78  319.4515521.66     34415985.78  349.0416315.19  376.4116904.05   396.1
#Mann= 3 , 0 , 0
       0     .05       015312.07    .045       015521.66     .05       0
#XS Ineff= 2 ,-1
       0    5600     352   13017   13997     362
Permanent Ineff=
       F       F
Bank Sta=15312.07,15521.66
XS Rating Curve= 0 ,0
Exp/Cntr=0.3,0.1

Type RM Length L Ch R = 1 ,20892   ,1089.95,1147.33,1182.64
BEGIN DESCRIPTION:
LOB IFA station 9621: flow expansion due to natural high ground upstream
END DESCRIPTION:
XS GIS Cut Line= 6
2611054.003326486880036.169720982603200.360241136881695.83372448
2593202.381221386882768.289256722592175.905912136883578.42182282
2591648.396796556883773.959489482590647.701291386884685.41829647
#Sta/Elev= 30
       0  406.14  530.05  403.22 6675.33  402.03 7082.44  397.63  7462.3  381.72
 8127.05   395.3 8476.64  378.86 8576.87  371.46 8641.85  351.09 8706.82  360.86
 8762.77  347.42 9131.66  336.36 12589.4  339.2912685.27  330.76 12850.2  338.23
15114.79  336.8516208.89  340.8316558.75  334.5916952.69  340.4417243.48  357.32
17818.26  345.0917893.23  356.4918322.69  339.4119417.79  337.8419520.04  318.01
19609.65  337.7120058.05   345.720200.98  357.5120682.31  386.1321306.58  396.95
#Mann= 11 ,-1 , 0
       0     .06       0  530.05     .05       0 6675.33     .06       0
 8476.64      .1       0 8762.77     .05       0 12589.4      .1       0
15114.79     .05       016952.69      .1       019417.79    .045       0
19609.65      .1       020200.98     .06       0
#XS Ineff= 2 ,-1
       0    9621     352   17000   18137     362
Permanent Ineff=
       F       F
Bank Sta=19417.79,19609.65
XS Rating Curve= 0 ,0
Exp/Cntr=0.3,0.1

Type RM Length L Ch R = 1 ,19745   ,1044.98,1004.29,1000.61
BEGIN DESCRIPTION:
LOB IFA station 9075: flow expansion due to natural high ground upstream
END DESCRIPTION:
XS GIS Cut Line= 3
2610845.619884976878844.942444642591350.935777316882591.44971539
2590647.810871216883971.65791298
#Sta/Elev= 30
       0  405.35 1349.35  401.56 6764.94  400.73 7568.71  392.96 7878.66  376.83
 7958.65  361.23 8105.38  366.69  8218.6  349.51 8278.59  361.03 8328.58  348.87
 8473.78  346.03 9548.34  335.7113241.05  338.6713317.61  330.4613447.58  337.98
14965.53  337.2216783.66  340.4517076.86  358.4417696.73  381.3618246.62  340.33
19241.41  339.35 19271.4  324.1119336.39     31819421.37  338.5119826.29   340.4
19926.22  351.46 20273.4  369.73 20470.8  383.0120685.63   379.621400.07  394.16
#Mann= 11 ,-1 , 0
       0     .06       0 1349.35     .05       0 6764.94     .06       0
 8105.38      .1       0 8473.78     .05       013241.05      .1       0
14965.53     .05       016783.66      .1       019241.41    .045       0
19421.37      .1       0 20273.4     .06       0
#XS Ineff= 2 , 0
            9075     352
Permanent Ineff=
       F       F
Bank Sta=19241.41,19421.37
XS Rating Curve= 0 ,0
Exp/Cntr=0.3,0.1

Type RM Length L Ch R = 1 ,18741   ,1655.65,1742.82,1950.26
BEGIN DESCRIPTION:
ROB IFA station 211097: flow expansion due to natural high ground upstream
END DESCRIPTION:
XS GIS Cut Line= 5
2610763.852660066878378.988652142600975.607472816878665.28499556
2590955.961501646881722.923565312587971.051132896882582.00747706
 2585804.89962536882984.95319347
#Sta/Elev= 30
       0  404.36 1899.51  402.14 6223.41  397.59 6848.26  378.06 7982.98  397.46
 8527.83  393.79 9107.67  358.91 9532.54   369.510117.34  348.6210192.31   360.8
10412.23  337.3310747.09  333.59 13291.1   335.714855.49  337.5918569.04  337.64
   18669  336.5118773.96  355.8118958.89  338.3419513.67  337.9619648.62  318.23
19708.59  338.5719853.54  341.09 21352.1  342.3321821.55  360.46 22630.6  344.18
23944.29  356.6324523.83  346.29 24818.6  361.1525153.34  344.6625578.01  356.27
#Mann= 11 ,-1 , 0
       0     .06       0 1899.51     .05       0 7982.98     .06       0
 9532.54      .1       010747.09     .05       0 13291.1      .1       0
14855.49     .05       018569.04      .1       019513.67    .045       0
19708.59      .1       019853.54     .06       0
#XS Ineff= 2 ,-1
   17526   17801     362 21097.425578.01     362
Permanent Ineff=
       F       F
Bank Sta=19513.67,19708.59
XS Rating Curve= 0 ,0
Exp/Cntr=0.3,0.1

Type RM Length L Ch R = 1 ,16998   ,770.11,804.03,805.59
BEGIN DESCRIPTION:
ROB IFA station 22350: flow expansion due to natural high ground upstream
END DESCRIPTION:
XS GIS Cut Line= 4
2610698.685139466877870.605482562602837.471859316877925.18050465
2587972.020619146880692.107385472586988.65152289 6879984.7285509
#Sta/Elev= 30
       0  405.13 2358.92  399.79 6447.14   397.6 7136.85  373.52 8316.41  395.55
 8801.27  380.56  9031.2  389.6310155.87  377.7110490.77  347.1610620.74  359.69
10690.72   340.511040.61  334.7313090.02   336.314689.55  336.5719297.92  336.99
19437.86  335.7219522.83  354.6719612.79  337.8420277.54  339.0320432.47  317.97
20492.45  339.1320497.45  341.0222261.76  340.0322476.68  358.1722556.64  343.12
22731.58  339.3122991.45   348.4 23420.1  341.4323539.73  355.9924192.68  352.13
#Mann= 11 ,-1 , 0
       0     .06       0 2358.92     .05       0 8316.41     .06       0
10155.87      .1       011040.61     .05       013090.02      .1       0
14689.55     .05       019297.92      .1       020277.54    .045       0
20492.45      .1       020497.45     .06       0
#XS Ineff= 2 , 0
                           22350             360
Permanent Ineff=
       F       F
Bank Sta=20277.54,20492.45
XS Rating Curve= 0 ,0
Exp/Cntr=0.3,0.1