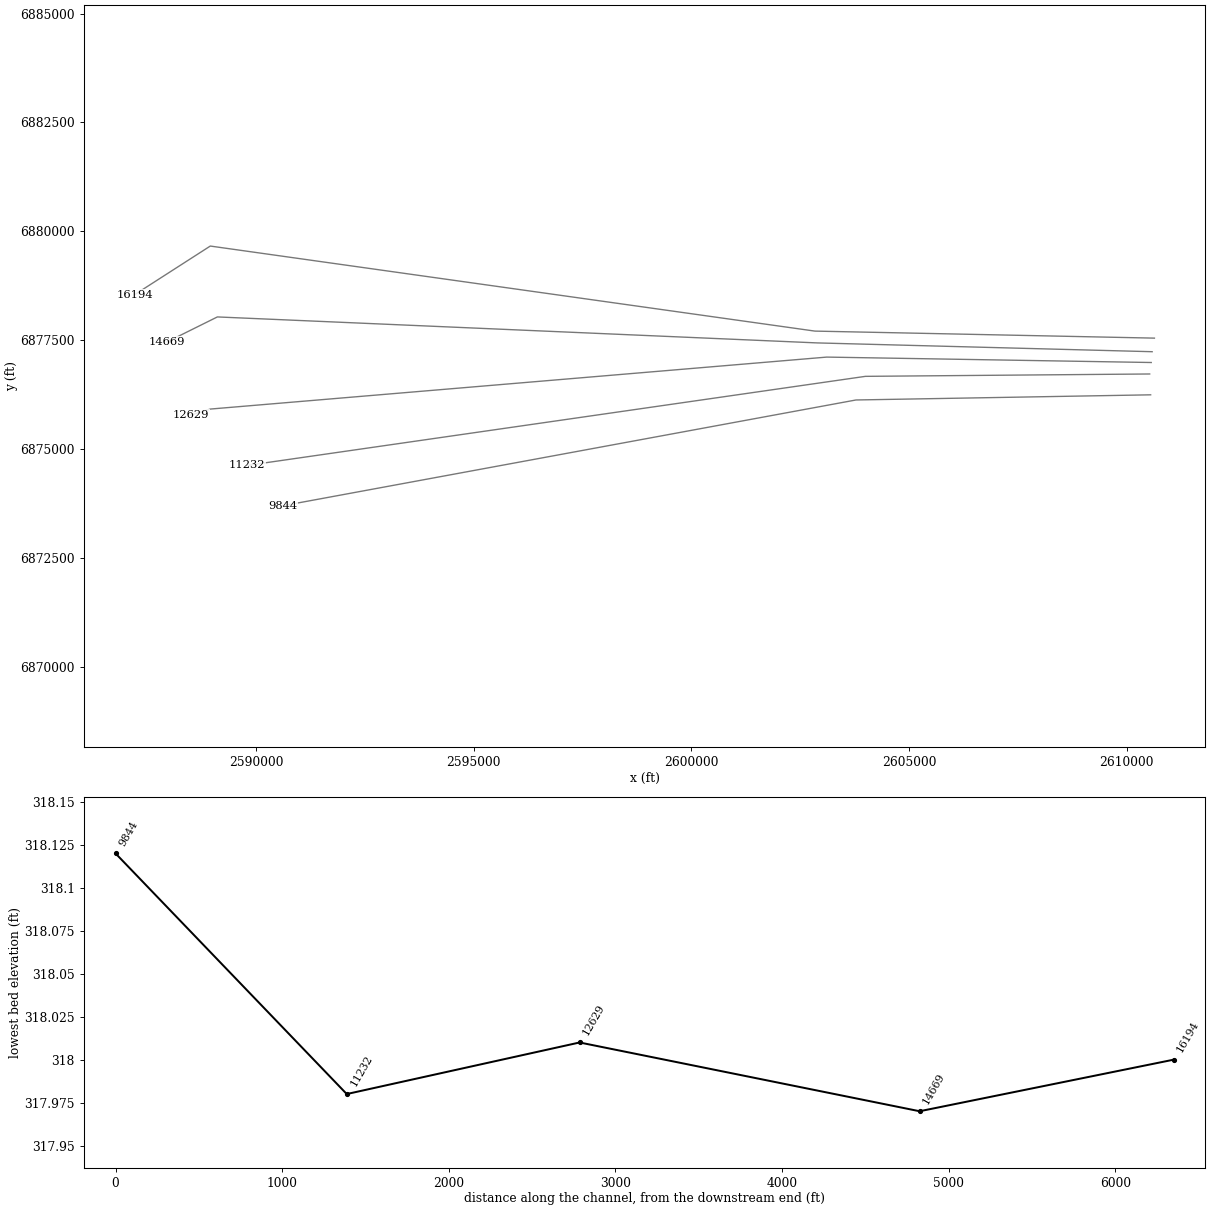
HEC-RAS study EF_FEMA.prj: East_Fork_FEMA

--- EF_FEMA.g01 (geometry) --- (continued)

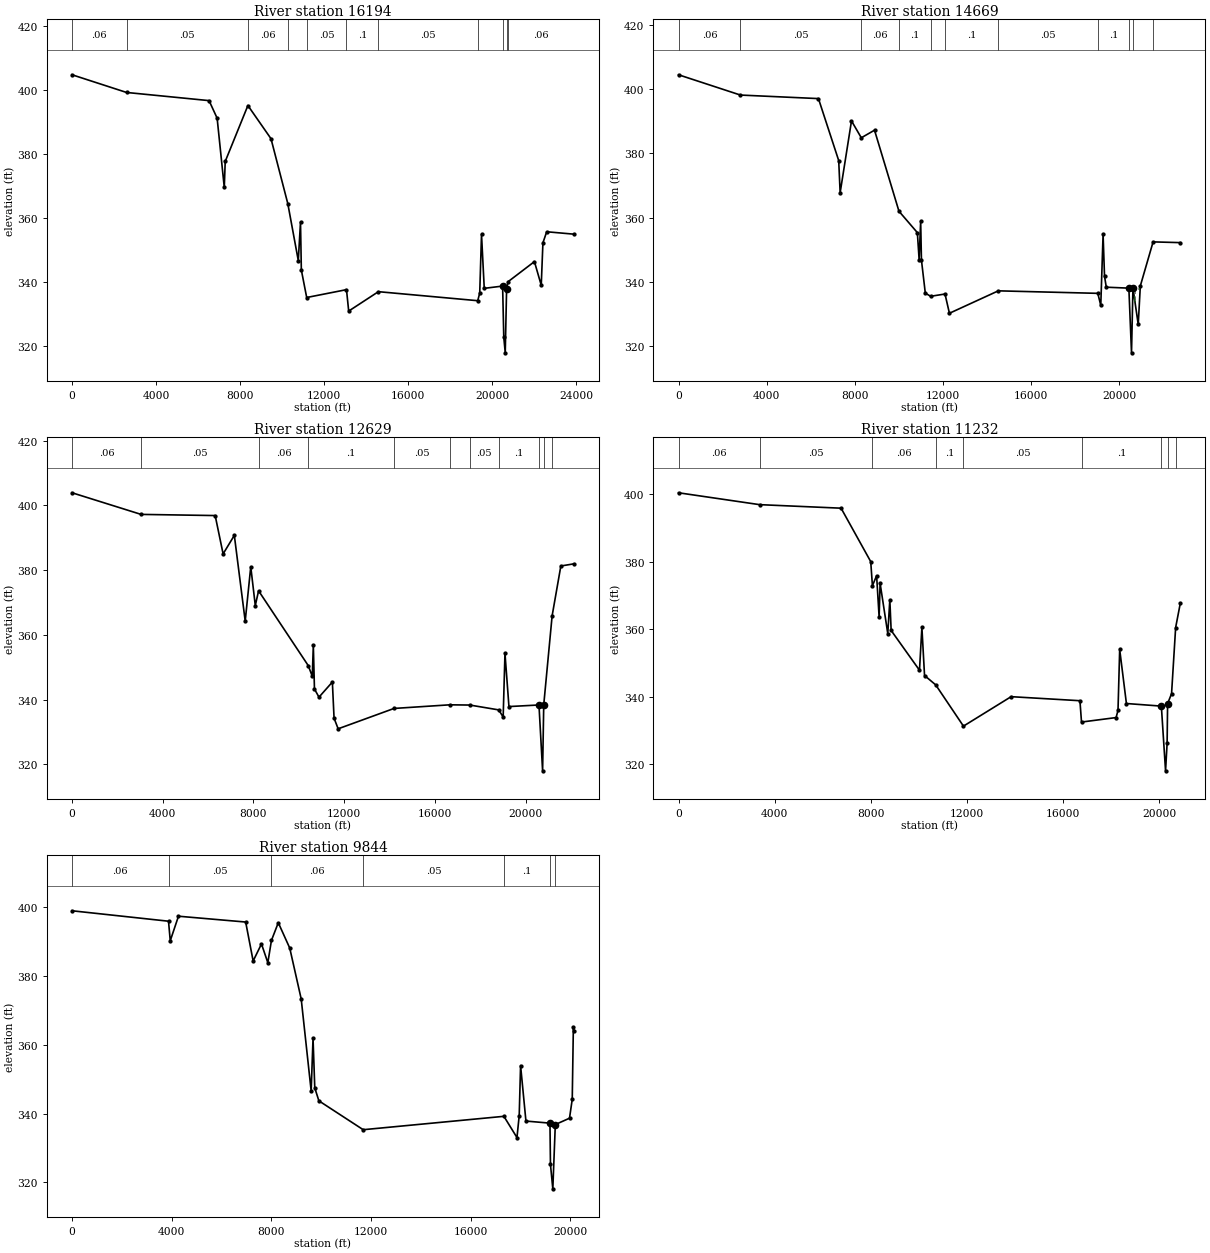
Type RM Length L Ch R = 1 ,16194   ,1459.55,1524.39,1548.01
XS GIS Cut Line= 4
2610636.035986566877546.874502732602837.471859316877708.16650298
2588948.582970476879661.291533722587214.015245396878546.99454972
#Sta/Elev= 30
       0  404.83 2593.41  399.31 6520.94  396.76  6905.7  391.27 7245.48  369.67
 7290.45  377.77 8369.93  395.23  9469.5  384.8710269.19  364.6110768.99  346.81
10873.95  358.8410913.94  343.8711168.84  335.28 13063.1  337.7313168.06  331.04
 14582.5   337.119310.66  334.2819405.62  336.6919490.59  354.9719620.54  338.14
20495.19  338.8520550.17  322.9120620.14     31820685.12  338.0920760.09  340.24
22009.38  346.4922333.88  339.0922413.75  352.3522593.47  355.8123886.45  355.06
#Mann= 11 ,-1 , 0
       0     .06       0 2593.41     .05       0 8369.93     .06       0
10269.19      .1       011168.84     .05       0 13063.1      .1       0
 14582.5     .05       019310.66      .1       020495.19    .045       0
20685.12      .1       020760.09     .06       0
#XS Ineff= 2 , 0
Permanent Ineff=
       F       F
Bank Sta=20495.19,20685.12
XS Rating Curve= 0 ,0
Exp/Cntr=0.3,0.1

Type RM Length L Ch R = 1 ,14669   ,1925.16,2040.36,2071.02
XS GIS Cut Line= 4
2610583.787731476877234.965021572602891.72535972 6877436.8990009
2589111.343471726878033.687505482587959.75128672 6877462.1194229
#Sta/Elev= 30
       0  404.48  2809.9  398.17 6349.68  397.07 7269.61  377.78  7334.6  367.79
 7849.56  390.13  8294.5  384.88 8894.38  387.2410004.17  362.02   10839  355.37
10918.99  346.9810988.97  358.9411023.97  346.8511198.93  336.5711438.88  335.56
12093.76  336.2712293.72  330.2814513.28  337.2619027.92  336.4819162.92  332.74
19267.92  354.8319332.92  341.8319412.92  338.3920437.92   338.120557.92  317.97
20622.92  338.1920862.92  326.8120957.92  338.7921537.74  352.4922773.38  352.26
#Mann= 11 ,-1 , 0
       0     .06       0  2809.9     .05       0  8294.5     .06       0
10004.17      .1       011438.88     .05       012093.76      .1       0
14513.28     .05       019027.92      .1       020437.92    .045       0
20622.92      .1       021537.74     .06       0
#XS Ineff= 1 ,-1
20712.92 20952.5  337.85
Permanent Ineff=
       F
Bank Sta=20437.92,20622.92
XS Rating Curve= 0 ,0
Exp/Cntr=0.3,0.1

Type RM Length L Ch R = 1 ,12629   ,1407.93,1397.2,1386.65
XS GIS Cut Line= 4
2610563.192628316876986.906134472603108.739361396877111.37832648
2588948.582970476875917.801973482588505.007085966875781.77206181
#Sta/Elev= 30
       0  403.93 3043.16  397.25 6311.16  396.89 6660.95  385.04 7155.64  390.77
  7635.4  364.28 7880.32  381.08 8080.26  369.09 8225.21  373.6410414.46  350.54
10594.39  347.2210639.38  356.8210689.36  343.2910889.29  340.7811479.09  345.45
11554.06  334.28   11734     33114198.15  337.2916652.29  338.4117541.94  338.34
18816.45  336.8419011.37  334.6319091.34  354.3219266.27  337.8720590.75  338.36
20750.69  318.0120800.67  338.3921170.53   365.921555.38  381.3122129.24  381.97
#Mann= 11 ,-1 , 0
       0     .06       0 3043.16     .05       0 8225.21     .06       0
10414.46      .1       014198.15     .05       016652.29      .1       0
17541.94     .05       018816.45      .1       020590.75    .045       0
20800.67      .1       021170.53     .06       0
#XS Ineff= 2 , 0
Permanent Ineff=
       F       F
Bank Sta=20590.75,20800.67
XS Rating Curve= 0 ,0
Exp/Cntr=0.3,0.1

Type RM Length L Ch R = 1 ,11232   ,1202.37,1387.45,1271.95
XS GIS Cut Line= 3
2610527.134301476876723.471950052603997.091587316876669.14758365
2589788.177091816874622.49485281
#Sta/Elev= 30
       0  400.46 3372.58  396.94  6765.2  395.89  7999.8  380.04 8069.77  372.89
 8244.72  375.88  8349.7  363.52 8389.68  373.64  8709.6  358.68 8794.58  368.69
 8849.57  359.6210029.26  347.8210129.24  360.5210239.21  346.2610704.09  343.48
11858.79  331.2413843.29  339.9816707.51  338.7816772.48  332.4518211.92  333.78
18291.89  335.8918361.86  353.9918641.75  337.9520096.18  337.1820271.11  317.98
20336.09   326.220356.08  337.9120521.02  340.8620690.95  360.4920885.87  367.72
#Mann= 9 ,-1 , 0
       0     .06       0 3372.58     .05       0 8069.77     .06       0
10704.09      .1       011858.79     .05       016772.48      .1       0
20096.18    .045       020356.08      .1       020690.95     .06       0
#XS Ineff= 2 , 0
Permanent Ineff=
       F       F
Bank Sta=20096.18,20356.08
XS Rating Curve= 0 ,0
Exp/Cntr=0.3,0.1

Type RM Length L Ch R = 1 ,9844    ,10444.61,9844.32,7111.31
XS GIS Cut Line= 3
 2610549.21824686876244.959127562603780.077585646876126.61290756
2590625.797791886873699.69912623
#Sta/Elev= 30
       0  398.91 3872.26  395.88 3942.21   390.2 4271.98  397.33 6970.18  395.64
 7270.09  384.32 7604.99  389.28 7859.92  383.82 8004.87   390.3  8279.8  395.44
 8739.71  388.07 9199.61  373.29 9599.53  346.57 9674.51  361.85  9744.5  347.45
 9909.46  343.6911689.09   335.317337.74  339.1917862.53  333.02 17952.5   339.4
18007.47  353.9418222.39  337.8119187.01  337.2119207.01  325.2319301.97  318.12
19401.93   336.819971.71  338.6420081.66  344.1420126.65  365.1320146.64  364.11
#Mann= 7 ,-1 , 0
       0     .06       0 3872.26     .05       0 8004.87     .06       0
11689.09     .05       017337.74      .1       019187.01    .045       0
19401.93      .1       0
#XS Ineff= 2 , 0
Permanent Ineff=
       F       F
Bank Sta=19187.01,19401.93
XS Rating Curve= 0 ,0
Exp/Cntr=0.3,0.1
Stream Node=East Fork       ,12030106000003  , 0 , 0 ,Upstream end
Stream Node=East Fork       ,12030106000003  , 0 , 1 ,Downstream end
LCMann Table=0

--- EF_FEMA.g02 (geometry) ---

Geom Title=EastFork_NV_Kauf_5_East
Program Version=5.06
BEGIN GEOM DESCRIPTION:
Scenario H
END GEOM DESCRIPTION:

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
River Reach=East Fork       ,1

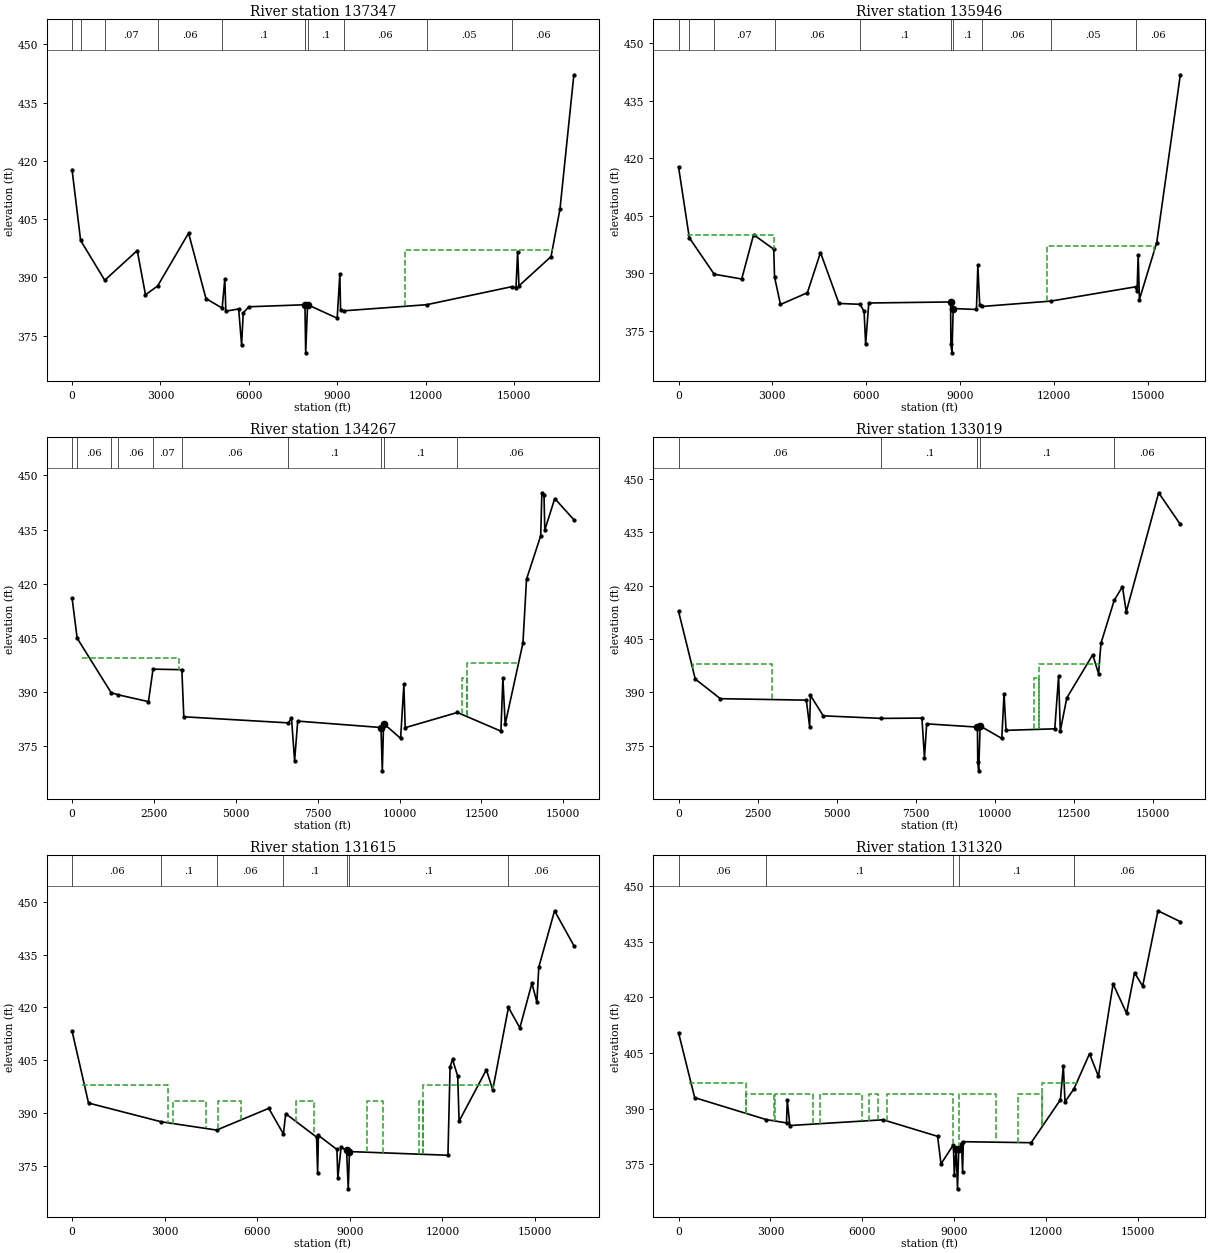
Type RM Length L Ch R = 1 ,137347  ,1140.97,1400.58,978.45
BEGIN DESCRIPTION:
LOB IFA station 3953.68: flow contraction due to natural high ground
END DESCRIPTION:
XS GIS Cut Line= 5
2588787.69779356 6964514.75043542587225.197637726964556.41701873
2585029.793892066965464.120911972573906.166861136968072.27514447
2572454.730787636967259.87585065
#Sta/Elev= 30
       0  417.72  289.64  399.51 1108.62  389.24 2211.87   396.9 2491.35   385.5
  2900.6  387.74 3953.68  401.38 4543.44  384.52 5093.21  382.07 5183.18  389.58
 5218.16  381.28 5652.98  381.84 5752.94  372.55 5807.92  380.84 6002.84  382.41
 7902.06  382.93 7927.05  370.54 7992.02  382.94 8996.63  379.46 9086.59  390.92
 9111.58  381.48 9211.54  381.3612030.44  382.9414919.31  387.5815064.25  387.34
15119.23  396.5615164.22   387.816253.27  395.3416557.95  407.6617027.45  442.18
#Mann= 10 ,-1 , 0
       0     .07       0  289.64     .06       0 1108.62     .07       0
  2900.6     .06       0 5093.21      .1       0 7902.06    .045       0
 7992.02      .1       0 9211.54     .06       012030.44     .05       0
14919.31     .06       0
#XS Ineff= 2 ,-1
     235 3953.68  401.38 11285.9   16316     397
Permanent Ineff=
       F       F
Bank Sta=7902.06,7992.02
XS Rating Curve= 0 ,0
Exp/Cntr=0.3,0.1

Type RM Length L Ch R = 1 ,135946  ,940.19,1679.57,1522.42
BEGIN DESCRIPTION:
LOB IFA station 4539.01: flow contraction due to natural high ground
END DESCRIPTION:
XS GIS Cut Line= 6
2588792.906116476964431.417268722584150.093551736964534.61555314
2580302.000198056965452.483468062580109.291593976965663.42103831
2574802.434097476966908.357196732573353.168295226966005.53551157
#Sta/Elev= 30
       0  417.71  344.92  399.25 1139.74  389.77 2019.54  388.52 2399.46  400.06
 3044.33  396.28 3069.32  389.04 3259.28  381.88  4119.1  384.93 4539.01  395.41
  5128.5  382.15 5797.82  381.93 5932.68  380.11 5982.63  371.58 6082.53  382.27
 8698.51  382.54 8708.36   371.5 8742.84  369.29 8782.25  380.83 9525.19  380.58
 9570.15  392.06 9630.11  381.72 9715.04  381.3711908.33  382.7714611.02  386.48
14660.95  385.3914695.89  394.8314735.83  383.18   15290  398.0216043.86   441.7
#Mann= 10 ,-1 , 0
       0     .07       0  344.92     .06       0 1139.74     .07       0
 3069.32     .06       0 5797.82      .1       0 8698.51    .045       0
 8782.25      .1       0 9715.04     .06       011908.33     .05       0
14611.02     .06       0
#XS Ineff= 3 ,-1
     280 3044.33     400 3044.33 4539.01  395.41 11795.9   15196     397
Permanent Ineff=
       F       F       F
Bank Sta=8698.51,8782.25
XS Rating Curve= 0 ,0
Exp/Cntr=0.3,0.1

Type RM Length L Ch R = 1 ,134267  ,945.86,1247.61,984.8
BEGIN DESCRIPTION:
LOB IFA station 3271.67: flow contraction due to natural high ground
END DESCRIPTION:
XS GIS Cut Line= 6
2588765.04134281 6964353.29209692587657.48942405 6964353.2920969
2585886.656023476963587.667315812579703.193652886964540.00497806
2576021.786645646964703.762524562573752.039544726964430.88282098
#Sta/Elev= 30
       0  416.04  154.66  404.91 1192.52  389.82 1402.44  389.24 2332.08  387.33
 2472.03  396.33 3351.63  396.18 3411.59  383.14 6604.72  381.45 6699.67  382.82
 6794.61  370.95 6889.55  381.94 9432.35  380.17 9472.12  368.17  9511.9  381.27
10031.17  377.1710131.13   392.110171.11  380.1211765.49  384.33 13094.6  379.16
13154.33  393.8813224.02  381.0613766.57  403.5613876.08  421.2414309.42  433.28
14344.31  445.1714409.11  444.6914434.03  434.8614738.08  443.5815321.25  437.71
#Mann= 10 ,-1 , 0
       0     .07       0  154.66     .06       0 1192.52     .07       0
 1402.44     .06       0 2472.03     .07       0 3351.63     .06       0
 6604.72      .1       0 9432.35    .045       0  9511.9      .1       0
11765.49     .06       0
#XS Ineff= 3 ,-1
     296 3271.67   399.5 11907.712051.15     39412051.15   13675     398
Permanent Ineff=
       F       F       F
Bank Sta=9432.35,9511.9
XS Rating Curve= 0 ,0
Exp/Cntr=0.3,0.1

Type RM Length L Ch R = 1 ,133019  ,1384.23,1404.04,669.16
XS GIS Cut Line= 6
2588754.190642716964308.587461892587669.034348476964243.83037356
2585644.468515726962879.449572152577308.228298476963605.97731856
2577133.749316726963332.53987332 2573698.65415286964403.53904365
#Sta/Elev= 30
       0  412.81  528.58  393.76 1321.74  388.24 4037.95  387.83 4142.85  380.42
 4167.82   389.2 4572.66  383.42 6407.22   382.7 7691.92  382.79  7771.9  371.67
 7841.88  381.17 9446.45  380.25 9456.44  370.33 9486.43  367.96 9531.42  380.58
10216.23  377.0610286.21  389.6410351.19  379.3411890.76  379.77 12010.6  394.56
12065.49  379.23 12270.1  388.4513089.62  400.5913274.52  395.2613349.47  403.79
13769.23   415.914029.07  419.72   14149  412.64 15173.4  446.11   15858  437.22
#Mann= 5 ,-1 , 0
       0     .06       0 6407.22      .1       0 9446.45    .045       0
 9531.42      .1       013769.23     .06       0
#XS Ineff= 3 ,-1
     454    2945     398 11247.311390.75     39411390.75   13291     398
Permanent Ineff=
       F       F       F
Bank Sta=9446.45,9531.42
XS Rating Curve= 0 ,0
Exp/Cntr=0.3,0.1

Type RM Length L Ch R = 1 ,131615  ,369.03,295,387.25
XS GIS Cut Line= 6
 2588747.15948886964284.194794152587668.760726976964143.37617815
2584852.372658976962150.103589892582383.203056636961929.92128748
2577347.612734146963234.825829892573662.195892396964391.82023506
#Sta/Elev= 30
       0  413.26  533.43   392.8 2888.33  387.47 4683.03  385.11 6372.96   391.3
  6846.4     384 6921.16  389.77 7920.21  383.12 7955.18   372.8 7980.17   383.6
  8579.8   379.6 8609.78  371.55 8714.72   380.2 8893.24  379.32 8947.46   368.4
 8986.89     37912176.84  377.9512245.58  403.1412324.14  405.2112492.83  400.45
 12537.8  387.6513422.28  402.2713627.16  396.5214136.86  419.9914506.64  414.18
14896.42  426.8615056.32  421.5615121.28  431.5215630.99  447.4816255.62  437.57
#Mann= 7 ,-1 , 0
       0     .06       0 2888.33      .1       0 4683.03     .06       0
  6846.4      .1       0 8893.24    .045       0 8986.89      .1       0
14136.86     .06       0
#XS Ineff= 7 ,-1
     306  3102.4     398  3278.5  4337.6   393.5  4728.8    5473   393.5
  7256.4  7839.6   393.5  9555.7 10058.1   393.5   1123111374.45   393.5
11374.45   13635     398
Permanent Ineff=
       F       F       F       F       F       F       F
Bank Sta=8893.24,8986.89
XS Rating Curve= 0 ,0
Exp/Cntr=0.5,0.3

Type RM Length L Ch R = 1 ,131320  ,172.92,142.52,224.66
BEGIN DESCRIPTION:
US Bridge
END DESCRIPTION:
XS GIS Cut Line= 6
2588737.414429566964257.794584482587680.556963226964114.56554022
2584666.667977886961956.290001142583241.320762986961464.97044572
2582687.501332556961497.956600232573617.924983556964386.61191215
#Sta/Elev= 30
       0  410.48  526.75  392.94 2864.51  387.01 3524.75  386.12 3549.73  392.26
 3634.65  385.41 6678.04  386.96 8457.71  382.49 8567.68  375.03 8972.61   380.2
  9002.6  372.04 9062.59  379.12 9107.58  368.31 9148.43  379.19 9237.55  380.64
 9272.55   372.9 9297.54  381.0411512.11  380.7712466.92  392.36 12561.9  401.53
12616.89  391.7912911.93  395.3713416.74  404.7913706.68  398.7314186.59  423.64
 14626.5  415.7314886.45  426.68 15151.4  423.05 15651.3  443.4116381.16  440.47
#Mann= 5 ,-1 , 0
       0     .06       0 2864.51      .1       0 8972.61    .045       0
 9148.43      .1       012911.93     .06       0
#XS Ineff= 9 ,-1
     350    2215     397    2215    3121     394    3163    4396     394
    4630    6005     394 6209.61    6503     394 6792.79    8960     394
    9165   10375     394   11085   11880     394   11880   13035     397
Permanent Ineff=
       F       F       F       F       F       F       F       F       F
Bank Sta=9062.59,9148.43
XS Rating Curve= 0 ,0
Exp/Cntr=0.5,0.3

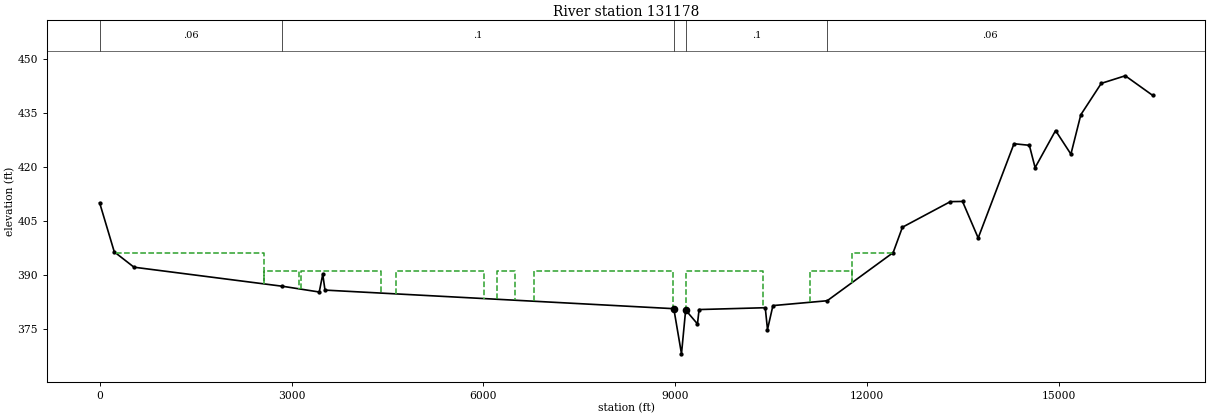
Type RM Length L Ch R = 1 ,131178  ,422.59,655.81,1080.74
BEGIN DESCRIPTION:
DS Bridge
END DESCRIPTION:
XS GIS Cut Line= 6
2588751.538417066964138.107815982587631.747021476963951.91002564
2584272.805904726961633.116434892583239.819781726961368.35974656
2582661.477762556961371.614661312573552.820783056964356.23008314
#Sta/Elev= 30
       0  410.02  228.84  396.38  537.27  392.11 2858.58  386.81 3433.69  385.21
  3488.6  390.14 3523.55  385.74 8977.57  380.57 9097.55  368.01 9162.53  380.19
  9347.5  376.33 9372.49  380.3310407.29  380.8410442.28  374.7810527.27  381.43
11375.92  382.78 12406.9  396.1712551.87  403.2313301.73  410.3513491.69   410.4
13736.64  400.2414296.53  426.4614536.48  426.0214626.47  419.81 14946.4  430.12
15186.36  423.5615341.33  434.5215661.26  443.2516036.19  445.3616466.12  439.89
#Mann= 5 ,-1 , 0
       0     .06       0 2858.58      .1       0 8977.57    .045       0
 9162.53      .1       011375.92     .06       0
#XS Ineff= 9 ,-1
     250    2570     396    2570    3120     391    3156    4397     391
    4630    6005     391 6205.54    6500     391    6790    8970     391
    9170   10375     391   11100   11760     391   11760   12400     396
Permanent Ineff=
       F       F       F       F       F       F       F       F       F
Bank Sta=8977.57,9162.53
XS Rating Curve= 0 ,0
Exp/Cntr=0.5,0.3