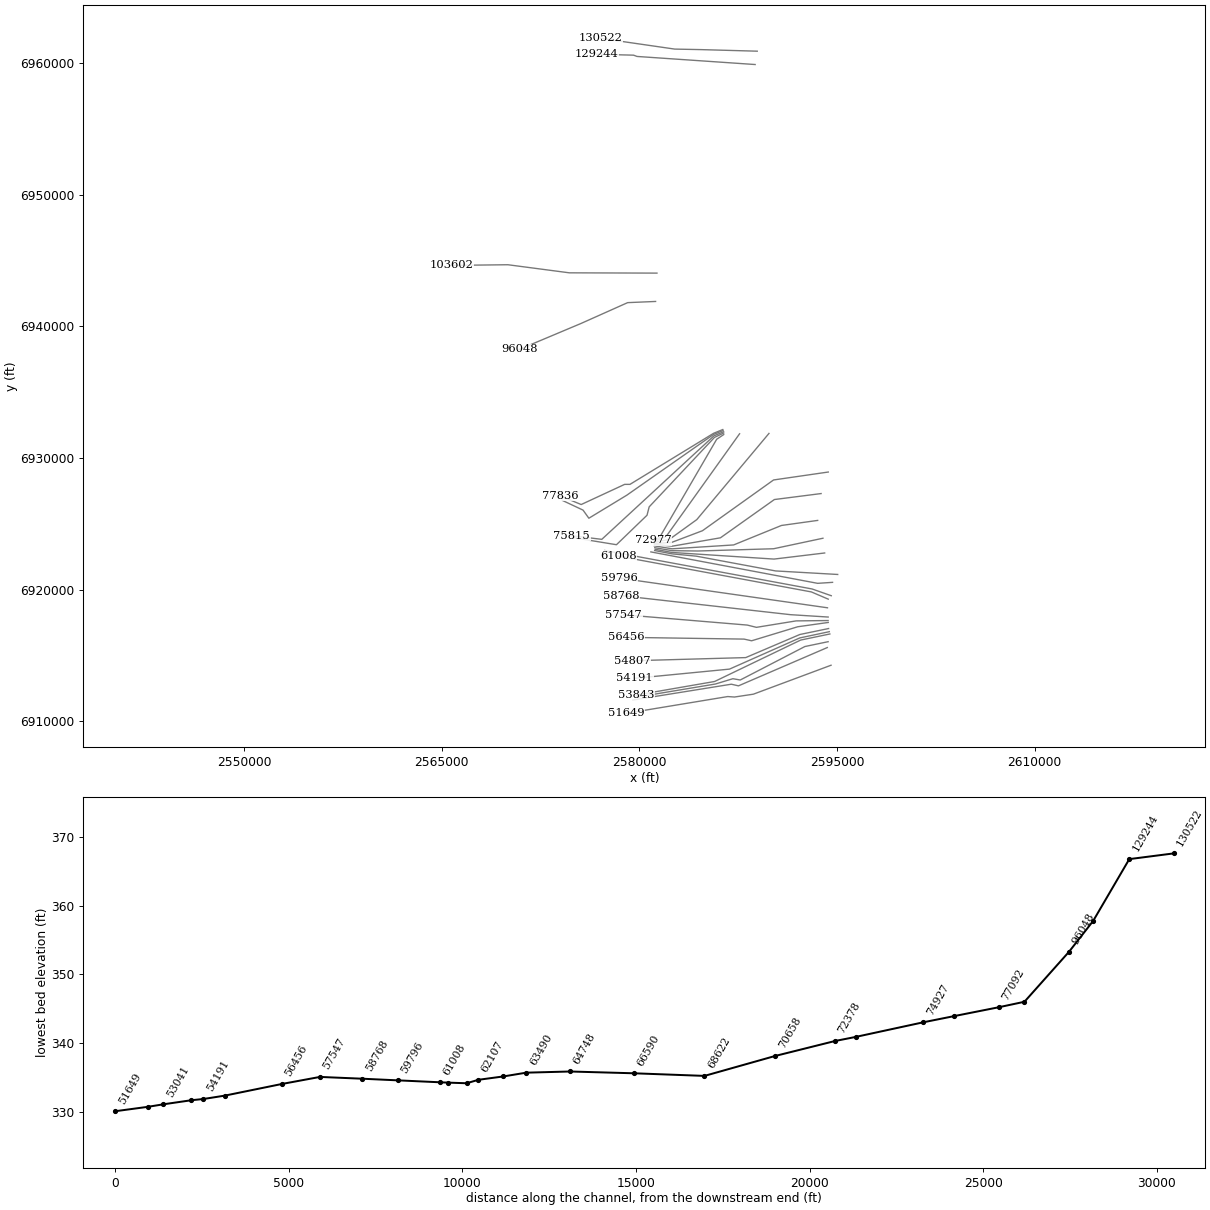
HEC-RAS study EF_FEMA.prj: East_Fork_FEMA

--- EF_FEMA.g02 (geometry) --- (continued)

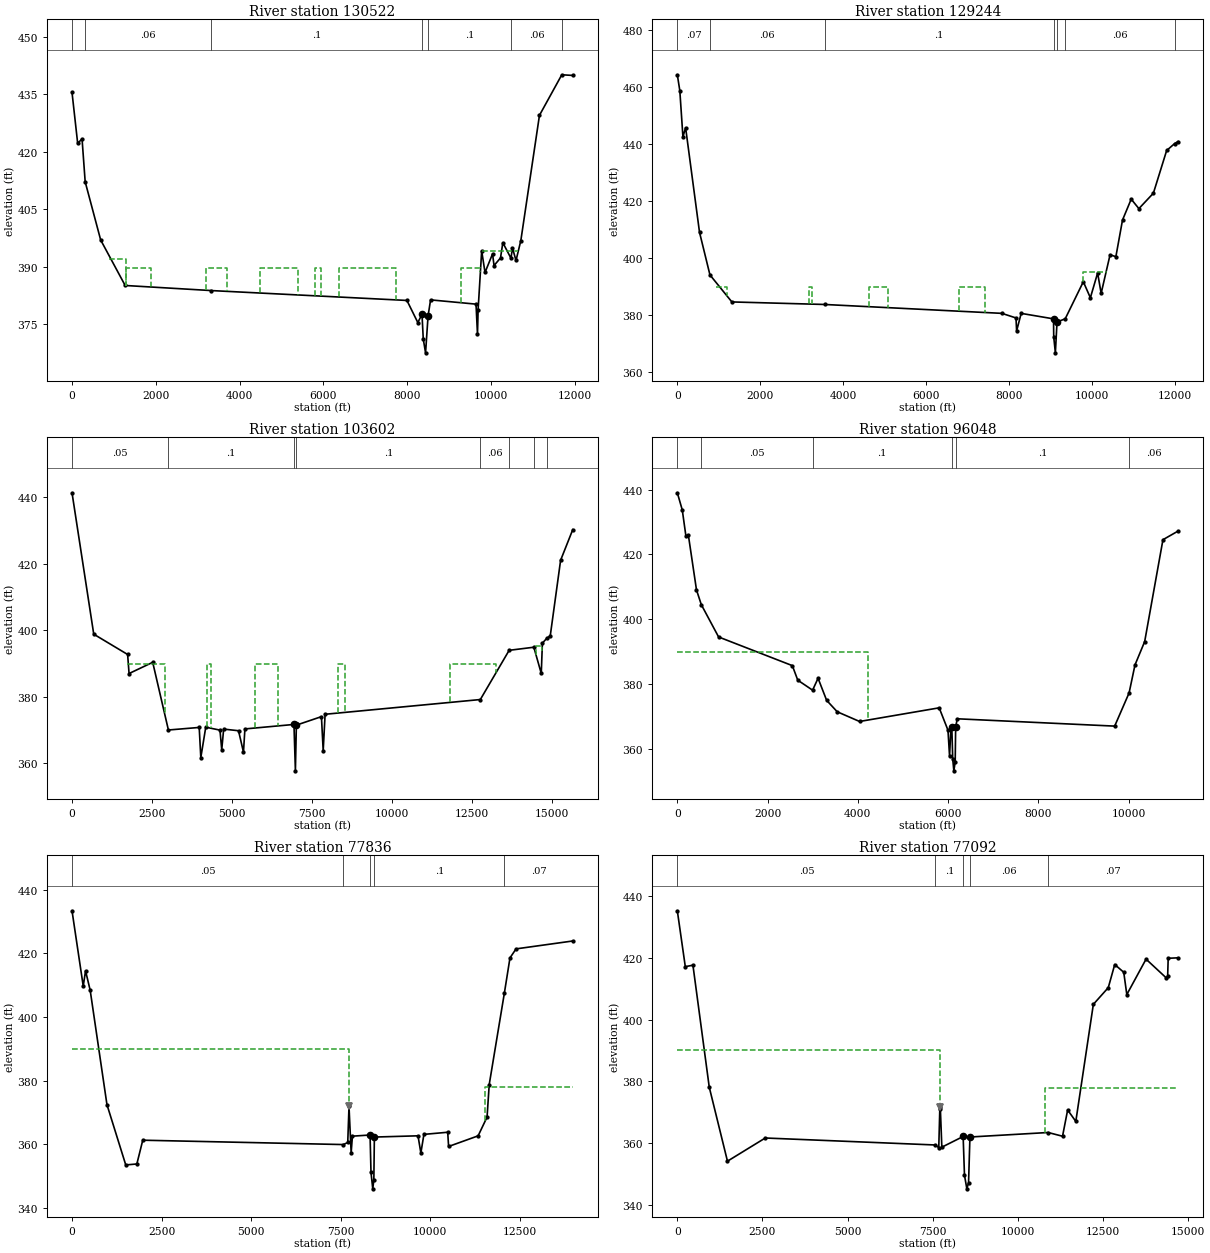
Type RM Length L Ch R = 1 ,130522  ,825.93,1278.14,964.51
XS GIS Cut Line= 4
2588948.37726222 6960912.01551492584693.881178056961031.34434448
2582688.672918146961070.406602312577053.341669146961888.04440273
#Sta/Elev= 30
       0  435.45  134.88  422.19  239.78  423.32  314.15  412.16  684.38  396.99
 1268.86  385.14 3316.13  383.82  7996.6  381.24 8256.57  375.48 8356.56  377.63
 8386.56  371.21 8441.55  367.59 8501.54  377.22 8561.53  381.39  9646.4  380.28
 9681.39  372.43 9696.39  378.83 9781.38  394.15 9861.37  388.5310041.35  393.38
10076.34  390.3310231.32  392.3210286.32  396.2910480.97  392.2410516.29  394.91
10601.28  391.6510716.26  396.8311161.21  429.4811694.34  440.0411956.11  439.87
#Mann= 7 ,-1 , 0
       0     .07       0  314.15     .06       0 3316.13      .1       0
 8356.56    .045       0 8501.54      .1       010480.97     .06       0
11694.34     .05       0
#XS Ineff= 8 ,-1
     890    1300     392    1300    1887  389.75    3199    3704  389.75
 4487.91  5401.7  389.75 5803.14 5954.81  389.75 6370.56 7740.43  389.75
 9288.19    9751  389.75 9781.38   10656  394.15
Permanent Ineff=
       F       F       F       F       F       F       F       F
Bank Sta=8356.56,8501.54
XS Rating Curve= 0 ,0
Exp/Cntr=0.3,0.1

Type RM Length L Ch R = 1 ,129244  ,922.95,1040.29,819.79
XS GIS Cut Line= 4
2588788.655140716959898.126794652579823.828582216960512.30896522
2579563.252331726960609.753324152576761.67492963 6960679.7108614
#Sta/Elev= 30
       0  464.15   59.97   458.6  134.94  442.42  199.91  445.61  534.75  408.98
  786.12  394.05 1314.39  384.59  3547.4   383.7  7821.4  380.59 8161.24  378.98
 8176.23  374.44 8286.19  380.58  9065.4  378.66 9070.37  372.34 9110.11  366.76
 9149.85  377.56 9347.56  378.69 9783.65  391.66  9953.5  386.0510128.34  394.73
10213.27   387.610428.07  401.1110567.95  400.4410727.81  413.2710937.62  420.59
11122.45  417.2711472.14  422.6811791.86  437.64 11985.7  440.0712066.61  440.76
#Mann= 7 ,-1 , 0
       0     .07       0  786.12     .06       0  3547.4      .1       0
  9065.4    .045       0 9149.85      .1       0 9347.56     .06       0
 11985.7     .05       0
#XS Ineff= 5 ,-1
     920    1198  389.75    3164    3250  389.75 4620.21 5073.91  389.75
 6790.06 7416.27  389.75 9783.65   10358     395
Permanent Ineff=
       F       F       F       F       F
Bank Sta=9065.4,9149.85
XS Rating Curve= 0 ,0
Exp/Cntr=0.3,0.1

Type RM Length L Ch R = 1 ,103602  ,491.43,697.56,687.23
XS GIS Cut Line= 4
2581338.134280646944053.508549562574691.724345136944075.03114431
2570026.547323816944689.645072562565718.344654146944640.17830798
#Sta/Elev= 30
       0  441.38  679.64  398.86 1739.07  392.76 1784.05  387.03 2523.65   390.4
 3014.39  370.05 3977.86  370.82 4027.83  361.74 4182.75   370.9 4627.52  370.01
 4682.49  364.11 4742.46  370.32 5207.23  369.83 5362.15  363.39 5407.13  370.37
 6941.21  371.72 6986.16  357.77 7016.13  371.51 7800.37  374.07 7855.31  363.88
 7915.26  374.7812769.61  379.2113671.06  394.01 14443.2  394.94 14675.6  387.04
14710.58  396.17 14855.6   397.714955.49   398.315280.36  421.0915660.21   430.3
#Mann= 8 ,-1 , 0
       0     .05       0 3014.39      .1       0 6941.21    .045       0
 7016.13      .1       012769.61     .06       013671.06     .07       0
 14443.2      .1       0 14855.6     .06       0
#XS Ineff= 6 ,-1
    1730    2900     390 4213.59  4331.1     390 5717.27 6426.55     390
 8328.54 8538.55     39011818.01   13255     390   14511   14702   395.2
Permanent Ineff=
       F       F       F       F       F       F
Bank Sta=6941.21,7016.13
XS Rating Curve= 0 ,0
Exp/Cntr=0.5,0.3

Type RM Length L Ch R = 1 ,96048   ,1090.05,1281.61,847.13
BEGIN DESCRIPTION:
LOB IFA station 4227: flow contraction due to natural high ground downstream
END DESCRIPTION:
XS GIS Cut Line= 4
2581233.967494226941900.731030972579112.051134396941810.50188072
 2575562.78231436940223.360698062570878.066946226938251.28951098
#Sta/Elev= 30
       0  439.01  109.94   433.7   189.9  425.69  244.87  425.94  424.77  409.05
   531.7   404.5   914.5  394.55 2548.61  385.71 2668.55  381.23 2997.16  378.14
 3118.31  381.82 3308.21  375.01 3543.09  371.48 4037.82  368.49 5801.96   372.7
 5996.86   365.8 6031.85  357.79 6061.83  366.49 6081.83  366.73 6101.82  356.97
 6126.81  353.27 6156.79  356.02 6166.79  366.72 6201.77  369.32 9690.34  367.06
10009.93   377.310140.16  385.9210355.08  393.1310759.92  424.5411094.79   427.2
#Mann= 6 ,-1 , 0
       0     .07       0   531.7     .05       0 2997.16      .1       0
 6081.83    .045       0 6166.79      .1       010009.93     .06       0
#XS Ineff= 2 , 0
       0    4227     390               0
Permanent Ineff=
       F       F
Bank Sta=6081.83,6166.79
XS Rating Curve= 0 ,0
Exp/Cntr=0.3,0.1

Type RM Length L Ch R = 1 ,77836   ,308.65,744.14,1041.53
BEGIN DESCRIPTION:
LOB - Kaufman LID15
ROB IFA station 11533: flow contraction due to natural high ground downstream
END DESCRIPTION:
XS GIS Cut Line= 6
2586329.106582146932169.480808482585634.53480855 6931884.9669418
2579288.946777976928005.586577222578886.169040226928005.58657722
2575587.846568636926473.917724562573967.606698896927143.31763248
#Sta/Elev= 30
       0  433.37  313.16  409.69  377.78   414.5  507.02  408.41  975.51  372.46
 1500.33  353.52 1810.23  353.82 1975.17  361.29 7574.07  359.92 7698.24  360.57
 7733.23  371.94 7793.21  357.31  7828.2  362.56 8321.11  362.92 8347.21   351.2
 8396.93  346.01 8426.77  348.88 8441.69  362.28 9659.82  362.67 9739.74  357.27
 9824.66  363.1210489.01  363.7910513.99  359.3211338.18  362.6611587.94  368.56
11647.88  378.7712069.63  407.4112227.31  418.5612397.11   421.413980.25  423.88
#Mann= 5 ,-1 , 0
       0     .05       0 7574.07      .1       0 8321.11    .045       0
 8441.69      .1       012069.63     .07       0
Levee=-1,7733.23,371.94,0,,,,
#XS Ineff= 2 , 0
       0 7733.23     390   11533       0     378
Permanent Ineff=
       F       F
Bank Sta=8321.11,8441.69
XS Rating Curve= 0 ,0
Exp/Cntr=0.3,0.1

Type RM Length L Ch R = 1 ,77092   ,943.98,1276.8,1378.67
BEGIN DESCRIPTION:
LOB - Kaufman LID15
ROB IFA station 10783.6: flow contraction due to natural high ground downstream
END DESCRIPTION:
XS GIS Cut Line= 6
2586356.884085646932096.56428765 2585642.12042336931804.04846847
2579052.835701636927186.142349972576169.750588556925433.65865023
2575728.610722816926049.683008732574162.919300396926785.24485782
#Sta/Elev= 30
       0  435.19  234.18  417.11   458.4  417.58  937.29  378.12 1472.24  354.16
 2582.12  361.66 7580.45   359.4 7676.66  358.53 7706.66  370.91 7721.65  371.63
 7766.65  358.69 8392.23  362.15 8431.57  349.61 8501.55  345.21 8551.53  347.26
 8591.52  361.9810888.78  363.4411310.65  362.23 11460.6  370.7311700.52  367.03
12215.35  404.9112653.98  410.3212843.39   417.813107.97  415.2913197.97  408.08
13762.92  419.5414362.87   413.414397.87  414.1914412.87  419.8214702.85  419.97
#Mann= 5 ,-1 , 0
       0     .05       0 7580.45      .1       0 8392.23    .045       0
 8591.52     .06       010888.78     .07       0
Levee=-1,7721.65,371.63,0,,,,
#XS Ineff= 2 , 0
       0 7721.65     390 10783.6       0     378
Permanent Ineff=
       F       F
Bank Sta=8392.23,8591.52
XS Rating Curve= 0 ,0
Exp/Cntr=0.3,0.1

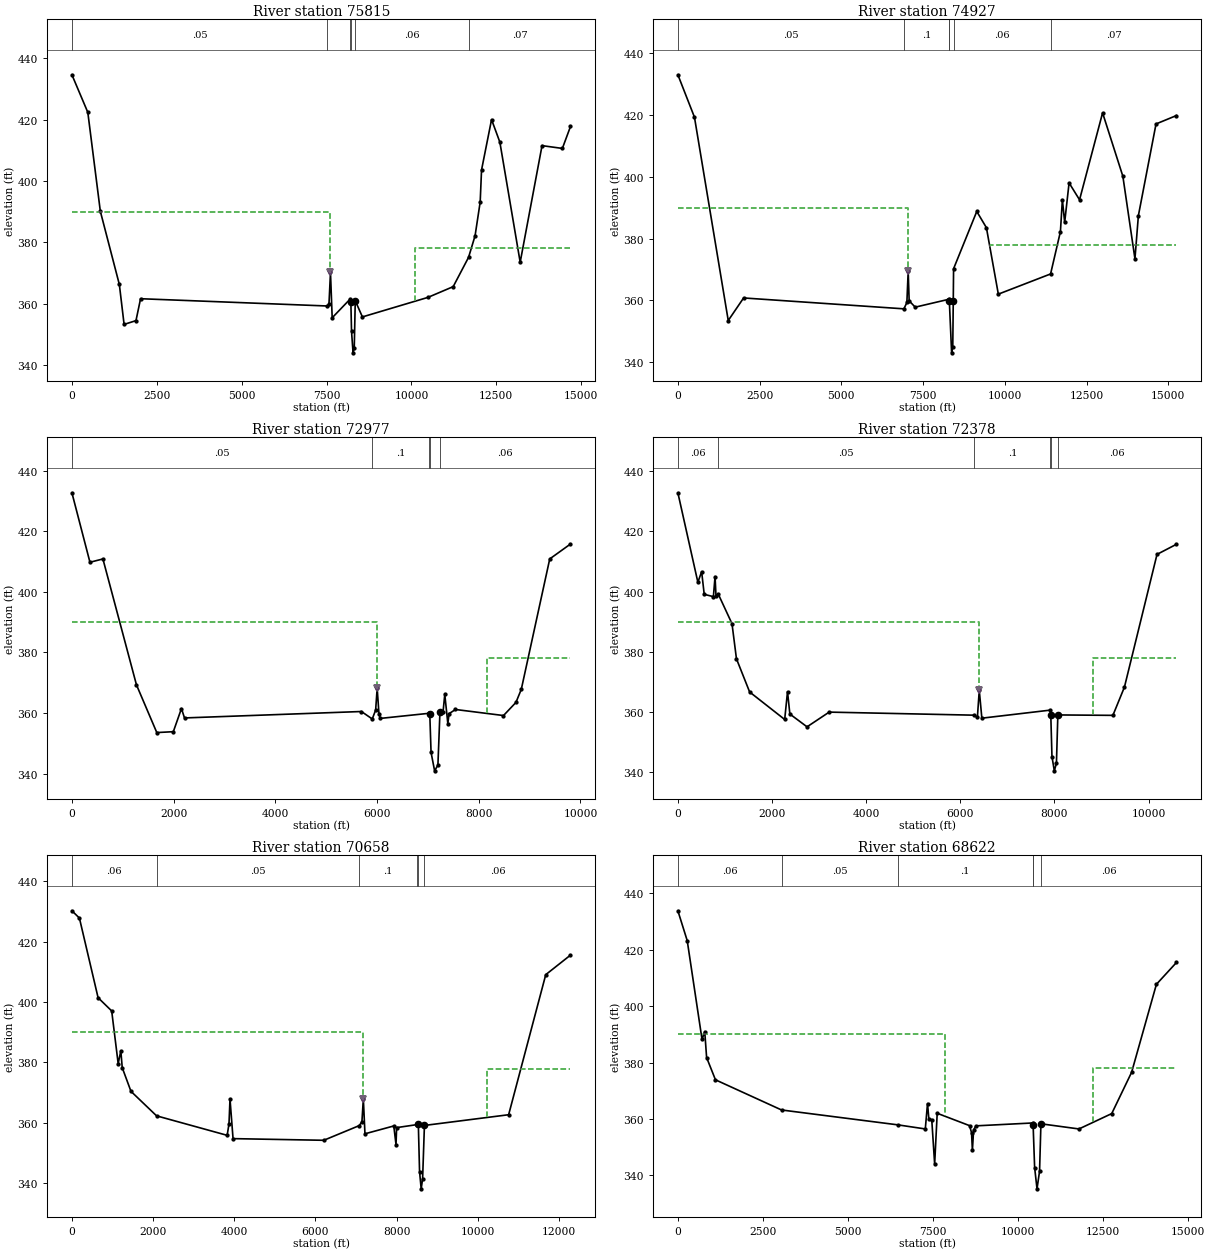
Type RM Length L Ch R = 1 ,75815   ,500.58,888.74,1416.72
BEGIN DESCRIPTION:
LOB - Kaufman LID15
ROB IFA station 10102.8: flow contraction due to natural high ground downstream
END DESCRIPTION:
XS GIS Cut Line= 4
2586398.550997056932002.814147062585663.920248466931693.04376923
 2577151.74764036923830.090991232574868.214477726924105.12324956
#Sta/Elev= 30
       0  434.66   468.4   422.4  837.26  390.12 1397.17  366.24 1537.15  353.21
 1887.09  354.44 2022.07  361.59 7513.93  359.22 7571.07  359.76 7616.06  370.16
 7666.05  355.37 8204.61  361.59 8215.96  360.56 8235.95  350.92 8280.94  343.93
 8315.94  345.52 8345.93  360.93 8555.89  355.6510485.51  362.0211230.37  365.53
11683.22   375.111875.24  382.1612025.21  393.15 12065.2   403.612360.15  420.04
12604.67  412.6813203.38   373.513846.99  411.54 14445.7  410.6314685.19  417.79
#Mann= 6 ,-1 , 0
       0     .05       0 7513.93      .1       0 8204.61     .06       0
 8215.96    .045       0 8345.93     .06       011683.22     .07       0
Levee=-1,7616.06,370.16,0,,,,
#XS Ineff= 2 , 0
       0 7616.06     390 10102.8       0     378
Permanent Ineff=
       F       F
Bank Sta=8215.96,8345.93
XS Rating Curve= 0 ,0
Exp/Cntr=0.3,0.1

Type RM Length L Ch R = 1 ,74927   ,1396.59,1949.18,1764.62
BEGIN DESCRIPTION:
LOB - Kaufman LID15
ROB IFA station 9544: flow contraction due to natural high ground
END DESCRIPTION:
XS GIS Cut Line= 6
2586402.023102976931905.591900562585701.455606486931572.75004657
2580747.280147396926297.253379732580582.989137386925660.03910297
 2578264.4816353 6923421.52947242574955.020078396923964.06414847
#Sta/Elev= 30
       0  432.95  507.13  419.24  1540.3  353.48 2010.11  360.78 6912.73  357.26
 7003.05  359.31 7043.04  369.48 7073.02  359.85 7257.95   357.8 8294.15  360.37
 8301.79   359.7 8371.59  343.03 8406.49  345.02 8421.44  359.65 8431.41  370.24
 9140.39  388.75 9435.19  383.51 9799.93  362.0111397.72  368.5411698.64  382.23
 11758.6  392.5611828.55  385.2111963.48  397.9912283.36  392.5212988.08  420.63
13607.84  400.1513977.69  373.4414082.65  387.3914622.44  417.05 15247.2  419.77
#Mann= 6 ,-1 , 0
       0     .05       0 6912.73      .1       0 8294.15     .06       0
 8301.79    .045       0 8431.41     .06       011397.72     .07       0
Levee=-1,7043.04,369.48,0,,,,
#XS Ineff= 2 , 0
       0 7043.04     390    9544       0     378
Permanent Ineff=
       F       F
Bank Sta=8301.79,8421.44
XS Rating Curve= 0 ,0
Exp/Cntr=0.3,0.1

Type RM Length L Ch R = 1 ,72977   ,812.59,599.81,512.27
BEGIN DESCRIPTION:
LOB - Kaufman LID15
ROB IFA station 8157: flow expansion due to natural high ground upstream
END DESCRIPTION:
XS GIS Cut Line= 4
2586402.023102976931787.536362392585870.115374136931432.29625922
2581529.340919236923958.793161652581049.317272986923751.96614748
#Sta/Elev= 30
       0  432.67  354.79  409.74  609.64  410.83 1269.46  369.28 1669.35  353.53
 1994.26  353.82 2154.21  361.46  2214.2  358.36 5693.21  360.48  5906.6  358.02
 5973.14  360.96 6003.13  368.16 6038.12  359.81 6063.11   358.2 7023.05  359.89
 7037.98  359.62 7062.84  346.99 7132.82   340.9  7197.8   342.8 7237.79  360.36
 7297.77  360.17 7332.76  366.14 7392.75   356.5 7417.74  359.78 7542.71  361.15
 8487.46  359.15 8732.41  363.49 8837.38  367.79 9396.78  410.84 9804.96  415.76
#Mann= 5 ,-1 , 0
       0     .05       0  5906.6      .1       0 7023.05     .06       0
 7037.98    .045       0 7237.79     .06       0
Levee=-1,6003.13,368.16,0,,,,
#XS Ineff= 2 , 0
       0 6003.13     390    8157       0     378
Permanent Ineff=
       F       F
Bank Sta=7037.98,7237.79
XS Rating Curve= 0 ,0
Exp/Cntr=0.3,0.1

Type RM Length L Ch R = 1 ,72378   ,1353.88,1719.75,835.38
BEGIN DESCRIPTION:
LOB - Kaufman LID15
ROB IFA station 8827: flow expansion due to natural high ground upstream
END DESCRIPTION:
XS GIS Cut Line= 3
2587608.57679223 6931849.90631642582029.768724146924041.25625131
2581101.400502136923682.52140448
#Sta/Elev= 30
       0  432.87  424.86  403.08  504.83   406.6  559.81  399.06  754.75  398.29
  789.73  404.99  809.73  398.64  861.56  399.02 1149.61   389.3 1244.58   377.6
 1524.49  366.55 2269.24   357.4 2329.22  366.66  2379.2  359.21 2744.08  354.95
 3213.93  359.85 6295.71  358.83 6362.87  358.06 6402.85  367.13 6457.84  357.83
 7914.71  360.52 7922.34  358.84 7947.33  345.05 7997.32   340.3  8042.3  342.84
 8072.29  358.91 9241.86  358.77 9486.77  368.1710178.99  412.3610592.04  415.73
#Mann= 6 ,-1 , 0
       0     .06       0  861.56     .05       0 6295.71      .1       0
 7914.71     .06       0 7922.34    .045       0 8072.29     .06       0
Levee=-1,6402.85,367.13,0,,,,
#XS Ineff= 2 , 0
       0 6402.85     390    8827       0     378
Permanent Ineff=
       F       F
Bank Sta=7922.34,8072.29
XS Rating Curve= 0 ,0
Exp/Cntr=0.3,0.1

Type RM Length L Ch R = 1 ,70658   ,1805.09,2036.2,1079.67
BEGIN DESCRIPTION:
LOB - Kaufman LID15
ROB IFA station 10237: flow expansion due to natural high ground upstream
END DESCRIPTION:
XS GIS Cut Line= 4
2589837.743593726931875.947930982584361.332302476925329.66345139
2582274.02545346 6923822.32394642581118.761687896923613.07698956
#Sta/Elev= 30
       0  430.28     185  427.86  644.99  401.47  979.99  397.09 1139.99  379.62
 1204.99  383.88 1239.99  378.28 1454.99  370.44 2085.93  362.32 3824.95  355.86
 3869.95  359.66 3894.95  367.91 3969.95  354.77 6204.95  354.22 7078.08  359.08
 7144.95  360.34 7179.95  367.97 7219.95  356.37 7929.95  358.97 7984.95   352.8
 7999.95  358.42 8500.74  359.41 8534.86   359.5 8564.94  343.81 8604.93  338.13
 8639.93  341.39 8684.92  359.1410759.55  362.6911674.04  409.1112283.57  415.59
#Mann= 6 ,-1 , 0
       0     .06       0 2085.93     .05       0 7078.08      .1       0
 8500.74     .06       0 8534.86    .045       0 8684.92     .06       0
Levee=-1,7179.95,367.97,0,,,,
#XS Ineff= 2 , 0
       0 7179.95     390   10237       0     378
Permanent Ineff=
       F       F
Bank Sta=8534.86,8684.92
XS Rating Curve= 0 ,0
Exp/Cntr=0.3,0.1

Type RM Length L Ch R = 1 ,68622   ,1568.87,2031.43,1299.5
BEGIN DESCRIPTION:
LOB IFA station 7840: flow expansion due to Kaufman LID15 levee upstream
ROB IFA station 12204: flow expansion due to natural high ground upstream
END DESCRIPTION:
XS GIS Cut Line= 5
2594338.177506226928943.005306072590187.13757996 6928340.6866288
 2584791.22251886924484.626755642582458.030006726923599.30569164
2581127.442116726923508.91053122
#Sta/Elev= 30
       0  433.85  274.97  423.25  709.92  388.23  789.91     391   844.9  381.79
 1104.87   373.9 3047.63   363.2 6467.94  357.92 7273.27  356.47 7338.25  365.48
 7378.23  359.99  7463.2  359.71 7548.17  344.04 7623.14  362.03 8572.76  357.65
 8632.74  355.17 8657.73  348.83 8692.71  356.08 8762.69  357.5710429.59  358.59
10442.03  358.0410487.01  342.7910556.99  335.2310631.96  341.4910671.94   358.3
11790.18  356.4712753.49  361.9213337.47  376.5514066.76  407.7714656.18  415.51
#Mann= 6 ,-1 , 0
       0     .06       0 3047.63     .05       0 6467.94      .1       0
10429.59     .06       010442.03    .045       010671.94     .06       0
#XS Ineff= 2 , 0
       0    7840     390   12204       0     378
Permanent Ineff=
       F       F
Bank Sta=10442.03,10671.94
XS Rating Curve= 0 ,0
Exp/Cntr=0.3,0.1

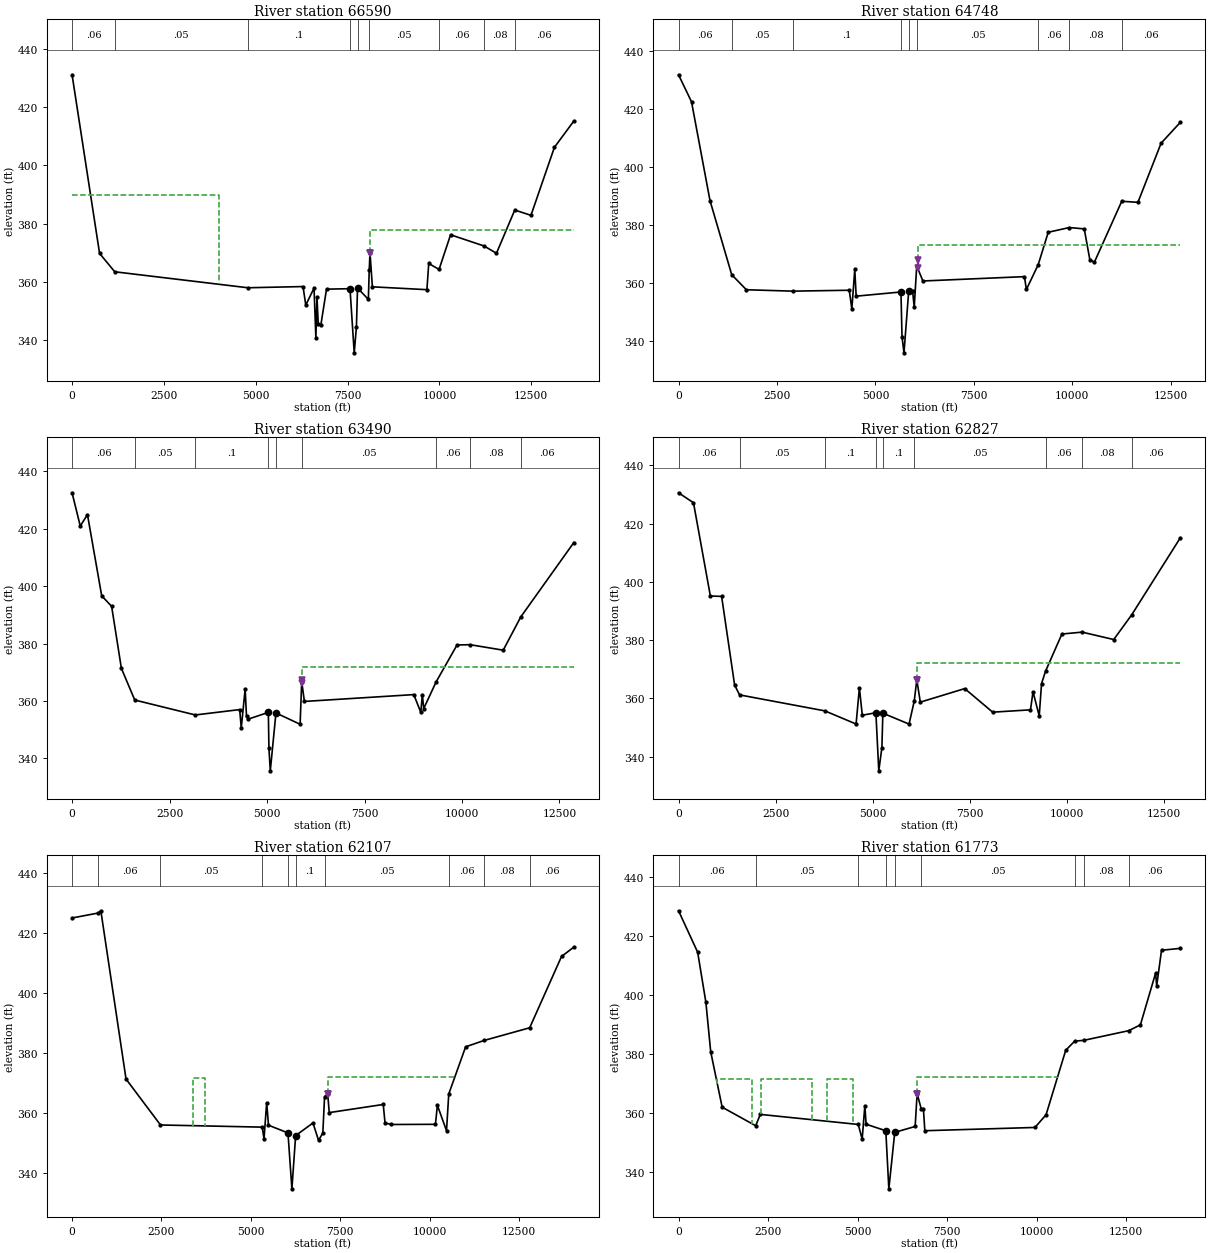
Type RM Length L Ch R = 1 ,66590   ,1845.22,1842.01,825.61
BEGIN DESCRIPTION:
ROB - Kaufman LID10
LOB IFA station 4000: flow expansion due to Kaufman LID15 levee upstream
END DESCRIPTION:
XS GIS Cut Line= 5
2593794.774721646927307.588629392590248.669609136926853.69485214
2586155.986521566923946.590758232582493.689384226923308.87746672
 2581153.48373136923448.14654514
#Sta/Elev= 30
       0  431.18  748.96  369.79 1161.54  363.47 4784.37  357.98 6287.38  358.39
  6362.3  352.01 6587.08  357.88 6637.03  340.84    6667  354.67 6701.97  345.36
  6771.9  345.12 6926.75   357.5 7566.11  357.66    7681  335.61 7740.94  344.51
 7770.91  357.89 8065.62  353.99 8089.95  364.14 8110.57  369.99 8175.51   358.3
  9659.4  357.32 9709.37  366.32 9990.46  364.2810303.98  376.19 11216.7  372.33
11553.15  369.8312050.78  384.69 12492.3  382.8713131.05  406.2613660.02  415.29
#Mann= 9 ,-1 , 0
       0     .06       0 1161.54     .05       0 4784.37      .1       0
 7566.11    .045       0 7770.91      .1       0 8089.95     .05       0
 9990.46     .06       0 11216.7     .08       012050.78     .06       0
Levee=0,,,-1,8110.57,369.99,,
#XS Ineff= 2 , 0
       0    4000     390 8110.57       0     378
Permanent Ineff=
       F       F
Bank Sta=7566.11,7770.91
XS Rating Curve= 0 ,0
Exp/Cntr=0.3,0.1

Type RM Length L Ch R = 1 ,64748   ,1485.94,1258.36,388.27
BEGIN DESCRIPTION:
ROB - Kaufman LID10
END DESCRIPTION:
XS GIS Cut Line= 5
2593534.358247736925267.657997982590784.831594566924883.80279456
2587155.986490066923404.924190642582493.076524566923110.03665707
2581136.122545566923335.29932989
#Sta/Elev= 30
       0  431.73  329.55  422.42   798.9  388.36 1350.37  362.81 1722.64  357.62
 2900.35  357.14 4335.63  357.45  4400.6  350.99 4475.58  364.62 4510.56  355.41
 5648.22  356.85 5675.12  341.43  5725.1  335.87 5845.05  357.18 5945.01  357.03
    5985   351.6 6048.89  365.87 6204.92  360.64 8783.47  362.14 8833.44  357.71
 9133.62  366.27 9388.11  377.44 9922.23  379.0610302.58  378.6110447.49  367.78
10562.42  367.1911254.62  388.1211665.99  387.7612254.09  408.1412742.51  415.34
#Mann= 9 ,-1 , 0
       0     .06       0 1350.37     .05       0 2900.35      .1       0
 5648.22    .045       0 5845.05      .1       0 6048.89     .05       0
 9133.62     .06       0 9922.23     .08       011254.62     .06       0
Levee=0,,,-1,6069.97,367.73,,
#XS Ineff= 2 , 0
       0                 6069.97       0     373
Permanent Ineff=
       F       F
Bank Sta=5648.22,5845.05
XS Rating Curve= 0 ,0
Exp/Cntr=0.3,0.1

Type RM Length L Ch R = 1 ,63490   ,807.88,662.89,436.52
BEGIN DESCRIPTION:
ROB - Kaufman LID10
END DESCRIPTION:
XS GIS Cut Line= 5
2593933.663879566923913.491414982590188.802274816923115.88999181
2584451.816373476922944.351949072582493.237613476922968.49396114
2581170.844917066923196.41050006
#Sta/Elev= 30
       0  432.54  209.94  420.96  394.88  424.94  759.77  396.67  1014.7  392.98
 1264.62   371.4 1607.43  360.36 3161.18  355.16 4298.83  357.03 4338.82  350.59
 4438.81  364.14 4473.81  354.65 4518.81  353.72 5033.76  356.05 5048.76  343.51
 5083.75   335.7 5228.74  355.86 5848.68  351.92 5889.26  366.81 5958.67  359.87
 8763.46  362.25 8943.46   356.1 8983.46  362.23 9018.46  357.39 9337.22   366.7
 9873.28  379.5410209.89  379.6311057.58  377.7211507.35   389.312869.15  415.22
#Mann= 9 ,-1 , 0
       0     .06       0 1607.43     .05       0 3161.18      .1       0
 5033.76    .045       0 5228.74      .1       0 5889.26     .05       0
 9337.22     .06       010209.89     .08       011507.35     .06       0
Levee=0,,,-1,5893.68,367.28,,
#XS Ineff= 2 , 0
       0                 5893.68       0     372
Permanent Ineff=
       F       F
Bank Sta=5033.76,5228.74
XS Rating Curve= 0 ,0
Exp/Cntr=0.3,0.1

Type RM Length L Ch R = 1 ,62827   ,933.3,720.09,426.45
BEGIN DESCRIPTION:
ROB - Kaufman LID10
END DESCRIPTION:
XS GIS Cut Line= 4
2594063.871952476922793.699691312590222.728059966922330.61728415
2582458.835123236922834.600528152581205.567288556923074.88252789
#Sta/Elev= 30
       0  430.59   384.9  427.17  819.78  395.17  1109.7  395.02 1444.61   364.6
 1571.64  361.22 3769.35  355.73 4573.52  351.22 4658.47  363.65 4733.42  354.24
 5083.21  355.09 5158.16  335.15 5238.11  343.15  5263.1  354.94 5937.68   351.2
 6071.76   359.1 6137.56  366.42  6227.5  358.73  7371.8  363.38 8091.36  355.29
 9065.78  356.09 9130.75  362.29 9290.65  354.01 9350.62   365.1 9454.11  369.38
 9875.31  382.1110394.37  382.7611209.53  380.22   11675  388.7412925.27  415.13
#Mann= 9 ,-1 , 0
       0     .06       0 1571.64     .05       0 3769.35      .1       0
 5083.21    .045       0  5263.1      .1       0 6071.76     .05       0
 9454.11     .06       010394.37     .08       0   11675     .06       0
Levee=0,,,-1,6137.56,366.42,,
#XS Ineff= 2 , 0
       0                 6137.56       0     372
Permanent Ineff=
       F       F
Bank Sta=5083.21,5263.1
XS Rating Curve= 0 ,0
Exp/Cntr=0.3,0.1

Type RM Length L Ch R = 1 ,62107   ,347.84,334.05,325.77
BEGIN DESCRIPTION:
ROB - Kaufman LID10
END DESCRIPTION:
XS GIS Cut Line= 5
2595053.455275136921161.755120562590342.430904556921429.73555572
2584311.848149466922553.571234552582467.506693816922728.78577915
2581162.16448823 6922979.3964984
#Sta/Elev= 30
       0  424.87  732.47  426.52  804.77  427.27 1509.56  371.22 2473.35  355.93
 5318.47  355.21 5368.56  351.33 5443.56   363.4 5493.55  355.85 6038.49  353.29
 6148.48  334.66 6253.47  352.39 6738.42   356.6  6893.4  350.81 7013.39  353.24
 7062.29   365.3 7148.37  366.41 7193.37  360.05 8703.23  362.76 8753.22  356.64
 8923.21  356.0910163.13  356.1510218.12  362.48 10473.1  354.0210535.91  366.26
11007.88  381.9611525.04  384.0812799.03   388.313690.13  412.0514034.93  415.17
#Mann= 10 ,-1 , 0
       0     .05       0  732.47     .06       0 2473.35     .05       0
 5318.47      .1       0 6038.49    .045       0 6253.47      .1       0
 7062.29     .05       010535.91     .06       011525.04     .08       0
12799.03     .06       0
Levee=0,,,-1,7148.37,366.41,,
#XS Ineff= 2 ,-1
 3388.51 3718.61   371.5 7148.37   10713     372
Permanent Ineff=
       F       F
Bank Sta=6038.49,6253.47
XS Rating Curve= 0 ,0
Exp/Cntr=0.5,0.3

Type RM Length L Ch R = 1 ,61773   ,508.19,534.06,519.89
BEGIN DESCRIPTION:
US Bridge
ROB - Kaufman LID10
END DESCRIPTION:
XS GIS Cut Line= 3
2594662.83040021 6920562.79700092593532.223081386920487.75253156
2580875.706071636922875.23004006
#Sta/Elev= 30
       0  428.56   534.1  414.49  763.72  397.49  898.49  380.69 1218.09  361.88
 2154.83  355.58 2283.07  359.43  5018.7  356.02 5127.99  351.03 5202.99   362.4
 5237.99   356.1 5787.97  353.88 5872.96  334.16 6037.96  353.33 6607.94  355.34
 6662.93  366.49 6781.16  361.16 6837.93  361.41 6877.93  353.89 9952.87     355
10262.87  359.2910812.87  381.2211062.84   384.311319.55  384.5812573.11  387.86
12897.87  389.8313322.87  407.4113352.87  403.0813487.87  415.1614012.87   415.8
#Mann= 9 ,-1 , 0
       0     .06       0 2154.83     .05       0  5018.7      .1       0
 5787.97    .045       0 6037.96      .1       0 6781.16     .05       0
11062.84     .06       011319.55     .08       012573.11     .06       0
Levee=0,,,-1,6662.93,366.49,,
#XS Ineff= 4 ,-1
    1086    2065   371.5    2295    3715   371.5    4140    4860   371.5
 6662.93   10575     372
Permanent Ineff=
       F       F       F       F
Bank Sta=5787.97,6037.96
XS Rating Curve= 0 ,0
Exp/Cntr=0.5,0.3

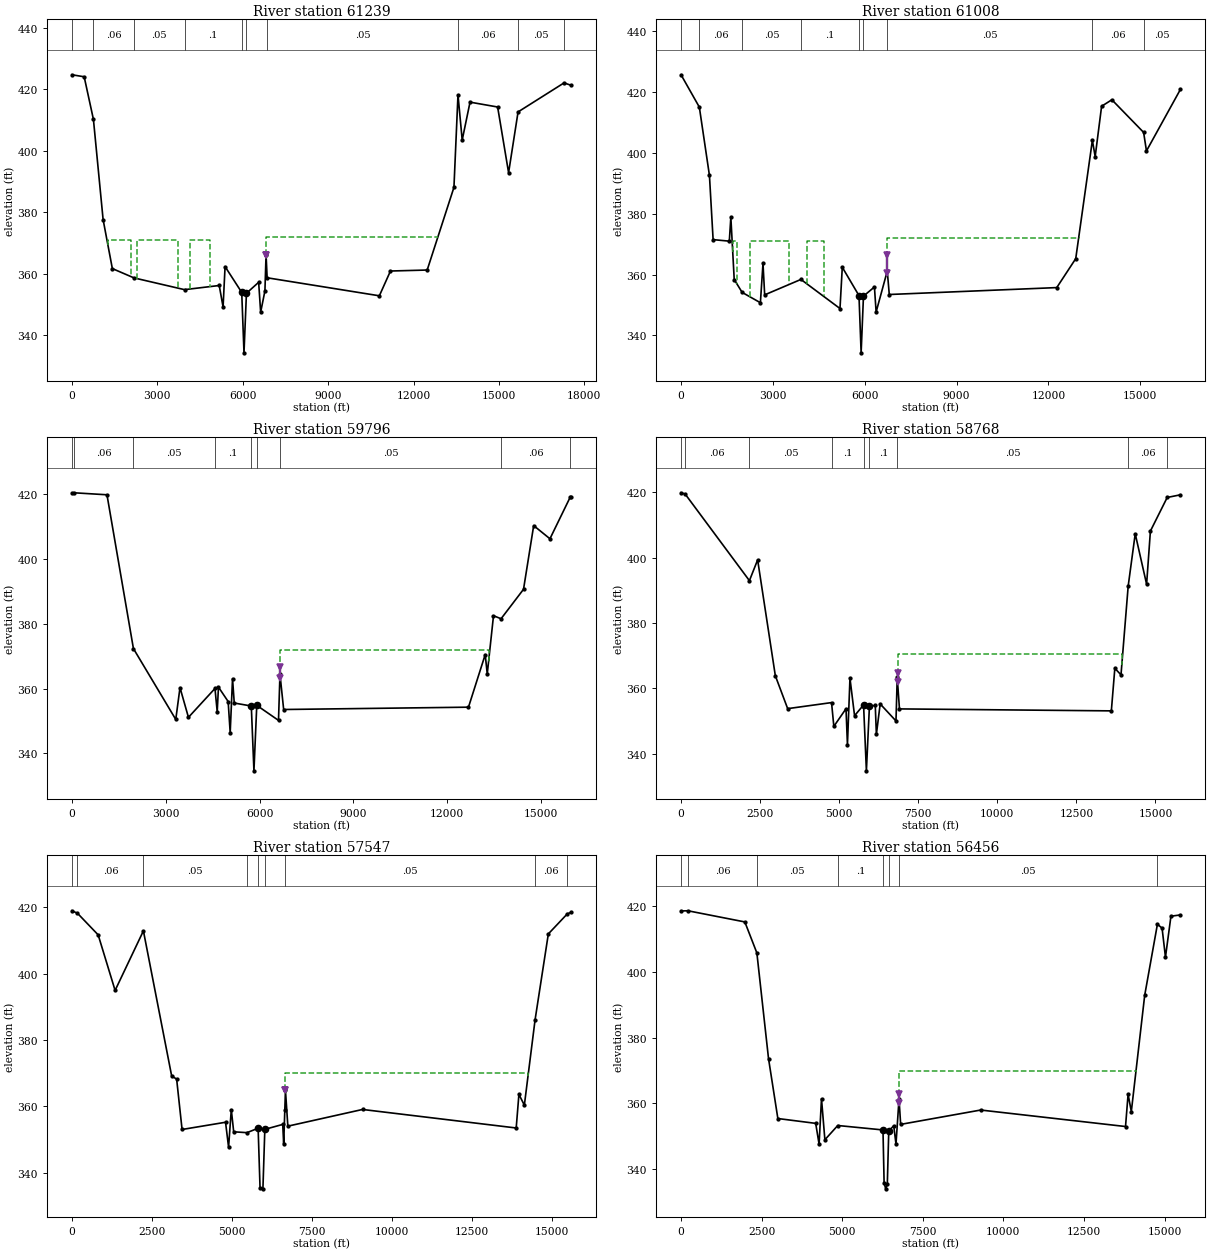
Type RM Length L Ch R = 1 ,61239   ,231.81,230.66,231.9
BEGIN DESCRIPTION:
DS Bridge
ROB - Kaufman LID10
END DESCRIPTION:
XS GIS Cut Line= 3
2594565.608153726919547.172063652593109.176027226920059.67431948
2577378.631044816922982.72752848
#Sta/Elev= 30
       0  424.68  429.71  424.03  754.27  410.18 1094.27   377.6 1419.05  361.65
 2180.49  358.62 3954.08   354.8 5173.94  356.15 5308.94  349.16 5378.94   362.3
 5964.02  353.91 6043.79  334.25 6129.55  353.63 6558.94  357.19 6628.94  347.46
 6778.94   354.4 6818.94  366.23 6856.56  358.6610798.94   352.811188.94  360.86
12478.94  361.1813418.94  388.06   13561  418.1713708.94  403.4613983.94  415.78
14953.94   414.215338.94  392.8315671.59   412.617286.68  422.0417543.94  421.23
#Mann= 10 ,-1 , 0
       0     .07       0  754.27     .06       0 2180.49     .05       0
 3954.08      .1       0 5964.02    .045       0 6129.55      .1       0
 6856.56     .05       0   13561     .06       015671.59     .05       0
17286.68     .07       0
Levee=0,,,-1,6818.94,366.23,,
#XS Ineff= 4 ,-1
    1265    2065     371    2295    3715     371    4145    4860     371
 6818.94   12857     372
Permanent Ineff=
       F       F       F       F
Bank Sta=5964.02,6129.55
XS Rating Curve= 0 ,0
Exp/Cntr=0.5,0.3

Type RM Length L Ch R = 1 ,61008   ,1142.5,1211.73,1352.69
BEGIN DESCRIPTION:
ROB - Kaufman LID10
END DESCRIPTION:
XS GIS Cut Line= 3
2594336.441617316919286.755261642593052.01341188 6919836.3673514
2578387.745824476922559.55055331
#Sta/Elev= 30
       0  425.67   597.9  415.05  928.06  392.58 1047.81   371.5 1577.08     371
 1627.08  378.88 1737.08  358.39 1996.36  354.16 2592.07  350.77 2677.07  363.66
 2732.07  353.35 3916.25  358.42 5192.04  348.86 5267.04  362.42 5812.14  353.11
 5882.48   334.3 5958.82  352.94 6317.03  355.94 6372.03  347.71 6736.21  361.17
 6802.02  353.47   12272  355.74   12892  365.2513435.23  404.11   13527  398.79
   13737  415.33   14072  417.4615109.12  406.74   15202  400.65   16312  420.88
#Mann= 9 ,-1 , 0
       0     .07       0   597.9     .06       0 1996.36     .05       0
 3916.25      .1       0 5812.14    .045       0 5958.82      .1       0
 6736.21     .05       013435.23     .06       015109.12     .05       0
Levee=0,,,-1,6717.02,366.29,,
#XS Ineff= 4 ,-1
    1688 1828.11     371 2264.67 3529.53     371  4104.3 4662.68     371
 6717.02   13017     372
Permanent Ineff=
       F       F       F       F
Bank Sta=5812.14,5958.82
XS Rating Curve= 0 ,0
Exp/Cntr=0.3,0.1

Type RM Length L Ch R = 1 ,59796   ,966.46,1028.06,1097.97
BEGIN DESCRIPTION:
ROB - Kaufman LID10
END DESCRIPTION:
XS GIS Cut Line= 2
2594279.149737136918630.505261812578471.192179896920887.38263781
#Sta/Elev= 30
       0  420.43   63.08  420.49 1119.88  419.87 1965.58  372.35 3319.63  350.46
 3454.62  360.29 3724.59  351.11 4573.28  360.03 4644.49  352.85 4684.49  360.45
 4994.46     356 5059.45  346.36 5134.44  363.07 5189.44  355.53 5734.38  354.61
 5818.88  334.58 5909.37  354.82  6604.3  350.17 6651.09  364.47 6769.28  353.53
12678.61  354.2513213.55   370.513278.54  364.5113478.52  382.5113720.39  381.57
14438.41  390.6714763.37  410.3515283.31  406.28 15933.3  419.1815968.22  419.16
#Mann= 9 ,-1 , 0
       0     .07       0   63.08     .06       0 1965.58     .05       0
 4573.28      .1       0 5734.38    .045       0 5909.37      .1       0
 6651.09     .05       013720.39     .06       0 15933.3     .05       0
Levee=0,,,-1,6664.29,366.53,,
#XS Ineff= 2 ,-1
                         6664.29   13321     372
Permanent Ineff=
       F       F
Bank Sta=5734.38,5909.37
XS Rating Curve= 0 ,0
Exp/Cntr=0.3,0.1

Type RM Length L Ch R = 1 ,58768   ,995.35,1220.81,1240.8
BEGIN DESCRIPTION:
ROB - Kaufman LID10
END DESCRIPTION:
XS GIS Cut Line= 3
2594331.233294386917927.380355732591470.356470216918107.56076965
2578627.442195486919550.57724056
#Sta/Elev= 30
       0  419.81  129.38  419.44 2162.04  392.95 2422.08   399.3 2981.54  363.89
 3371.51  353.83 4758.75  355.68 4831.38  348.41 5216.35  353.81 5261.35   342.8
 5341.34  363.13 5486.33  351.67  5771.3  354.96  5860.8  334.82 5956.29  354.55
 6141.27   354.8 6176.27  345.96 6296.26  355.27 6796.21  350.07 6835.42  363.37
  6906.2  353.75 13605.3  353.1513715.28  366.1513910.25  364.1714137.73   391.3
14360.18  407.2714720.13  391.8614840.11  408.1115371.36  418.3815789.97  419.19
#Mann= 9 ,-1 , 0
       0     .07       0  129.38     .06       0 2162.04     .05       0
 4758.75      .1       0  5771.3    .045       0 5956.29      .1       0
 6835.42     .05       014137.73     .06       015371.36     .05       0
Levee=0,,,-1,6846.21,364.63,,
#XS Ineff= 1 ,-1
 6846.21   13936   370.5
Permanent Ineff=
       F
Bank Sta=5771.3,5956.29
XS Rating Curve= 0 ,0
Exp/Cntr=0.3,0.1

Type RM Length L Ch R = 1 ,57547   ,837.69,1091.62,1276.98
BEGIN DESCRIPTION:
ROB - Kaufman LID10
END DESCRIPTION:
XS GIS Cut Line= 5
2594326.024971476917661.755230812591898.227989816917634.89307982
2588885.705799646917144.938679142588193.448982066917317.00920114
2578809.733825646918100.92429997
#Sta/Elev= 30
       0  418.98  171.57  418.24  819.31  411.71 1348.86  394.95 2233.37  412.92
 3117.28  369.11 3272.13   368.2 3441.97  352.99 4800.67  355.17 4895.57  347.66
 4980.49  358.98 5055.42  352.29 5469.52  352.03 5819.22  353.37 5879.08  335.35
 5968.87  335.08 6028.73  353.03  6588.2  354.52 6618.19  348.63 6653.62  358.95
 6673.17  364.84 6748.15  353.99 9082.28  359.03 13885.4  353.4413970.37  363.58
 14140.3  360.33 14476.1  386.1214890.01     41215485.07  418.0715609.73  418.52
#Mann= 9 ,-1 , 0
       0     .07       0  171.57     .06       0 2233.37     .05       0
 5469.52      .1       0 5819.22    .045       0 6028.73      .1       0
 6653.62     .05       0 14476.1     .06       015485.07     .05       0
Levee=0,,,-1,6673.17,364.84,,
#XS Ineff= 1 ,-1
 6673.17   14256     370
Permanent Ineff=
       F
Bank Sta=5819.22,6028.73
XS Rating Curve= 0 ,0
Exp/Cntr=0.3,0.1

Type RM Length L Ch R = 1 ,56456   ,1050.99,1649.02,1533
BEGIN DESCRIPTION:
ROB - Kaufman LID10
END DESCRIPTION:
XS GIS Cut Line= 5
2594336.441617316917515.921861072592019.932142726917189.06621556
 2588521.1225393 6916124.10509092587948.01082464 6916251.7918434
2579038.787501386916385.50515865
#Sta/Elev= 30
       0  418.48  214.12  418.53 1979.53  415.14 2352.61  405.73 2714.17  373.65
 3003.95  355.42 4178.08  353.95    4283  347.63 4357.95  361.42 4462.87  348.97
 4862.76   353.3 6265.43  351.95 6300.26  335.86 6350.02  334.06 6399.78  335.47
 6444.57  351.62 6598.88  353.22 6668.84  347.66 6763.26  361.36 6813.76  353.64
 9297.36     35813789.86  352.9913869.82  362.7813969.76  357.5314384.53  392.83
14779.46  414.4414924.23  413.2515029.17  404.4415199.08  416.8815493.92  417.27
#Mann= 8 ,-1 , 0
       0     .07       0  214.12     .06       0 2352.61     .05       0
 4862.76      .1       0 6265.43    .045       0 6444.57      .1       0
 6763.26     .05       014779.46     .06       0
Levee=0,,,-1,6753.8,362.83,,
#XS Ineff= 1 ,-1
  6753.8   14146     370
Permanent Ineff=
       F
Bank Sta=6265.43,6444.57
XS Rating Curve= 0 ,0
Exp/Cntr=0.3,0.1

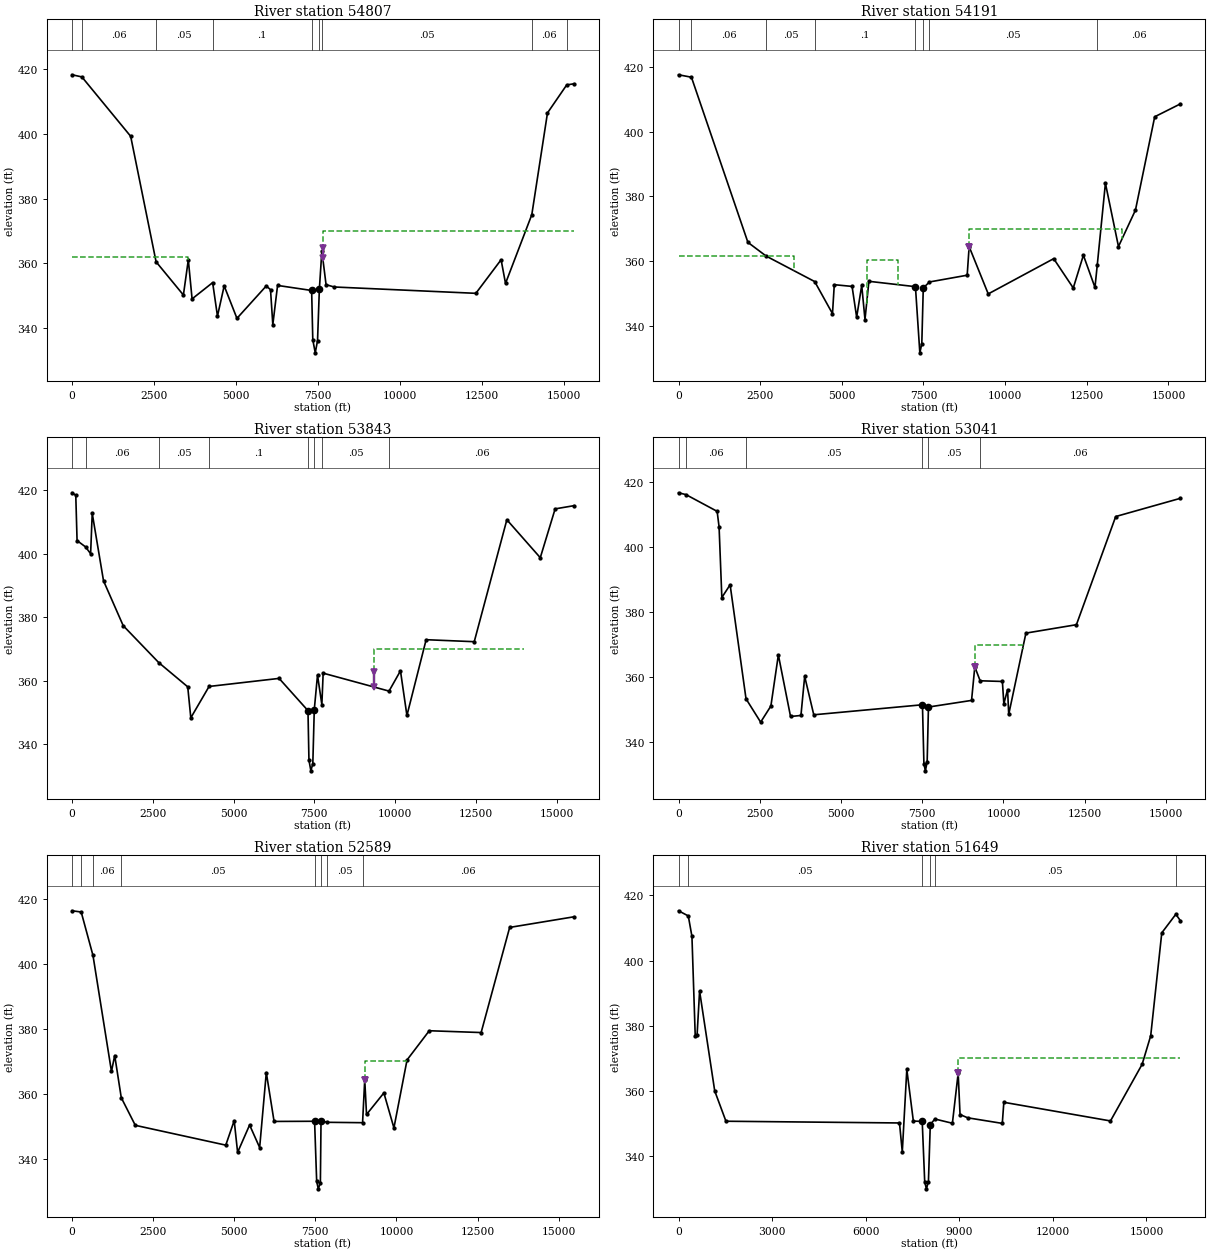
Type RM Length L Ch R = 1 ,54807   ,343.73,615.72,961.48
BEGIN DESCRIPTION:
ROB - Kaufman LID10
LOB IFA Station 3546.4: flow contraction due to natural high ground
END DESCRIPTION:
XS GIS Cut Line= 4
2594361.759808146917054.116354232592180.812398396916601.35708915
2588073.222844566914846.860926232579461.964476566914605.99132922
#Sta/Elev= 30
       0  418.24  299.19  417.58 1787.96  399.24 2563.43  360.47 3396.56  350.22
 3546.44  361.09 3661.36  349.02 4288.79  354.05 4435.77   343.7 4640.62  353.04
 5030.33  343.01 5924.66  353.02 6054.56  351.86 6124.51  341.07  6269.4  353.18
 7309.04  351.62 7344.04  336.42 7419.04  332.36 7489.03  336.14 7544.03  351.93
 7620.78  363.83 7749.02  353.42    7994   352.712318.99  350.7413088.99  361.11
13223.99  353.8114025.72  375.0214503.99  406.4515091.26  415.1115308.99  415.45
#Mann= 9 ,-1 , 0
       0     .07       0  299.19     .06       0 2563.43     .05       0
 4288.79      .1       0 7309.04    .045       0 7544.03      .1       0
 7620.78     .05       014025.72     .06       015091.26     .05       0
Levee=0,,,-1,7649.02,364.66,,
#XS Ineff= 2 , 0
       0  3546.4     362 7649.02       0     370
Permanent Ineff=
       F       F
Bank Sta=7309.04,7544.03
XS Rating Curve= 0 ,0
Exp/Cntr=0.5,0.3

Type RM Length L Ch R = 1 ,54191   ,340.54,347.69,879.16
BEGIN DESCRIPTION:
ROB - Kaufman LID10
LOB IFA Station 3531.8: flow contraction due to natural high ground upstream
LOB IFA Station 5759-6715: flow contraction due to natural high ground downstream
END DESCRIPTION:
XS GIS Cut Line= 4
2594417.912911066916815.486582152592178.329463726916341.52821247
2586841.523864396913971.736364142579640.135051976913270.34767506
#Sta/Elev= 30
       0  417.47  394.86  416.72 2124.25  365.88 2684.15  361.65 4168.99  353.81
 4713.93  343.94 4768.92  352.85 5313.86  352.32 5453.85  342.83 5608.83  352.64
 5708.82  342.13 5828.81  353.89 7253.65  352.24 7388.64  331.87 7448.63  334.68
 7493.63  351.85 7683.61  353.69 8838.14  355.77 8898.11  364.57 9482.76  350.01
11486.59  360.8612086.24  351.8312396.06  361.9112750.85  352.0112820.81  358.88
13070.66  384.0813470.43  364.5913990.12   375.814579.78  404.5415364.32   408.5
#Mann= 8 ,-1 , 0
       0     .07       0  394.86     .06       0 2684.15     .05       0
 4168.99      .1       0 7253.65    .045       0 7493.63      .1       0
 7683.61     .05       012820.81     .06       0
Levee=0,,,-1,8898.11,364.57,,
#XS Ineff= 3 ,-1
       0  3531.8   361.6    5759    6715   360.5 8898.11   13579     370
Permanent Ineff=
       F       F       F
Bank Sta=7253.65,7493.63
XS Rating Curve= 0 ,0
Exp/Cntr=0.5,0.3

Type RM Length L Ch R = 1 ,53843   ,1413.54,802.88,201.58
BEGIN DESCRIPTION:
ROB - Kaufman LID10
END DESCRIPTION:
XS GIS Cut Line= 4
2594458.982054646916640.921970652592239.655128466916177.40550923
2585711.877173566913031.572233972579776.634450886912001.82462156
#Sta/Elev= 30
       0  419.28  114.86  418.49  154.81  404.22   417.3  402.23  574.29  400.08
  624.23   412.8   973.8  391.54 1583.05  377.42 2683.57  365.79 3581.54  358.15
 3676.49  348.39 4242.17  358.27 6410.11  360.81 7304.66  350.65 7334.65  335.05
 7394.62  331.69 7454.59     334 7499.57  350.95 7599.52  361.86 7734.38  352.55
 7774.43  362.46 9814.35  356.8110168.32  363.1910368.28  349.1310963.16     373
12452.87  372.3713462.67  410.7814497.47  398.8314957.38  414.2115537.27  415.21
#Mann= 8 ,-1 , 0
       0     .07       0   417.3     .06       0 2683.57     .05       0
 4242.17      .1       0 7304.66    .045       0 7499.57      .1       0
 7734.38     .05       0 9814.35     .06       0
Levee=0,,,-1,9348.54,362.89,,
#XS Ineff= 1 ,-1
 9348.54   14000     370
Permanent Ineff=
       F
Bank Sta=7304.66,7499.57
XS Rating Curve= 0 ,0
Exp/Cntr=0.8,0.6

Type RM Length L Ch R = 1 ,53041   ,887.56,451.48,215
BEGIN DESCRIPTION:
ROB - Kaufman 5 West
END DESCRIPTION:
XS GIS Cut Line= 6
2594327.634876396916055.069795892592563.746015716915687.01442964
2587658.814880716913145.118266732587098.468232396913242.56984347
2585772.079480986912839.792105732579695.69038706 6911825.9030574
#Sta/Elev= 30
       0  416.78   229.6  416.21 1187.94  411.06 1247.84  406.25 1332.69  384.51
 1587.25  388.43 2076.85  353.29 2526.81   346.1 2841.78  351.07 3071.76  366.81
 3446.73  347.85  3766.7  348.16 3881.69  360.21 4161.66  348.37 7505.91  351.46
 7550.82  333.36 7595.72   331.1  7650.6  333.79 7690.52  350.76    9017   352.8
 9116.72  363.14 9281.27  358.85 9965.74  358.64 10010.7  351.7610125.61  356.14
10160.59   348.510690.17  373.5412243.96  376.1313453.01  409.4615441.46  415.07
#Mann= 6 ,-1 , 0
       0     .07       0   229.6     .06       0 2076.85     .05       0
 7505.91    .045       0 7690.52     .05       0 9281.27     .06       0
Levee=0,,,-1,9116.72,363.14,,
#XS Ineff= 1 ,-1
 9116.72   10587     370
Permanent Ineff=
       F
Bank Sta=7505.91,7690.52
XS Rating Curve= 0 ,0
Exp/Cntr=0.5,0.3

Type RM Length L Ch R = 1 ,52589   ,1237.78,939.78,994.4
BEGIN DESCRIPTION:
ROB - Kaufman 5 West
END DESCRIPTION:
XS GIS Cut Line= 4
2594264.537561646915609.672064652587522.424733556912700.27696481
2586980.75816597 6912825.27704292579505.367276896911622.05044673
#Sta/Elev= 30
       0  416.45  281.37  416.07   644.9  402.67 1214.68  366.92 1314.65  371.83
 1516.82  358.83 1949.48  350.31 4738.75   344.2 4998.68  351.75 5103.65  341.97
 5473.54  350.41 5783.46  343.46  5988.4  366.58 6228.33  351.51 7477.03  351.56
 7541.55  333.01 7591.19  330.73 7655.71   332.6 7675.57  351.66 7872.82  351.24
 8956.65  351.12 9023.46  364.39 9078.43  353.65 9613.22   360.3 9923.09  349.52
10327.92  370.4711012.64  379.4712611.99  378.9113491.63  411.3215470.82  414.59
#Mann= 8 ,-1 , 0
       0     .07       0  281.37     .05       0   644.9     .06       0
 1516.82     .05       0 7477.03    .045       0 7675.57     .05       0
 7872.82     .05       0 8956.65     .06       0
Levee=0,,,-1,9023.46,364.39,,
#XS Ineff= 1 ,-1
 9023.46   10319     370
Permanent Ineff=
       F
Bank Sta=7477.03,7675.57
XS Rating Curve= 0 ,0
Exp/Cntr=0.3,0.1

Type RM Length L Ch R = 1 ,51649   ,976.98,1004.9,1121.02
BEGIN DESCRIPTION:
ROB - Kaufman 5 West
END DESCRIPTION:
XS GIS Cut Line= 5
2594550.648537966914266.963463982588652.855215486912067.51970014
2587215.985057736911850.876432642586709.924718146911887.77694939
2578983.345026976910609.60496506
#Sta/Elev= 30
       0  415.23  313.12  413.65  429.97  407.36  534.96  376.97  594.96  377.24
  674.95  390.66 1159.92  360.07 1519.89  350.79 7083.55  350.26 7173.43  341.38
 7318.25  366.65 7527.98  350.84 7812.37  350.74 7891.97  332.27 7946.69  330.09
 8011.36   332.3 8071.05  349.79 8218.76  351.47 8779.91  350.17 8964.83  365.51
 9024.81  352.85 9269.72  351.8410379.28  350.1310429.26  356.5913847.93  350.88
14862.53  368.2215137.42  376.9615492.28  408.4715943.32  414.1716087.05  412.22
#Mann= 6 ,-1 , 0
       0     .07       0  313.12     .05       0 7812.37    .045       0
 8071.05     .05       0 8218.76     .05       015943.32     .06       0
Levee=0,,,-1,8964.83,365.51,,
#XS Ineff= 2 , 0
       0                 8964.83       0     370
Permanent Ineff=
       F       F
Bank Sta=7812.37,8071.05
XS Rating Curve= 0 ,0
Exp/Cntr=0.3,0.1