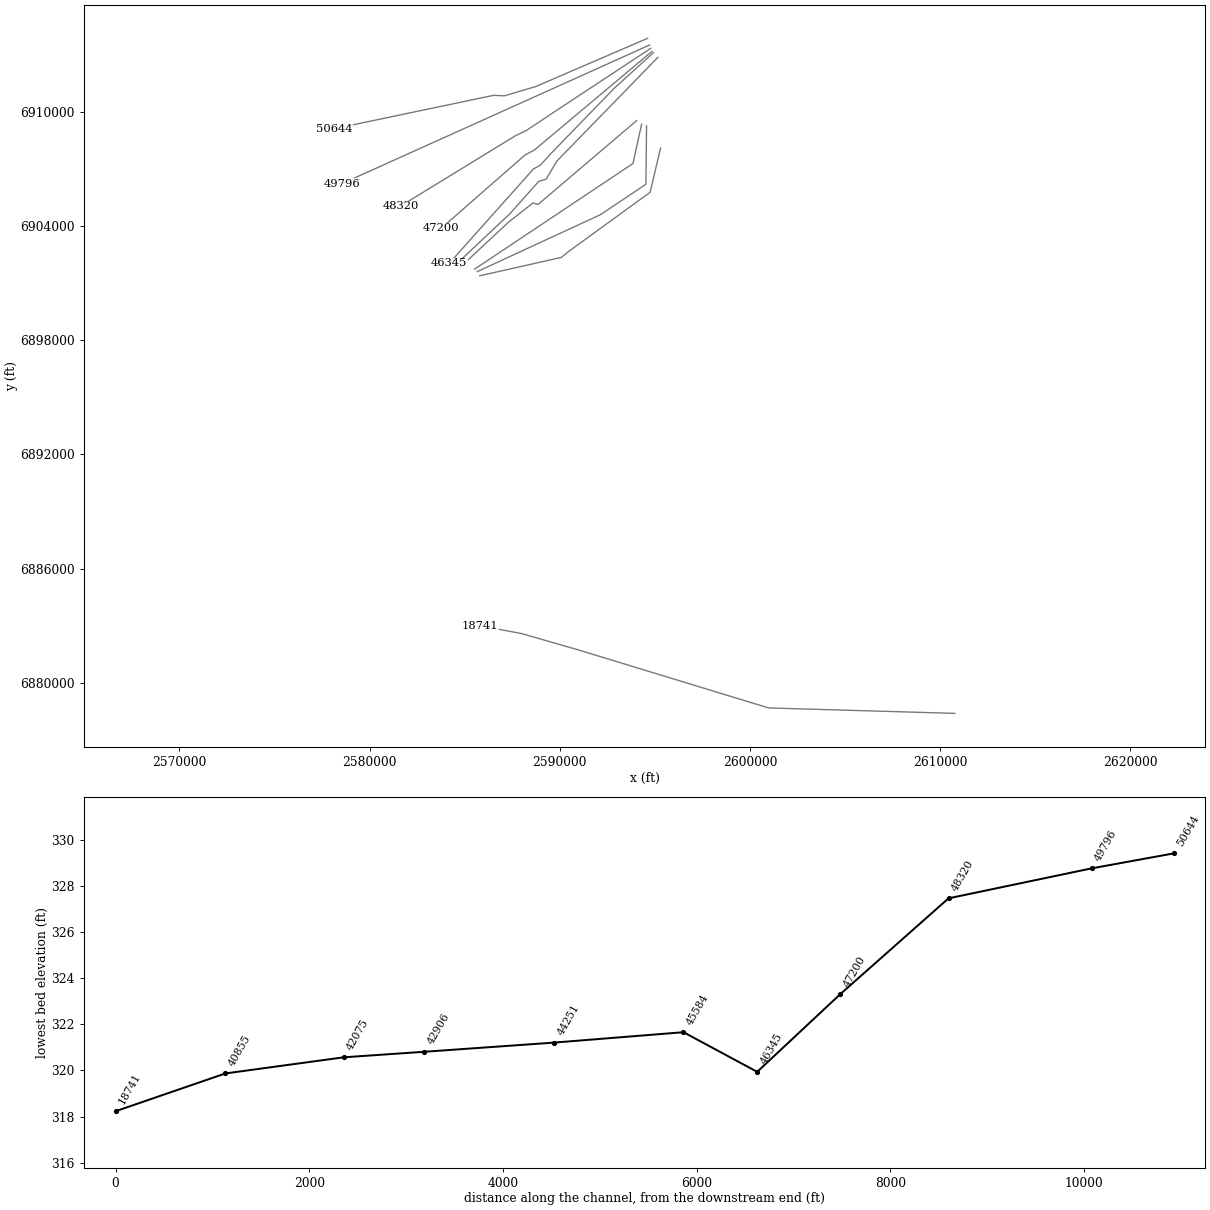
HEC-RAS study EF_FEMA.prj: East_Fork_FEMA

--- EF_FEMA.g02 (geometry) --- (continued)

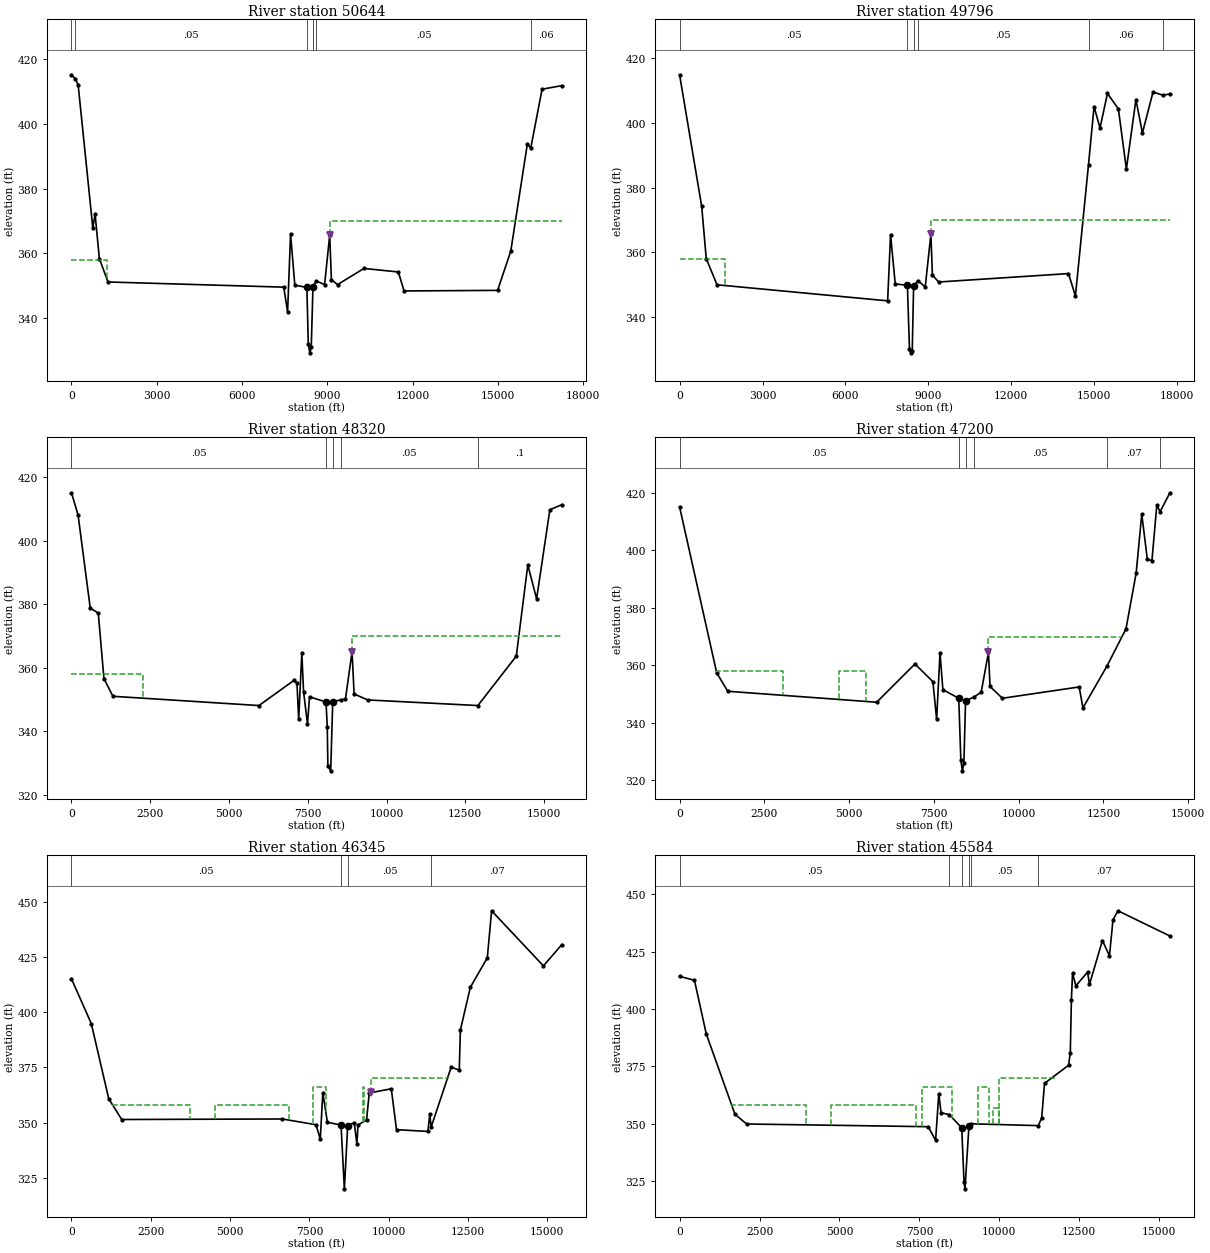
Type RM Length L Ch R = 1 ,50644   ,692.75,848.13,1501.09
BEGIN DESCRIPTION:
ROB - Kaufman 5 West
END DESCRIPTION:
XS GIS Cut Line= 5
2594613.148741056913891.96355781 2588721.42922536911351.62054139
2587079.716301386910866.943689232586513.192171986910892.49875623
2578149.030422646909137.24143998
#Sta/Elev= 30
       0  415.01  139.84  413.74  234.86  411.84  749.54  367.84  829.49  372.16
   979.4  358.44 1284.21  351.23 7464.13  349.64 7598.88  342.03 7703.68  365.95
  7853.4  350.26 8277.12  349.55 8326.87  332.07 8381.59  329.42 8431.34  331.13
 8491.03  349.78 8603.38  351.56 8899.91  350.42 9079.84  365.62 9139.82  351.96
 9354.73  350.4110284.37   355.4 11493.9  354.3111693.82  348.4714982.53  348.65
15447.35  360.7416027.12  393.5916151.85  392.5216546.92  410.5717241.65  411.66
#Mann= 6 ,-1 , 0
       0     .07       0  139.84     .05       0 8277.12    .045       0
 8491.03     .05       0 8603.38     .05       016151.85     .06       0
Levee=0,,,-1,9079.84,365.62,,
#XS Ineff= 2 , 0
       0    1241     358 9079.84       0     370
Permanent Ineff=
       F       F
Bank Sta=8277.12,8491.03
XS Rating Curve= 0 ,0
Exp/Cntr=0.3,0.1

Type RM Length L Ch R = 1 ,49796   ,1452.91,1476.31,1787.04
BEGIN DESCRIPTION:
ROB - Kaufman 5 West
END DESCRIPTION:
XS GIS Cut Line= 2
 2594722.52352236913543.005266232578550.505997646906250.95653014
#Sta/Elev= 30
       0  414.94  799.77  374.16  964.73  357.95 1354.62  349.86 7527.86  344.88
 7632.83  365.42 7802.79  350.12 8242.66  349.71 8317.64  329.84 8362.63  328.77
 8417.62  329.43  8467.6   349.6 8625.57  351.16  8887.5  349.18 9092.44  365.52
 9147.43  352.88 9372.37  350.7214071.18  353.3314321.12  346.38 14795.5   387.1
14995.95  405.0815210.89  398.4515480.82  409.1515875.72  404.3616165.65  385.74
16510.54  407.2616745.45  396.88 17130.3  409.6317483.55  408.6117740.06  408.99
#Mann= 6 ,-1 , 0
       0     .05       0 8242.66    .045       0  8467.6     .05       0
 8625.57     .05       0 14795.5     .06       017483.55     .07       0
Levee=0,,,-1,9092.44,365.52,,
#XS Ineff= 2 , 0
       0    1632     358 9092.44       0     370
Permanent Ineff=
       F       F
Bank Sta=8242.66,8467.6
XS Rating Curve= 0 ,0
Exp/Cntr=0.3,0.1

Type RM Length L Ch R = 1 ,48320   ,1117.07,1120.41,1502.42
BEGIN DESCRIPTION:
ROB - Kaufman 5 West
END DESCRIPTION:
XS GIS Cut Line= 5
2594779.815402466913365.921958982589704.538479556910018.63075331
2588220.341316716909033.61041364 2587673.45494336908773.21264048
2581622.233778066905062.72990398
#Sta/Elev= 30
       0  415.16  209.99  408.08  594.97   378.8  849.96  377.21 1029.95  356.57
 1314.93  350.98 5949.71  348.06 7062.67     356 7157.47   355.1 7212.36  343.75
 7312.15  364.63 7367.04  352.38 7491.78  342.27 7556.64   350.8 8079.47   349.2
 8119.19  341.41 8139.05  328.94 8228.42  327.47 8292.96  349.28  8540.6  349.84
 8696.68   350.1 8906.64  365.05 8971.62  351.72 9401.54  349.83 12901.2  348.06
14120.54  363.6614485.46  392.38 14765.4  381.7115185.32  409.8115565.24  411.41
#Mann= 5 ,-1 , 0
       0     .05       0 8079.47    .045       0 8292.96     .05       0
  8540.6     .05       0 12901.2      .1       0
Levee=0,,,-1,8906.64,365.05,,
#XS Ineff= 2 , 0
       0    2257     358 8906.64       0     370
Permanent Ineff=
       F       F
Bank Sta=8079.47,8292.96
XS Rating Curve= 0 ,0
Exp/Cntr=0.3,0.1

Type RM Length L Ch R = 1 ,47200   ,849.08,854.74,1118.27
BEGIN DESCRIPTION:
ROB - Kaufman 5 West
END DESCRIPTION:
XS GIS Cut Line= 4
2594837.106954566913199.255297562588663.692136056908017.22104223
2588173.46641047 6907757.56867442583775.011624726903908.21613689
#Sta/Elev= 30
       0  415.14 1094.33  357.42 1419.13  350.99 5811.45  347.17 6940.76  360.48
 7470.43  354.33 7580.36  341.23  7680.3  364.24 7765.25  351.53 8232.54  348.56
 8294.96  326.94 8339.95   323.3 8384.93  326.08 8434.05   347.7 8676.88  348.95
 8894.84  350.69 9109.84   364.5 9154.84  352.67 9519.84  348.5511784.84  352.49
11894.84  345.1912598.24  359.6313164.84   372.713464.84  392.1113629.84  412.57
13794.84  396.8713929.84  396.4714074.84  415.7714171.05  413.4814459.84  420.05
#Mann= 6 ,-1 , 0
       0     .05       0 8232.54    .045       0 8434.05     .05       0
 8676.88     .05       012598.24     .07       014171.05      .1       0
Levee=0,,,-1,9109.84,364.5,,
#XS Ineff= 3 ,-1
    1087    3062     358    4704    5496     358 9109.84   13020     370
Permanent Ineff=
       F       F       F
Bank Sta=8232.54,8434.05
XS Rating Curve= 0 ,0
Exp/Cntr=0.5,0.3

Type RM Length L Ch R = 1 ,46345   ,777.22,761,653.03
BEGIN DESCRIPTION:
US Bridge
ROB - Kaufman 5 West
END DESCRIPTION:
XS GIS Cut Line= 6
2594925.64877222 6913141.96341742592858.618785566911263.34611164
2589469.304369976907767.00107023 2588993.98773536907233.66191381
2588610.966519716907017.985507892584191.103968386902062.58859456
#Sta/Elev= 30
       0  415.15  624.59  394.86 1174.23  360.77 1583.96  351.38 6647.79  351.62
 7707.65     349 7842.53  342.49 7922.46  363.58 8067.34  350.14 8496.97  348.85
 8601.87  319.94 8706.76  348.58 8912.49  349.94 8996.52  340.32 9031.49  348.89
 9301.28   351.2 9386.21  363.3910080.67  365.3210245.54  346.7811234.77  345.97
11294.72  353.9111336.75   347.911969.19  375.1312223.99  373.7712258.97  391.98
12573.72  411.36 13108.3  424.72 13243.2  446.0314876.92  421.0415456.47  430.69
#Mann= 4 ,-1 , 0
       0     .05       0 8496.97    .045       0 8706.76     .05       0
11336.75     .07       0
Levee=0,,,-1,9441.17,363.87,,
#XS Ineff= 5 ,-1
    1262    3742     358    4520    6857     358    7605    8018     366
  9176.9 9212.61     366 9441.17   11905     370
Permanent Ineff=
       F       F       F       F       F
Bank Sta=8496.97,8706.76
XS Rating Curve= 0 ,0
Exp/Cntr=0.5,0.3

Type RM Length L Ch R = 1 ,45584   ,967.31,1332.53,361.44
BEGIN DESCRIPTION:
DS Bridge
ROB IFA station 9792: flow expansion due to Kaufman 5 West levee upstream
END DESCRIPTION:
XS GIS Cut Line= 6
2595154.815308636912891.963589312589835.605474646907426.51093756
2589282.320491976906482.568599732588894.303223396906370.30307622
 2587378.35317136904669.299588472584516.62497088 6901975.7829939
#Sta/Elev= 30
       0  414.27  464.79  412.55  834.63  389.18 1729.24  354.22 2094.08  349.93
 7776.47  348.74 8006.28  342.75  8106.2  363.12 8176.15  354.84 8436.37  353.99
 8823.08  348.23 8895.26  324.59 8925.18  321.66 9048.47  348.95 9106.64  350.02
 11217.9  349.21 11323.3   352.511413.25  367.6212163.25  375.5212218.25  380.88
12253.25  404.1712288.25  415.6112393.25  410.1212758.25  416.1212818.25   410.8
13223.25  429.8713443.25  423.2113553.25  438.8813708.25  442.8415333.25  431.85
#Mann= 6 ,-1 , 0
       0     .05       0 8436.37      .1       0 8823.08    .045       0
 9048.47      .1       0 9106.64     .05       0 11217.9     .07       0
#XS Ineff= 6 ,-1
    1652    3938     358    4727    7382     358    7568    8533     366
    9327    9668     366    9792    9975     357    9975   11732     370
Permanent Ineff=
       F       F       F       F       F       F
Bank Sta=8823.08,9048.47
XS Rating Curve= 0 ,0
Exp/Cntr=0.5,0.3

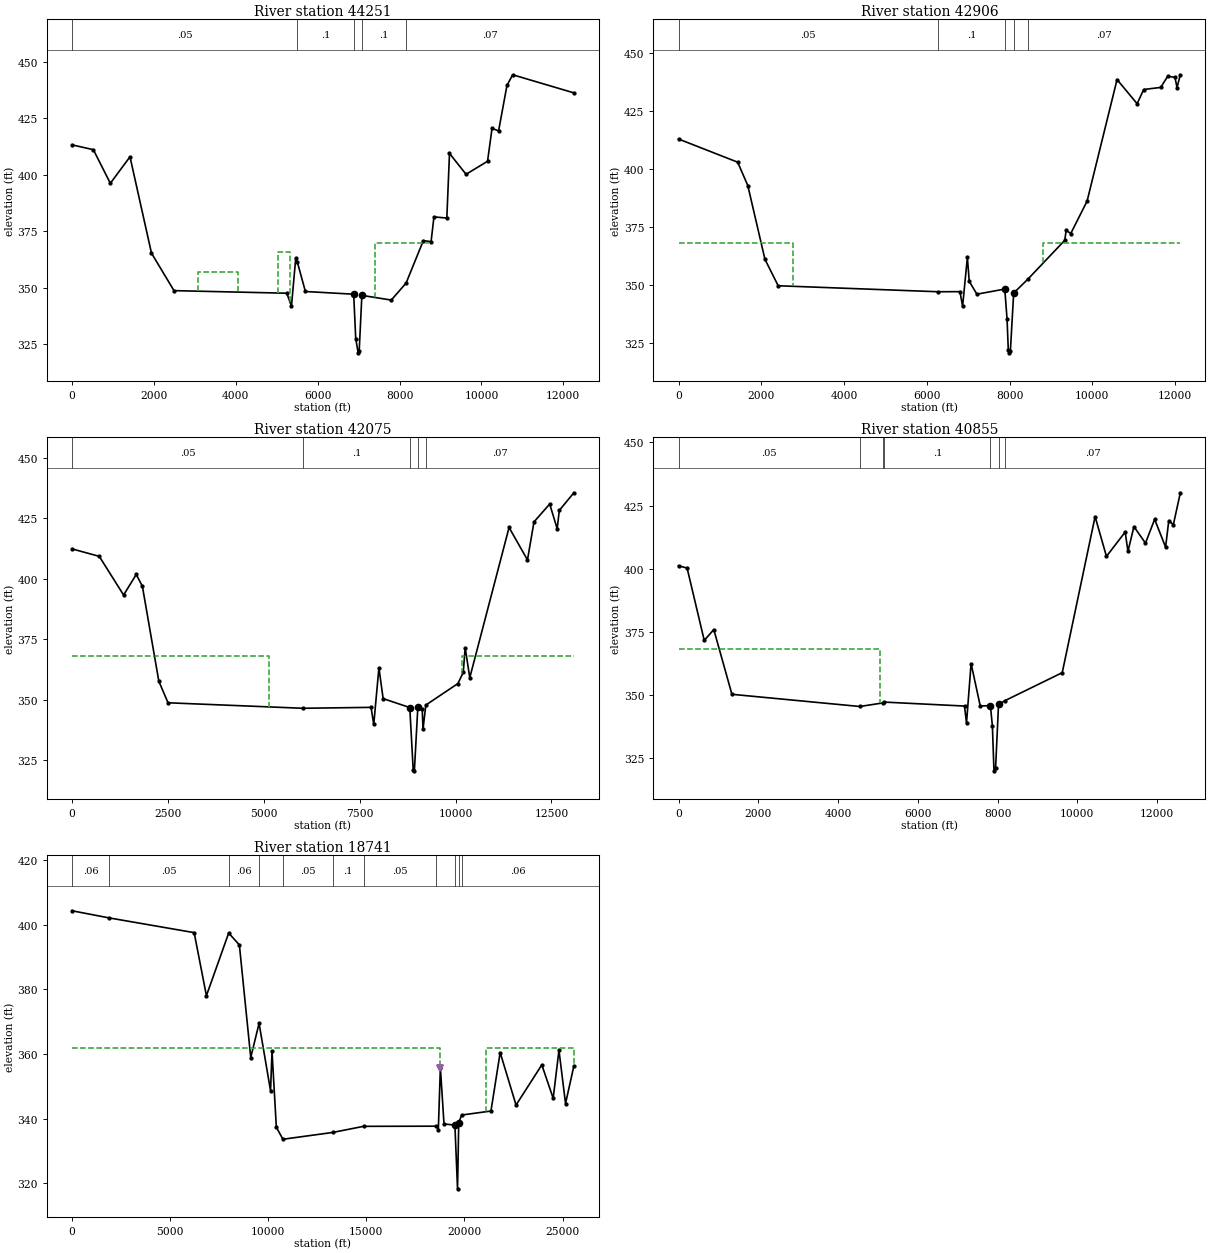
Type RM Length L Ch R = 1 ,44251   ,1282.65,1345.57,1145.65
BEGIN DESCRIPTION:
ROB IFA station 7410: flow expansion due to Kaufman 5 West levee upstream
END DESCRIPTION:
XS GIS Cut Line= 5
2594046.035702056909571.283878982588856.799689476905154.18346123
2588587.650949556905231.111456982587301.419270056904220.50422622
2584722.787944396901813.02249265
#Sta/Elev= 30
       0  413.19  519.97  411.06  934.95  396.19 1414.92  407.91 1939.89   365.3
 2489.86  348.72 5244.72  347.58 5359.71   341.9  5464.7  363.24  5501.6  361.48
 5699.69  348.34  6879.6  347.14 6929.58  327.44 6989.57  321.21 7014.56  322.15
 7079.55  346.63 7797.73  344.54 8160.12  352.07 8580.72  370.83 8770.32  370.38
 8840.28  381.34 9155.09  380.82 9220.05  409.42 9624.81  400.1810149.49  405.93
10259.43   420.510419.33  419.3510624.21  439.4910764.12  444.1912258.23  436.19
#Mann= 5 ,-1 , 0
       0     .05       0  5501.6      .1       0  6879.6    .045       0
 7079.55      .1       0 8160.12     .07       0
#XS Ineff= 3 ,-1
    3071    4054     357    5037    5335     366    7410    8722     370
Permanent Ineff=
       F       F       F
Bank Sta=6879.6,7079.55
XS Rating Curve= 0 ,0
Exp/Cntr=0.3,0.1

Type RM Length L Ch R = 1 ,42906   ,907.64,831.04,782.67
BEGIN DESCRIPTION:
LOB IFA station 2758: flow contraction due to Kaufman MUD1 levee downstream
ROB IFA station 8821: flow expansion due to Kaufman 5 West levee upstream
END DESCRIPTION:
XS GIS Cut Line= 3
2594297.772075226909371.631391142593845.622388976907306.79825048
2585514.888722396901747.91862023
#Sta/Elev= 30
       0  412.86 1429.16  402.89 1674.02  392.84 2088.78  361.07 2408.61  349.69
  6275.2  347.11 6801.43  347.15  6866.4  340.89 6981.34  361.89 7026.32  351.62
 7211.23  346.06  7885.9  348.27 7940.87  335.31 7970.86  321.87 7995.85  320.81
 8020.83   321.5 8100.79  346.56 8448.57  352.61 9335.21  369.26  9370.2  373.59
 9480.15  372.16 9874.96  386.1110599.62  438.46 11084.4  428.0711244.32  434.18
11654.13  435.0811824.05  439.8611998.97  439.4312048.95  435.0212128.91  440.52
#Mann= 5 ,-1 , 0
       0     .05       0  6275.2      .1       0  7885.9    .045       0
 8100.79      .1       0 8448.57     .07       0
#XS Ineff= 2 , 0
       0    2758     368    8821       0     368
Permanent Ineff=
       F       F
Bank Sta=7885.9,8100.79
XS Rating Curve= 0 ,0
Exp/Cntr=0.3,0.1

Type RM Length L Ch R = 1 ,42075   ,1066.9,1219.97,1124.41
BEGIN DESCRIPTION:
LOB IFA station 5124: flow contraction due to Kaufman MUD1 levee downstream
ROB IFA station 10178: flow expansion due to Kaufman 5 West levee upstream
END DESCRIPTION:
XS GIS Cut Line= 4
2594558.188549136909284.82579048 2594527.03572436906218.12949607
2592143.249809476904619.118914562585655.947823466901617.71021923
#Sta/Elev= 30
       0  412.37  709.27  409.29 1343.62   393.3 1673.28  401.79 1833.12  396.96
 2262.68  357.62 2502.44  348.72 6018.52  346.45 7796.83  346.83 7866.81  339.75
 8001.77  363.17 8111.75  350.45 8806.54  346.75 8896.52  320.78 8926.51  320.57
 9016.48  346.92 9131.45  345.99 9151.44  337.76 9224.91  347.7810061.18  356.67
10201.14  361.3110251.12  371.4910371.09   359.111395.79  421.2411875.65  407.82
 12045.6  423.5412455.48  430.9412650.42   420.712705.41  428.29 13085.3  435.59
#Mann= 5 ,-1 , 0
       0     .05       0 6018.52      .1       0 8806.54    .045       0
 9016.48      .1       0 9224.91     .07       0
#XS Ineff= 2 , 0
       0    5124     368   10178       0     368
Permanent Ineff=
       F       F
Bank Sta=8806.54,9016.48
XS Rating Curve= 0 ,0
Exp/Cntr=0.3,0.1

Type RM Length L Ch R = 1 ,40855   ,1237.08,1134.33,1039.8
BEGIN DESCRIPTION:
LOB IFA station 5045: flow contraction due to Kaufman MUD1 levee downstream
END DESCRIPTION:
XS GIS Cut Line= 5
2595299.352093066908122.994780812594743.397824396905789.94596922
2590440.123622556902663.953205482590079.021982556902366.42296064
2585786.156224476901400.69621757
#Sta/Elev= 30
       0  401.15  214.85  400.23  644.56  371.57   884.4  375.85 1339.09   350.2
 4547.89  345.37 5137.78  346.82 5162.77  347.11 7172.37  345.55 7222.36   338.8
 7337.34  362.39  7567.3  345.55 7821.79  345.74 7871.57  337.61 7911.39  319.87
 7951.21  320.82 8025.87   346.2 8185.15  347.67 9623.49  358.7810447.53  420.63
10732.21  404.8611201.66  414.5111271.58  406.8511421.41  416.6611711.07  410.11
11940.81  419.5612215.49  408.5212295.39  419.0212410.26  417.4412585.06  430.07
#Mann= 7 ,-1 , 0
       0     .05       0 4547.89      .1       0 5137.78     .05       0
 5162.77      .1       0 7821.79    .045       0 8025.87      .1       0
 8185.15     .07       0
#XS Ineff= 2 , 0
       0    5045     368               0
Permanent Ineff=
       F       F
Bank Sta=7821.79,8025.87
XS Rating Curve= 0 ,0
Exp/Cntr=0.3,0.1

Type RM Length L Ch R = 1 ,18741   ,1655.65,1742.82,1950.26
BEGIN DESCRIPTION:
LOB - Kaufman MUD1
ROB IFA station 211097: flow expansion due to natural high ground upstream
END DESCRIPTION:
XS GIS Cut Line= 5
2610763.852660066878378.988652142600975.607472816878665.28499556
2590955.961501646881722.923565312587971.051132896882582.00747706
 2585804.89962536882984.95319347
#Sta/Elev= 30
       0  404.36 1899.51  402.14 6223.41  397.59 6848.26  378.06 7982.98  397.46
 8527.83  393.79 9107.67  358.91 9532.54   369.510117.34  348.6210192.31   360.8
10412.23  337.3310747.09  333.59 13291.1   335.714855.49  337.5918569.04  337.64
   18669  336.5118773.96  355.8118958.89  338.3419513.67  337.9619648.62  318.23
19708.59  338.5719853.54  341.09 21352.1  342.3321821.55  360.46 22630.6  344.18
23944.29  356.6324523.83  346.29 24818.6  361.1525153.34  344.6625578.01  356.27
#Mann= 11 ,-1 , 0
       0     .06       0 1899.51     .05       0 7982.98     .06       0
 9532.54      .1       010747.09     .05       0 13291.1      .1       0
14855.49     .05       018569.04      .1       019513.67    .045       0
19708.59      .1       019853.54     .06       0
Levee=-1,18773.96,355.81,0,,,,
#XS Ineff= 2 ,-1
        18773.96     362 21097.425578.01     362
Permanent Ineff=
       F       F
Bank Sta=19513.67,19708.59
XS Rating Curve= 0 ,0
Exp/Cntr=0.3,0.1