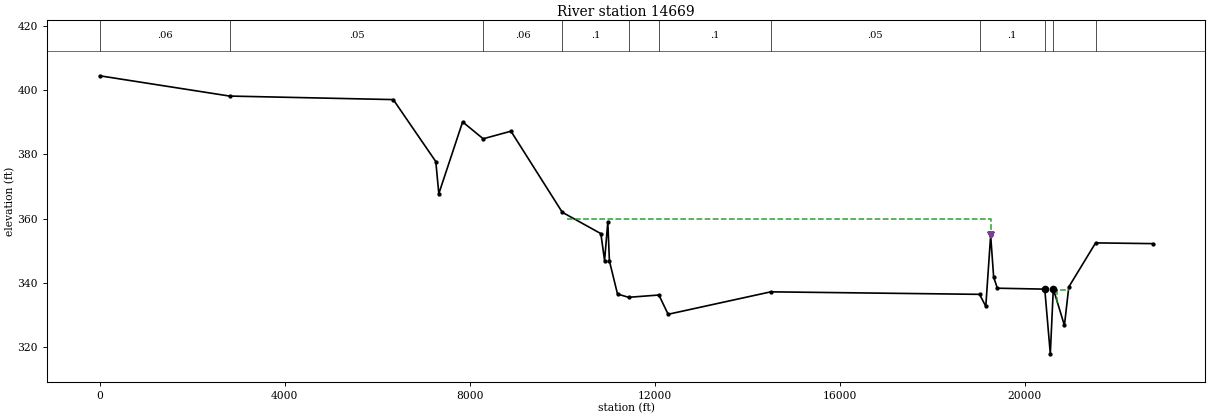
HEC-RAS study EF_FEMA.prj: East_Fork_FEMA

--- EF_FEMA.g02 (geometry) --- (continued)

Type RM Length L Ch R = 1 ,14669   ,1925.16,2040.36,2071.02
BEGIN DESCRIPTION:
LOB - Kaufman MUD1
END DESCRIPTION:
XS GIS Cut Line= 4
2610583.787731476877234.965021572602891.72535972 6877436.8990009
2589111.343471726878033.687505482587959.75128672 6877462.1194229
#Sta/Elev= 30
       0  404.48  2809.9  398.17 6349.68  397.07 7269.61  377.78  7334.6  367.79
 7849.56  390.13  8294.5  384.88 8894.38  387.2410004.17  362.02   10839  355.37
10918.99  346.9810988.97  358.9411023.97  346.8511198.93  336.5711438.88  335.56
12093.76  336.2712293.72  330.2814513.28  337.2619027.92  336.4819162.92  332.74
19267.92  354.8319332.92  341.8319412.92  338.3920437.92   338.120557.92  317.97
20622.92  338.1920862.92  326.8120957.92  338.7921537.74  352.4922773.38  352.26
#Mann= 11 ,-1 , 0
       0     .06       0  2809.9     .05       0  8294.5     .06       0
10004.17      .1       011438.88     .05       012093.76      .1       0
14513.28     .05       019027.92      .1       020437.92    .045       0
20622.92      .1       021537.74     .06       0
Levee=-1,19267.92,354.83,0,,,,
#XS Ineff= 2 ,-1
   1011519267.92     36020712.92 20952.5  337.85
Permanent Ineff=
       F       F
Bank Sta=20437.92,20622.92
XS Rating Curve= 0 ,0
Exp/Cntr=0.3,0.1

--- EF_FEMA.g03 (geometry) ---

Geom Title=EastFork_NV_Kauf_5_West
Program Version=5.06
BEGIN GEOM DESCRIPTION:
Scenario I
END GEOM DESCRIPTION:

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
River Reach=East Fork       ,1

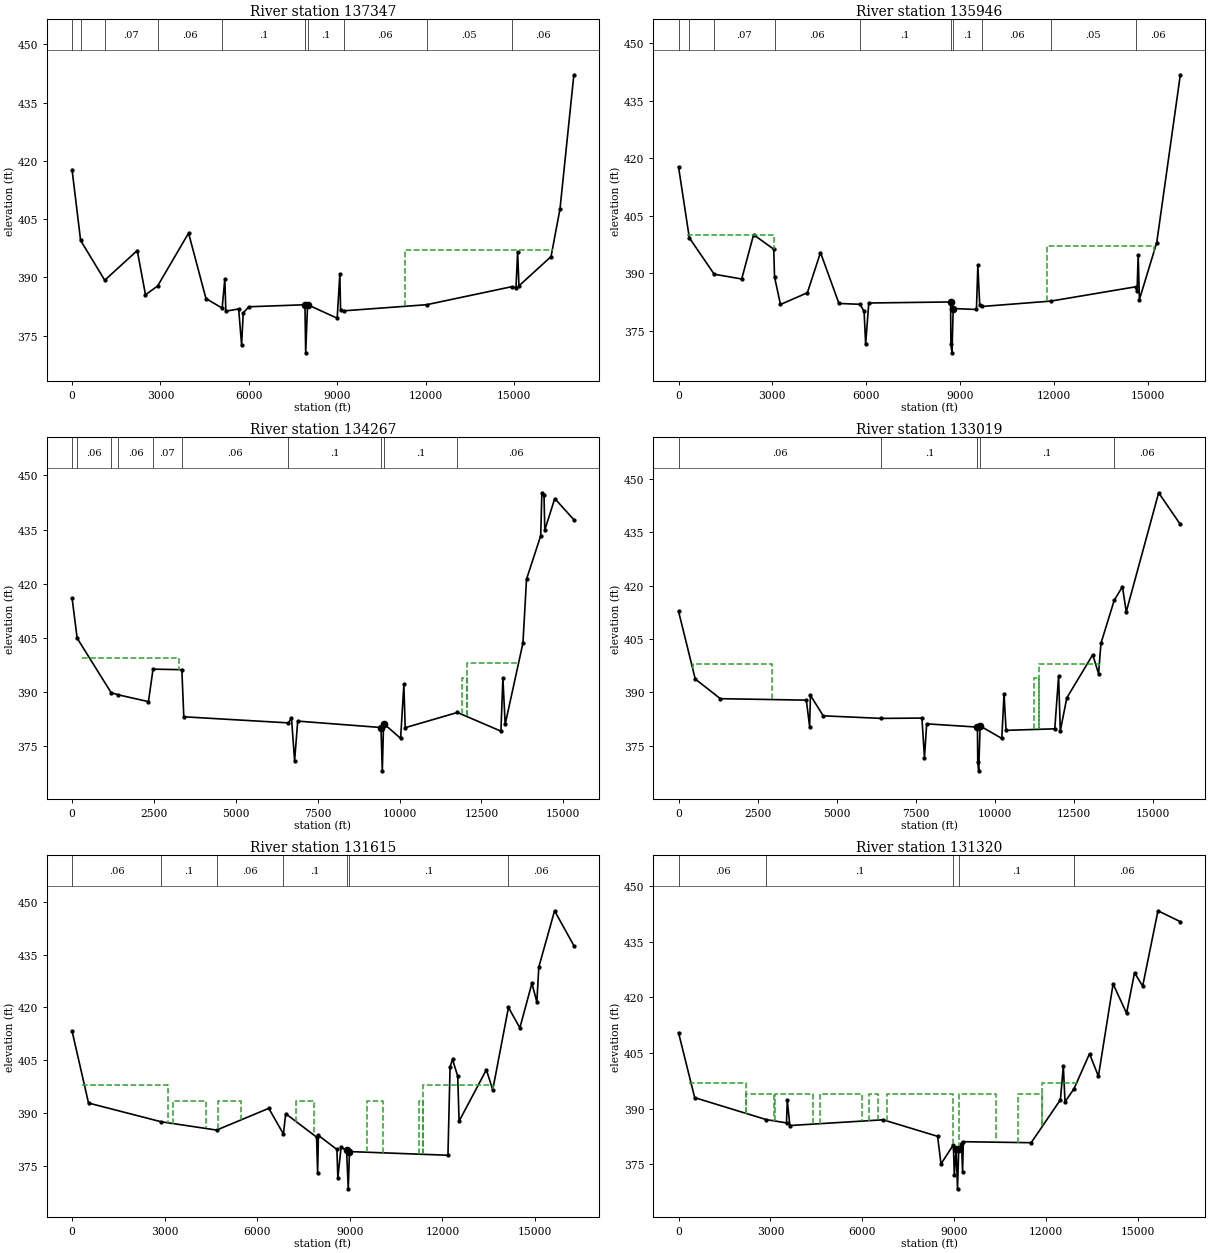
Type RM Length L Ch R = 1 ,137347  ,1140.97,1400.58,978.45
BEGIN DESCRIPTION:
LOB IFA station 3953.68: flow contraction due to natural high ground
END DESCRIPTION:
XS GIS Cut Line= 5
2588787.69779356 6964514.75043542587225.197637726964556.41701873
2585029.793892066965464.120911972573906.166861136968072.27514447
2572454.730787636967259.87585065
#Sta/Elev= 30
       0  417.72  289.64  399.51 1108.62  389.24 2211.87   396.9 2491.35   385.5
  2900.6  387.74 3953.68  401.38 4543.44  384.52 5093.21  382.07 5183.18  389.58
 5218.16  381.28 5652.98  381.84 5752.94  372.55 5807.92  380.84 6002.84  382.41
 7902.06  382.93 7927.05  370.54 7992.02  382.94 8996.63  379.46 9086.59  390.92
 9111.58  381.48 9211.54  381.3612030.44  382.9414919.31  387.5815064.25  387.34
15119.23  396.5615164.22   387.816253.27  395.3416557.95  407.6617027.45  442.18
#Mann= 10 ,-1 , 0
       0     .07       0  289.64     .06       0 1108.62     .07       0
  2900.6     .06       0 5093.21      .1       0 7902.06    .045       0
 7992.02      .1       0 9211.54     .06       012030.44     .05       0
14919.31     .06       0
#XS Ineff= 2 ,-1
     235 3953.68  401.38 11285.9   16316     397
Permanent Ineff=
       F       F
Bank Sta=7902.06,7992.02
XS Rating Curve= 0 ,0
Exp/Cntr=0.3,0.1

Type RM Length L Ch R = 1 ,135946  ,940.19,1679.57,1522.42
BEGIN DESCRIPTION:
LOB IFA station 4539.01: flow contraction due to natural high ground
END DESCRIPTION:
XS GIS Cut Line= 6
2588792.906116476964431.417268722584150.093551736964534.61555314
2580302.000198056965452.483468062580109.291593976965663.42103831
2574802.434097476966908.357196732573353.168295226966005.53551157
#Sta/Elev= 30
       0  417.71  344.92  399.25 1139.74  389.77 2019.54  388.52 2399.46  400.06
 3044.33  396.28 3069.32  389.04 3259.28  381.88  4119.1  384.93 4539.01  395.41
  5128.5  382.15 5797.82  381.93 5932.68  380.11 5982.63  371.58 6082.53  382.27
 8698.51  382.54 8708.36   371.5 8742.84  369.29 8782.25  380.83 9525.19  380.58
 9570.15  392.06 9630.11  381.72 9715.04  381.3711908.33  382.7714611.02  386.48
14660.95  385.3914695.89  394.8314735.83  383.18   15290  398.0216043.86   441.7
#Mann= 10 ,-1 , 0
       0     .07       0  344.92     .06       0 1139.74     .07       0
 3069.32     .06       0 5797.82      .1       0 8698.51    .045       0
 8782.25      .1       0 9715.04     .06       011908.33     .05       0
14611.02     .06       0
#XS Ineff= 3 ,-1
     280 3044.33     400 3044.33 4539.01  395.41 11795.9   15196     397
Permanent Ineff=
       F       F       F
Bank Sta=8698.51,8782.25
XS Rating Curve= 0 ,0
Exp/Cntr=0.3,0.1

Type RM Length L Ch R = 1 ,134267  ,945.86,1247.61,984.8
BEGIN DESCRIPTION:
LOB IFA station 3271.67: flow contraction due to natural high ground
END DESCRIPTION:
XS GIS Cut Line= 6
2588765.04134281 6964353.29209692587657.48942405 6964353.2920969
2585886.656023476963587.667315812579703.193652886964540.00497806
2576021.786645646964703.762524562573752.039544726964430.88282098
#Sta/Elev= 30
       0  416.04  154.66  404.91 1192.52  389.82 1402.44  389.24 2332.08  387.33
 2472.03  396.33 3351.63  396.18 3411.59  383.14 6604.72  381.45 6699.67  382.82
 6794.61  370.95 6889.55  381.94 9432.35  380.17 9472.12  368.17  9511.9  381.27
10031.17  377.1710131.13   392.110171.11  380.1211765.49  384.33 13094.6  379.16
13154.33  393.8813224.02  381.0613766.57  403.5613876.08  421.2414309.42  433.28
14344.31  445.1714409.11  444.6914434.03  434.8614738.08  443.5815321.25  437.71
#Mann= 10 ,-1 , 0
       0     .07       0  154.66     .06       0 1192.52     .07       0
 1402.44     .06       0 2472.03     .07       0 3351.63     .06       0
 6604.72      .1       0 9432.35    .045       0  9511.9      .1       0
11765.49     .06       0
#XS Ineff= 3 ,-1
     296 3271.67   399.5 11907.712051.15     39412051.15   13675     398
Permanent Ineff=
       F       F       F
Bank Sta=9432.35,9511.9
XS Rating Curve= 0 ,0
Exp/Cntr=0.3,0.1

Type RM Length L Ch R = 1 ,133019  ,1384.23,1404.04,669.16
XS GIS Cut Line= 6
2588754.190642716964308.587461892587669.034348476964243.83037356
2585644.468515726962879.449572152577308.228298476963605.97731856
2577133.749316726963332.53987332 2573698.65415286964403.53904365
#Sta/Elev= 30
       0  412.81  528.58  393.76 1321.74  388.24 4037.95  387.83 4142.85  380.42
 4167.82   389.2 4572.66  383.42 6407.22   382.7 7691.92  382.79  7771.9  371.67
 7841.88  381.17 9446.45  380.25 9456.44  370.33 9486.43  367.96 9531.42  380.58
10216.23  377.0610286.21  389.6410351.19  379.3411890.76  379.77 12010.6  394.56
12065.49  379.23 12270.1  388.4513089.62  400.5913274.52  395.2613349.47  403.79
13769.23   415.914029.07  419.72   14149  412.64 15173.4  446.11   15858  437.22
#Mann= 5 ,-1 , 0
       0     .06       0 6407.22      .1       0 9446.45    .045       0
 9531.42      .1       013769.23     .06       0
#XS Ineff= 3 ,-1
     454    2945     398 11247.311390.75     39411390.75   13291     398
Permanent Ineff=
       F       F       F
Bank Sta=9446.45,9531.42
XS Rating Curve= 0 ,0
Exp/Cntr=0.3,0.1

Type RM Length L Ch R = 1 ,131615  ,369.03,295,387.25
XS GIS Cut Line= 6
 2588747.15948886964284.194794152587668.760726976964143.37617815
2584852.372658976962150.103589892582383.203056636961929.92128748
2577347.612734146963234.825829892573662.195892396964391.82023506
#Sta/Elev= 30
       0  413.26  533.43   392.8 2888.33  387.47 4683.03  385.11 6372.96   391.3
  6846.4     384 6921.16  389.77 7920.21  383.12 7955.18   372.8 7980.17   383.6
  8579.8   379.6 8609.78  371.55 8714.72   380.2 8893.24  379.32 8947.46   368.4
 8986.89     37912176.84  377.9512245.58  403.1412324.14  405.2112492.83  400.45
 12537.8  387.6513422.28  402.2713627.16  396.5214136.86  419.9914506.64  414.18
14896.42  426.8615056.32  421.5615121.28  431.5215630.99  447.4816255.62  437.57
#Mann= 7 ,-1 , 0
       0     .06       0 2888.33      .1       0 4683.03     .06       0
  6846.4      .1       0 8893.24    .045       0 8986.89      .1       0
14136.86     .06       0
#XS Ineff= 7 ,-1
     306  3102.4     398  3278.5  4337.6   393.5  4728.8    5473   393.5
  7256.4  7839.6   393.5  9555.7 10058.1   393.5   1123111374.45   393.5
11374.45   13635     398
Permanent Ineff=
       F       F       F       F       F       F       F
Bank Sta=8893.24,8986.89
XS Rating Curve= 0 ,0
Exp/Cntr=0.5,0.3

Type RM Length L Ch R = 1 ,131320  ,172.92,142.52,224.66
BEGIN DESCRIPTION:
US Bridge
END DESCRIPTION:
XS GIS Cut Line= 6
2588737.414429566964257.794584482587680.556963226964114.56554022
2584666.667977886961956.290001142583241.320762986961464.97044572
2582687.501332556961497.956600232573617.924983556964386.61191215
#Sta/Elev= 30
       0  410.48  526.75  392.94 2864.51  387.01 3524.75  386.12 3549.73  392.26
 3634.65  385.41 6678.04  386.96 8457.71  382.49 8567.68  375.03 8972.61   380.2
  9002.6  372.04 9062.59  379.12 9107.58  368.31 9148.43  379.19 9237.55  380.64
 9272.55   372.9 9297.54  381.0411512.11  380.7712466.92  392.36 12561.9  401.53
12616.89  391.7912911.93  395.3713416.74  404.7913706.68  398.7314186.59  423.64
 14626.5  415.7314886.45  426.68 15151.4  423.05 15651.3  443.4116381.16  440.47
#Mann= 5 ,-1 , 0
       0     .06       0 2864.51      .1       0 8972.61    .045       0
 9148.43      .1       012911.93     .06       0
#XS Ineff= 9 ,-1
     350    2215     397    2215    3121     394    3163    4396     394
    4630    6005     394 6209.61    6503     394 6792.79    8960     394
    9165   10375     394   11085   11880     394   11880   13035     397
Permanent Ineff=
       F       F       F       F       F       F       F       F       F
Bank Sta=9062.59,9148.43
XS Rating Curve= 0 ,0
Exp/Cntr=0.5,0.3

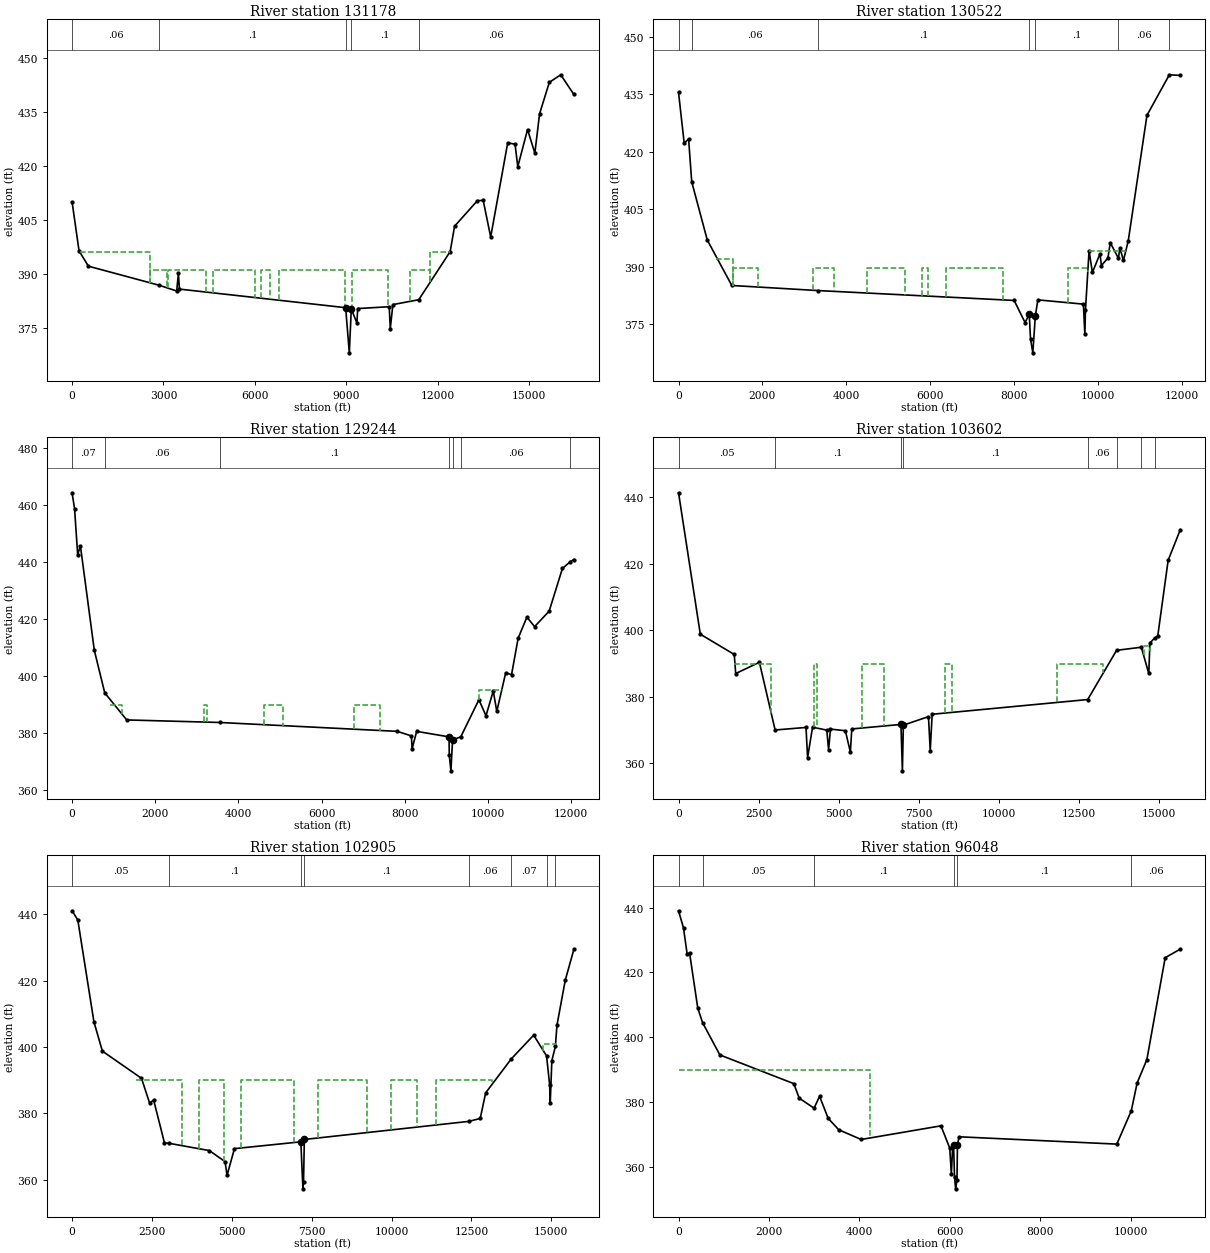
Type RM Length L Ch R = 1 ,131178  ,422.59,655.81,1080.74
BEGIN DESCRIPTION:
DS Bridge
END DESCRIPTION:
XS GIS Cut Line= 6
2588751.538417066964138.107815982587631.747021476963951.91002564
2584272.805904726961633.116434892583239.819781726961368.35974656
2582661.477762556961371.614661312573552.820783056964356.23008314
#Sta/Elev= 30
       0  410.02  228.84  396.38  537.27  392.11 2858.58  386.81 3433.69  385.21
  3488.6  390.14 3523.55  385.74 8977.57  380.57 9097.55  368.01 9162.53  380.19
  9347.5  376.33 9372.49  380.3310407.29  380.8410442.28  374.7810527.27  381.43
11375.92  382.78 12406.9  396.1712551.87  403.2313301.73  410.3513491.69   410.4
13736.64  400.2414296.53  426.4614536.48  426.0214626.47  419.81 14946.4  430.12
15186.36  423.5615341.33  434.5215661.26  443.2516036.19  445.3616466.12  439.89
#Mann= 5 ,-1 , 0
       0     .06       0 2858.58      .1       0 8977.57    .045       0
 9162.53      .1       011375.92     .06       0
#XS Ineff= 9 ,-1
     250    2570     396    2570    3120     391    3156    4397     391
    4630    6005     391 6205.54    6500     391    6790    8970     391
    9170   10375     391   11100   11760     391   11760   12400     396
Permanent Ineff=
       F       F       F       F       F       F       F       F       F
Bank Sta=8977.57,9162.53
XS Rating Curve= 0 ,0
Exp/Cntr=0.5,0.3

Type RM Length L Ch R = 1 ,130522  ,825.93,1278.14,964.51
XS GIS Cut Line= 4
2588948.37726222 6960912.01551492584693.881178056961031.34434448
2582688.672918146961070.406602312577053.341669146961888.04440273
#Sta/Elev= 30
       0  435.45  134.88  422.19  239.78  423.32  314.15  412.16  684.38  396.99
 1268.86  385.14 3316.13  383.82  7996.6  381.24 8256.57  375.48 8356.56  377.63
 8386.56  371.21 8441.55  367.59 8501.54  377.22 8561.53  381.39  9646.4  380.28
 9681.39  372.43 9696.39  378.83 9781.38  394.15 9861.37  388.5310041.35  393.38
10076.34  390.3310231.32  392.3210286.32  396.2910480.97  392.2410516.29  394.91
10601.28  391.6510716.26  396.8311161.21  429.4811694.34  440.0411956.11  439.87
#Mann= 7 ,-1 , 0
       0     .07       0  314.15     .06       0 3316.13      .1       0
 8356.56    .045       0 8501.54      .1       010480.97     .06       0
11694.34     .05       0
#XS Ineff= 8 ,-1
     890    1300     392    1300    1887  389.75    3199    3704  389.75
 4487.91  5401.7  389.75 5803.14 5954.81  389.75 6370.56 7740.43  389.75
 9288.19    9751  389.75 9781.38   10656  394.15
Permanent Ineff=
       F       F       F       F       F       F       F       F
Bank Sta=8356.56,8501.54
XS Rating Curve= 0 ,0
Exp/Cntr=0.3,0.1

Type RM Length L Ch R = 1 ,129244  ,922.95,1040.29,819.79
XS GIS Cut Line= 4
2588788.655140716959898.126794652579823.828582216960512.30896522
2579563.252331726960609.753324152576761.67492963 6960679.7108614
#Sta/Elev= 30
       0  464.15   59.97   458.6  134.94  442.42  199.91  445.61  534.75  408.98
  786.12  394.05 1314.39  384.59  3547.4   383.7  7821.4  380.59 8161.24  378.98
 8176.23  374.44 8286.19  380.58  9065.4  378.66 9070.37  372.34 9110.11  366.76
 9149.85  377.56 9347.56  378.69 9783.65  391.66  9953.5  386.0510128.34  394.73
10213.27   387.610428.07  401.1110567.95  400.4410727.81  413.2710937.62  420.59
11122.45  417.2711472.14  422.6811791.86  437.64 11985.7  440.0712066.61  440.76
#Mann= 7 ,-1 , 0
       0     .07       0  786.12     .06       0  3547.4      .1       0
  9065.4    .045       0 9149.85      .1       0 9347.56     .06       0
 11985.7     .05       0
#XS Ineff= 5 ,-1
     920    1198  389.75    3164    3250  389.75 4620.21 5073.91  389.75
 6790.06 7416.27  389.75 9783.65   10358     395
Permanent Ineff=
       F       F       F       F       F
Bank Sta=9065.4,9149.85
XS Rating Curve= 0 ,0
Exp/Cntr=0.3,0.1

Type RM Length L Ch R = 1 ,103602  ,491.43,697.56,687.23
XS GIS Cut Line= 4
2581338.134280646944053.508549562574691.724345136944075.03114431
2570026.547323816944689.645072562565718.344654146944640.17830798
#Sta/Elev= 30
       0  441.38  679.64  398.86 1739.07  392.76 1784.05  387.03 2523.65   390.4
 3014.39  370.05 3977.86  370.82 4027.83  361.74 4182.75   370.9 4627.52  370.01
 4682.49  364.11 4742.46  370.32 5207.23  369.83 5362.15  363.39 5407.13  370.37
 6941.21  371.72 6986.16  357.77 7016.13  371.51 7800.37  374.07 7855.31  363.88
 7915.26  374.7812769.61  379.2113671.06  394.01 14443.2  394.94 14675.6  387.04
14710.58  396.17 14855.6   397.714955.49   398.315280.36  421.0915660.21   430.3
#Mann= 8 ,-1 , 0
       0     .05       0 3014.39      .1       0 6941.21    .045       0
 7016.13      .1       012769.61     .06       013671.06     .07       0
 14443.2      .1       0 14855.6     .06       0
#XS Ineff= 6 ,-1
    1730    2900     390 4213.59  4331.1     390 5717.27 6426.55     390
 8328.54 8538.55     39011818.01   13255     390   14511   14702   395.2
Permanent Ineff=
       F       F       F       F       F       F
Bank Sta=6941.21,7016.13
XS Rating Curve= 0 ,0
Exp/Cntr=0.5,0.3

Type RM Length L Ch R = 1 ,102905  ,527.41,553.15,508.18
BEGIN DESCRIPTION:
US Bridge
END DESCRIPTION:
XS GIS Cut Line= 6
 2581358.96757236943845.175304822578354.728502056943702.54665306
2574397.366338066943461.575350232573800.467925556943472.64192915
2568610.761769556944282.465440722565739.177945816944570.73389307
#Sta/Elev= 30
       0  441.09  179.86   438.3  684.46   407.6  949.25  398.78 2173.28  390.59
 2428.08  383.09 2552.98  384.05 2892.71  371.11 3038.95  370.99 4297.52   368.8
 4787.47  365.49 4852.46  361.37 5082.44  369.39 7161.31  371.44 7225.99  357.27
 7245.89  359.26 7270.76  372.1512416.83   377.612776.88  378.4812946.69   386.2
 13747.8  396.4314449.63   403.614853.04  397.3514948.95  388.7114968.92  383.26
15018.85  395.9415129.72  400.2115178.63  406.5615438.28  420.1415707.91  429.44
#Mann= 8 ,-1 , 0
       0     .05       0 3038.95      .1       0 7161.31    .045       0
 7270.76      .1       012416.83     .06       0 13747.8     .07       0
14853.04      .1       015129.72     .06       0
#XS Ineff= 7 ,-1
    2000    3447     390    3972    4752     390    5279    6934     390
    7698    9248     390    9976   10806     390   11395   13150     390
   14749   15140   400.9
Permanent Ineff=
       F       F       F       F       F       F       F
Bank Sta=7161.31,7270.76
XS Rating Curve= 0 ,0
Exp/Cntr=0.5,0.3

Type RM Length L Ch R = 1 ,96048   ,1090.05,1281.61,847.13
BEGIN DESCRIPTION:
LOB IFA station 4227: flow contraction due to natural high ground downstream
END DESCRIPTION:
XS GIS Cut Line= 4
2581233.967494226941900.731030972579112.051134396941810.50188072
 2575562.78231436940223.360698062570878.066946226938251.28951098
#Sta/Elev= 30
       0  439.01  109.94   433.7   189.9  425.69  244.87  425.94  424.77  409.05
   531.7   404.5   914.5  394.55 2548.61  385.71 2668.55  381.23 2997.16  378.14
 3118.31  381.82 3308.21  375.01 3543.09  371.48 4037.82  368.49 5801.96   372.7
 5996.86   365.8 6031.85  357.79 6061.83  366.49 6081.83  366.73 6101.82  356.97
 6126.81  353.27 6156.79  356.02 6166.79  366.72 6201.77  369.32 9690.34  367.06
10009.93   377.310140.16  385.9210355.08  393.1310759.92  424.5411094.79   427.2
#Mann= 6 ,-1 , 0
       0     .07       0   531.7     .05       0 2997.16      .1       0
 6081.83    .045       0 6166.79      .1       010009.93     .06       0
#XS Ineff= 2 , 0
       0    4227     390               0
Permanent Ineff=
       F       F
Bank Sta=6081.83,6166.79
XS Rating Curve= 0 ,0
Exp/Cntr=0.3,0.1

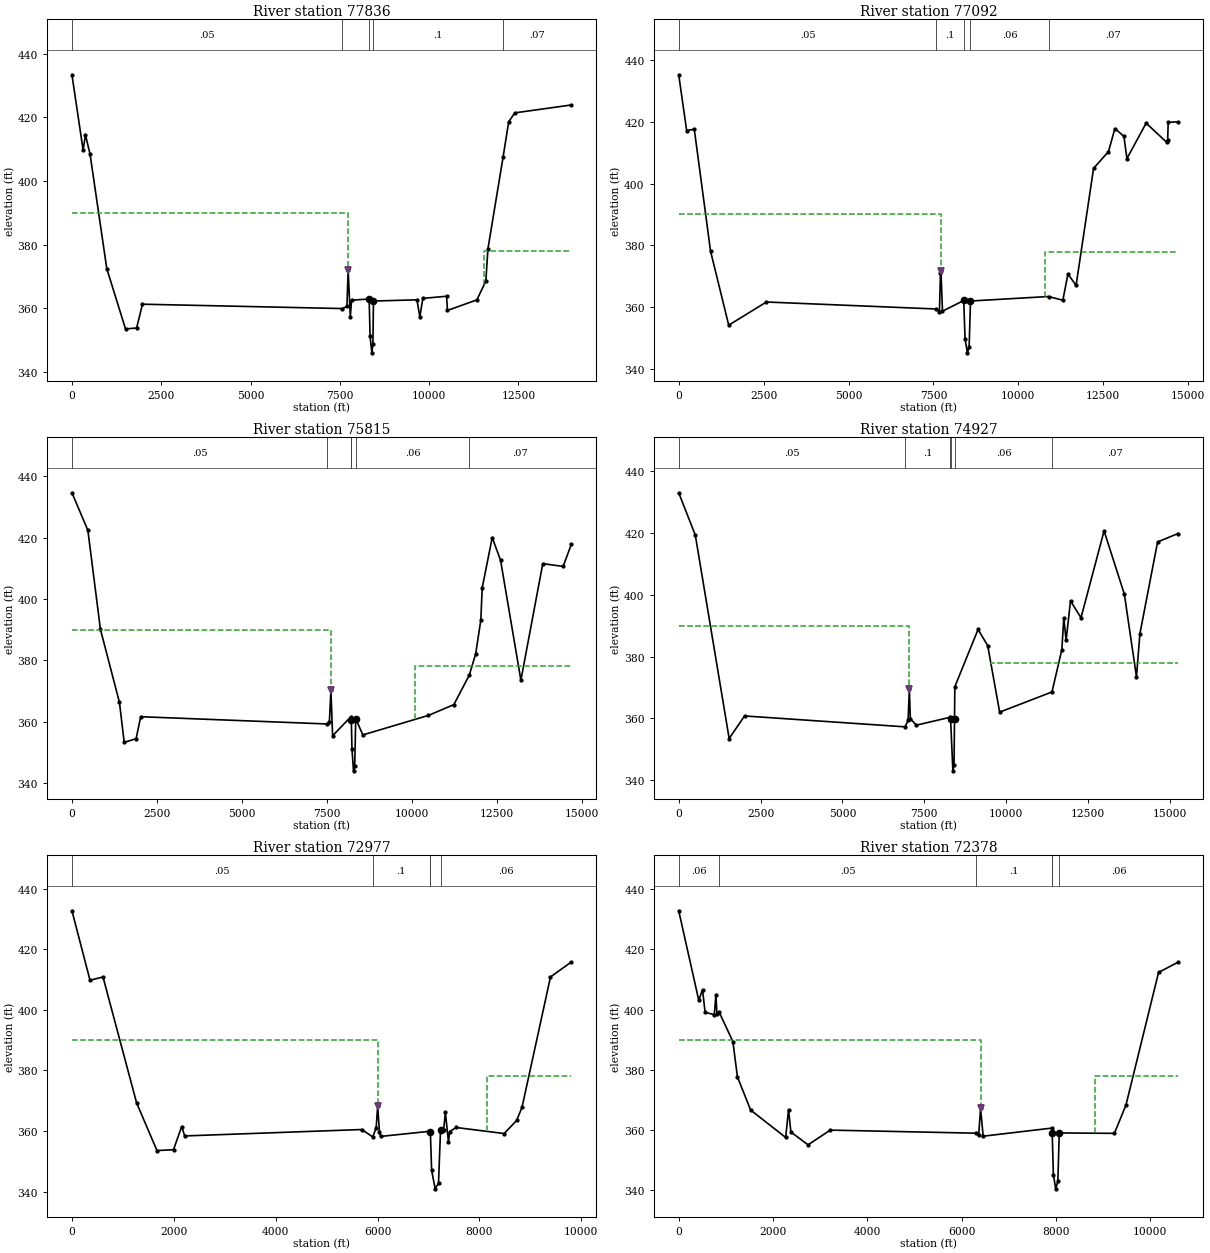
Type RM Length L Ch R = 1 ,77836   ,308.65,744.14,1041.53
BEGIN DESCRIPTION:
LOB - Kaufman LID15
ROB IFA station 11533: flow contraction due to natural high ground downstream
END DESCRIPTION:
XS GIS Cut Line= 6
2586329.106582146932169.480808482585634.53480855 6931884.9669418
2579288.946777976928005.586577222578886.169040226928005.58657722
2575587.846568636926473.917724562573967.606698896927143.31763248
#Sta/Elev= 30
       0  433.37  313.16  409.69  377.78   414.5  507.02  408.41  975.51  372.46
 1500.33  353.52 1810.23  353.82 1975.17  361.29 7574.07  359.92 7698.24  360.57
 7733.23  371.94 7793.21  357.31  7828.2  362.56 8321.11  362.92 8347.21   351.2
 8396.93  346.01 8426.77  348.88 8441.69  362.28 9659.82  362.67 9739.74  357.27
 9824.66  363.1210489.01  363.7910513.99  359.3211338.18  362.6611587.94  368.56
11647.88  378.7712069.63  407.4112227.31  418.5612397.11   421.413980.25  423.88
#Mann= 5 ,-1 , 0
       0     .05       0 7574.07      .1       0 8321.11    .045       0
 8441.69      .1       012069.63     .07       0
Levee=-1,7733.23,371.94,0,,,,
#XS Ineff= 2 , 0
       0 7733.23     390   11533       0     378
Permanent Ineff=
       F       F
Bank Sta=8321.11,8441.69
XS Rating Curve= 0 ,0
Exp/Cntr=0.3,0.1

Type RM Length L Ch R = 1 ,77092   ,943.98,1276.8,1378.67
BEGIN DESCRIPTION:
LOB - Kaufman LID15
ROB IFA station 10783.6: flow contraction due to natural high ground downstream
END DESCRIPTION:
XS GIS Cut Line= 6
2586356.884085646932096.56428765 2585642.12042336931804.04846847
2579052.835701636927186.142349972576169.750588556925433.65865023
2575728.610722816926049.683008732574162.919300396926785.24485782
#Sta/Elev= 30
       0  435.19  234.18  417.11   458.4  417.58  937.29  378.12 1472.24  354.16
 2582.12  361.66 7580.45   359.4 7676.66  358.53 7706.66  370.91 7721.65  371.63
 7766.65  358.69 8392.23  362.15 8431.57  349.61 8501.55  345.21 8551.53  347.26
 8591.52  361.9810888.78  363.4411310.65  362.23 11460.6  370.7311700.52  367.03
12215.35  404.9112653.98  410.3212843.39   417.813107.97  415.2913197.97  408.08
13762.92  419.5414362.87   413.414397.87  414.1914412.87  419.8214702.85  419.97
#Mann= 5 ,-1 , 0
       0     .05       0 7580.45      .1       0 8392.23    .045       0
 8591.52     .06       010888.78     .07       0
Levee=-1,7721.65,371.63,0,,,,
#XS Ineff= 2 , 0
       0 7721.65     390 10783.6       0     378
Permanent Ineff=
       F       F
Bank Sta=8392.23,8591.52
XS Rating Curve= 0 ,0
Exp/Cntr=0.3,0.1

Type RM Length L Ch R = 1 ,75815   ,500.58,888.74,1416.72
BEGIN DESCRIPTION:
LOB - Kaufman LID15
ROB IFA station 10102.8: flow contraction due to natural high ground downstream
END DESCRIPTION:
XS GIS Cut Line= 4
2586398.550997056932002.814147062585663.920248466931693.04376923
 2577151.74764036923830.090991232574868.214477726924105.12324956
#Sta/Elev= 30
       0  434.66   468.4   422.4  837.26  390.12 1397.17  366.24 1537.15  353.21
 1887.09  354.44 2022.07  361.59 7513.93  359.22 7571.07  359.76 7616.06  370.16
 7666.05  355.37 8204.61  361.59 8215.96  360.56 8235.95  350.92 8280.94  343.93
 8315.94  345.52 8345.93  360.93 8555.89  355.6510485.51  362.0211230.37  365.53
11683.22   375.111875.24  382.1612025.21  393.15 12065.2   403.612360.15  420.04
12604.67  412.6813203.38   373.513846.99  411.54 14445.7  410.6314685.19  417.79
#Mann= 6 ,-1 , 0
       0     .05       0 7513.93      .1       0 8204.61     .06       0
 8215.96    .045       0 8345.93     .06       011683.22     .07       0
Levee=-1,7616.06,370.16,0,,,,
#XS Ineff= 2 , 0
       0 7616.06     390 10102.8       0     378
Permanent Ineff=
       F       F
Bank Sta=8215.96,8345.93
XS Rating Curve= 0 ,0
Exp/Cntr=0.3,0.1

Type RM Length L Ch R = 1 ,74927   ,1396.59,1949.18,1764.62
BEGIN DESCRIPTION:
LOB - Kaufman LID15
ROB IFA station 9544: flow contraction due to natural high ground
END DESCRIPTION:
XS GIS Cut Line= 6
2586402.023102976931905.591900562585701.455606486931572.75004657
2580747.280147396926297.253379732580582.989137386925660.03910297
 2578264.4816353 6923421.52947242574955.020078396923964.06414847
#Sta/Elev= 30
       0  432.95  507.13  419.24  1540.3  353.48 2010.11  360.78 6912.73  357.26
 7003.05  359.31 7043.04  369.48 7073.02  359.85 7257.95   357.8 8294.15  360.37
 8301.79   359.7 8371.59  343.03 8406.49  345.02 8421.44  359.65 8431.41  370.24
 9140.39  388.75 9435.19  383.51 9799.93  362.0111397.72  368.5411698.64  382.23
 11758.6  392.5611828.55  385.2111963.48  397.9912283.36  392.5212988.08  420.63
13607.84  400.1513977.69  373.4414082.65  387.3914622.44  417.05 15247.2  419.77
#Mann= 6 ,-1 , 0
       0     .05       0 6912.73      .1       0 8294.15     .06       0
 8301.79    .045       0 8431.41     .06       011397.72     .07       0
Levee=-1,7043.04,369.48,0,,,,
#XS Ineff= 2 , 0
       0 7043.04     390    9544       0     378
Permanent Ineff=
       F       F
Bank Sta=8301.79,8421.44
XS Rating Curve= 0 ,0
Exp/Cntr=0.3,0.1

Type RM Length L Ch R = 1 ,72977   ,812.59,599.81,512.27
BEGIN DESCRIPTION:
LOB - Kaufman LID15
ROB IFA station 8157: flow expansion due to natural high ground upstream
END DESCRIPTION:
XS GIS Cut Line= 4
2586402.023102976931787.536362392585870.115374136931432.29625922
2581529.340919236923958.793161652581049.317272986923751.96614748
#Sta/Elev= 30
       0  432.67  354.79  409.74  609.64  410.83 1269.46  369.28 1669.35  353.53
 1994.26  353.82 2154.21  361.46  2214.2  358.36 5693.21  360.48  5906.6  358.02
 5973.14  360.96 6003.13  368.16 6038.12  359.81 6063.11   358.2 7023.05  359.89
 7037.98  359.62 7062.84  346.99 7132.82   340.9  7197.8   342.8 7237.79  360.36
 7297.77  360.17 7332.76  366.14 7392.75   356.5 7417.74  359.78 7542.71  361.15
 8487.46  359.15 8732.41  363.49 8837.38  367.79 9396.78  410.84 9804.96  415.76
#Mann= 5 ,-1 , 0
       0     .05       0  5906.6      .1       0 7023.05     .06       0
 7037.98    .045       0 7237.79     .06       0
Levee=-1,6003.13,368.16,0,,,,
#XS Ineff= 2 , 0
       0 6003.13     390    8157       0     378
Permanent Ineff=
       F       F
Bank Sta=7037.98,7237.79
XS Rating Curve= 0 ,0
Exp/Cntr=0.3,0.1

Type RM Length L Ch R = 1 ,72378   ,1353.88,1719.75,835.38
BEGIN DESCRIPTION:
LOB - Kaufman LID15
ROB IFA station 8827: flow expansion due to natural high ground upstream
END DESCRIPTION:
XS GIS Cut Line= 3
2587608.57679223 6931849.90631642582029.768724146924041.25625131
2581101.400502136923682.52140448
#Sta/Elev= 30
       0  432.87  424.86  403.08  504.83   406.6  559.81  399.06  754.75  398.29
  789.73  404.99  809.73  398.64  861.56  399.02 1149.61   389.3 1244.58   377.6
 1524.49  366.55 2269.24   357.4 2329.22  366.66  2379.2  359.21 2744.08  354.95
 3213.93  359.85 6295.71  358.83 6362.87  358.06 6402.85  367.13 6457.84  357.83
 7914.71  360.52 7922.34  358.84 7947.33  345.05 7997.32   340.3  8042.3  342.84
 8072.29  358.91 9241.86  358.77 9486.77  368.1710178.99  412.3610592.04  415.73
#Mann= 6 ,-1 , 0
       0     .06       0  861.56     .05       0 6295.71      .1       0
 7914.71     .06       0 7922.34    .045       0 8072.29     .06       0
Levee=-1,6402.85,367.13,0,,,,
#XS Ineff= 2 , 0
       0 6402.85     390    8827       0     378
Permanent Ineff=
       F       F
Bank Sta=7922.34,8072.29
XS Rating Curve= 0 ,0
Exp/Cntr=0.3,0.1

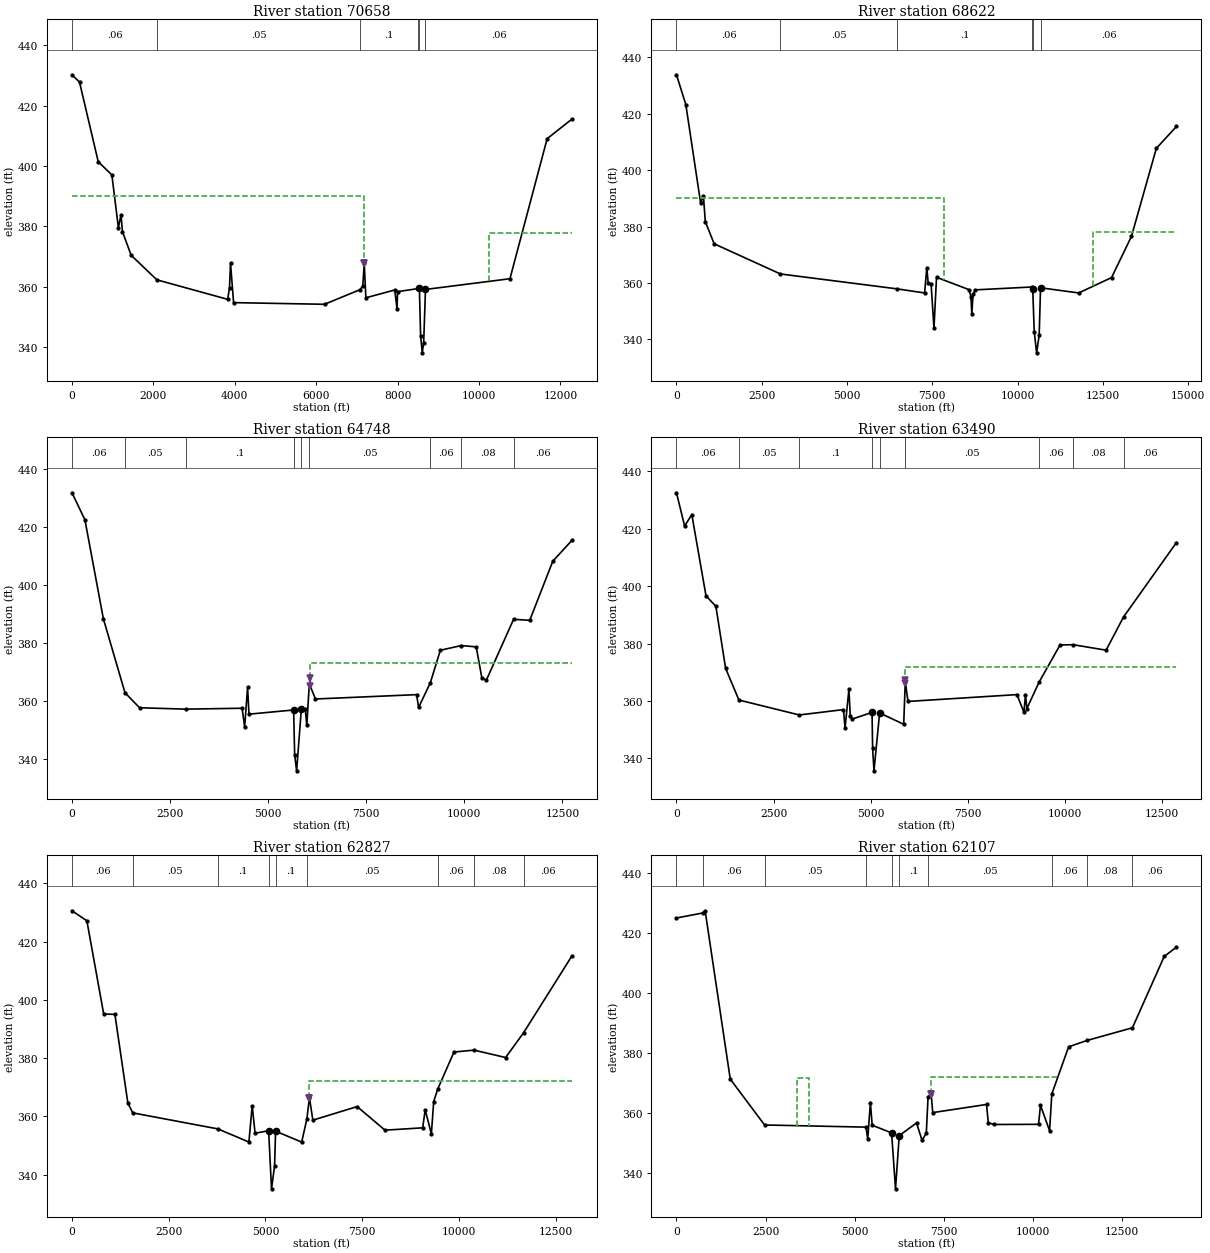
Type RM Length L Ch R = 1 ,70658   ,1805.09,2036.2,1079.67
BEGIN DESCRIPTION:
LOB - Kaufman LID15
ROB IFA station 10237: flow expansion due to natural high ground upstream
END DESCRIPTION:
XS GIS Cut Line= 4
2589837.743593726931875.947930982584361.332302476925329.66345139
2582274.02545346 6923822.32394642581118.761687896923613.07698956
#Sta/Elev= 30
       0  430.28     185  427.86  644.99  401.47  979.99  397.09 1139.99  379.62
 1204.99  383.88 1239.99  378.28 1454.99  370.44 2085.93  362.32 3824.95  355.86
 3869.95  359.66 3894.95  367.91 3969.95  354.77 6204.95  354.22 7078.08  359.08
 7144.95  360.34 7179.95  367.97 7219.95  356.37 7929.95  358.97 7984.95   352.8
 7999.95  358.42 8500.74  359.41 8534.86   359.5 8564.94  343.81 8604.93  338.13
 8639.93  341.39 8684.92  359.1410759.55  362.6911674.04  409.1112283.57  415.59
#Mann= 6 ,-1 , 0
       0     .06       0 2085.93     .05       0 7078.08      .1       0
 8500.74     .06       0 8534.86    .045       0 8684.92     .06       0
Levee=-1,7179.95,367.97,0,,,,
#XS Ineff= 2 , 0
       0 7179.95     390   10237       0     378
Permanent Ineff=
       F       F
Bank Sta=8534.86,8684.92
XS Rating Curve= 0 ,0
Exp/Cntr=0.3,0.1

Type RM Length L Ch R = 1 ,68622   ,1568.87,2031.43,1299.5
BEGIN DESCRIPTION:
LOB IFA station 7840: flow expansion due to Kaufman LID15 levee upstream
ROB IFA station 12204: flow expansion due to natural high ground upstream
END DESCRIPTION:
XS GIS Cut Line= 5
2594338.177506226928943.005306072590187.13757996 6928340.6866288
 2584791.22251886924484.626755642582458.030006726923599.30569164
2581127.442116726923508.91053122
#Sta/Elev= 30
       0  433.85  274.97  423.25  709.92  388.23  789.91     391   844.9  381.79
 1104.87   373.9 3047.63   363.2 6467.94  357.92 7273.27  356.47 7338.25  365.48
 7378.23  359.99  7463.2  359.71 7548.17  344.04 7623.14  362.03 8572.76  357.65
 8632.74  355.17 8657.73  348.83 8692.71  356.08 8762.69  357.5710429.59  358.59
10442.03  358.0410487.01  342.7910556.99  335.2310631.96  341.4910671.94   358.3
11790.18  356.4712753.49  361.9213337.47  376.5514066.76  407.7714656.18  415.51
#Mann= 6 ,-1 , 0
       0     .06       0 3047.63     .05       0 6467.94      .1       0
10429.59     .06       010442.03    .045       010671.94     .06       0
#XS Ineff= 2 , 0
       0    7840     390   12204       0     378
Permanent Ineff=
       F       F
Bank Sta=10442.03,10671.94
XS Rating Curve= 0 ,0
Exp/Cntr=0.3,0.1

Type RM Length L Ch R = 1 ,64748   ,1485.94,1258.36,388.27
BEGIN DESCRIPTION:
ROB - Kaufman LID10
END DESCRIPTION:
XS GIS Cut Line= 5
2593534.358247736925267.657997982590784.831594566924883.80279456
2587155.986490066923404.924190642582493.076524566923110.03665707
2581136.122545566923335.29932989
#Sta/Elev= 30
       0  431.73  329.55  422.42   798.9  388.36 1350.37  362.81 1722.64  357.62
 2900.35  357.14 4335.63  357.45  4400.6  350.99 4475.58  364.62 4510.56  355.41
 5648.22  356.85 5675.12  341.43  5725.1  335.87 5845.05  357.18 5945.01  357.03
    5985   351.6 6048.89  365.87 6204.92  360.64 8783.47  362.14 8833.44  357.71
 9133.62  366.27 9388.11  377.44 9922.23  379.0610302.58  378.6110447.49  367.78
10562.42  367.1911254.62  388.1211665.99  387.7612254.09  408.1412742.51  415.34
#Mann= 9 ,-1 , 0
       0     .06       0 1350.37     .05       0 2900.35      .1       0
 5648.22    .045       0 5845.05      .1       0 6048.89     .05       0
 9133.62     .06       0 9922.23     .08       011254.62     .06       0
Levee=0,,,-1,6069.97,367.73,,
#XS Ineff= 2 , 0
       0                 6069.97       0     373
Permanent Ineff=
       F       F
Bank Sta=5648.22,5845.05
XS Rating Curve= 0 ,0
Exp/Cntr=0.3,0.1

Type RM Length L Ch R = 1 ,63490   ,807.88,662.89,436.52
BEGIN DESCRIPTION:
ROB - Kaufman LID10
END DESCRIPTION:
XS GIS Cut Line= 5
2593933.663879566923913.491414982590188.802274816923115.88999181
2584451.816373476922944.351949072582493.237613476922968.49396114
2581170.844917066923196.41050006
#Sta/Elev= 30
       0  432.54  209.94  420.96  394.88  424.94  759.77  396.67  1014.7  392.98
 1264.62   371.4 1607.43  360.36 3161.18  355.16 4298.83  357.03 4338.82  350.59
 4438.81  364.14 4473.81  354.65 4518.81  353.72 5033.76  356.05 5048.76  343.51
 5083.75   335.7 5228.74  355.86 5848.68  351.92 5889.26  366.81 5958.67  359.87
 8763.46  362.25 8943.46   356.1 8983.46  362.23 9018.46  357.39 9337.22   366.7
 9873.28  379.5410209.89  379.6311057.58  377.7211507.35   389.312869.15  415.22
#Mann= 9 ,-1 , 0
       0     .06       0 1607.43     .05       0 3161.18      .1       0
 5033.76    .045       0 5228.74      .1       0 5889.26     .05       0
 9337.22     .06       010209.89     .08       011507.35     .06       0
Levee=0,,,-1,5893.68,367.28,,
#XS Ineff= 2 , 0
       0                 5893.68       0     372
Permanent Ineff=
       F       F
Bank Sta=5033.76,5228.74
XS Rating Curve= 0 ,0
Exp/Cntr=0.3,0.1

Type RM Length L Ch R = 1 ,62827   ,933.3,720.09,426.45
BEGIN DESCRIPTION:
ROB - Kaufman LID10
END DESCRIPTION:
XS GIS Cut Line= 4
2594063.871952476922793.699691312590222.728059966922330.61728415
2582458.835123236922834.600528152581205.567288556923074.88252789
#Sta/Elev= 30
       0  430.59   384.9  427.17  819.78  395.17  1109.7  395.02 1444.61   364.6
 1571.64  361.22 3769.35  355.73 4573.52  351.22 4658.47  363.65 4733.42  354.24
 5083.21  355.09 5158.16  335.15 5238.11  343.15  5263.1  354.94 5937.68   351.2
 6071.76   359.1 6137.56  366.42  6227.5  358.73  7371.8  363.38 8091.36  355.29
 9065.78  356.09 9130.75  362.29 9290.65  354.01 9350.62   365.1 9454.11  369.38
 9875.31  382.1110394.37  382.7611209.53  380.22   11675  388.7412925.27  415.13
#Mann= 9 ,-1 , 0
       0     .06       0 1571.64     .05       0 3769.35      .1       0
 5083.21    .045       0  5263.1      .1       0 6071.76     .05       0
 9454.11     .06       010394.37     .08       0   11675     .06       0
Levee=0,,,-1,6137.56,366.42,,
#XS Ineff= 2 , 0
       0                 6137.56       0     372
Permanent Ineff=
       F       F
Bank Sta=5083.21,5263.1
XS Rating Curve= 0 ,0
Exp/Cntr=0.3,0.1

Type RM Length L Ch R = 1 ,62107   ,347.84,334.05,325.77
BEGIN DESCRIPTION:
ROB - Kaufman LID10
END DESCRIPTION:
XS GIS Cut Line= 5
2595053.455275136921161.755120562590342.430904556921429.73555572
2584311.848149466922553.571234552582467.506693816922728.78577915
2581162.16448823 6922979.3964984
#Sta/Elev= 30
       0  424.87  732.47  426.52  804.77  427.27 1509.56  371.22 2473.35  355.93
 5318.47  355.21 5368.56  351.33 5443.56   363.4 5493.55  355.85 6038.49  353.29
 6148.48  334.66 6253.47  352.39 6738.42   356.6  6893.4  350.81 7013.39  353.24
 7062.29   365.3 7148.37  366.41 7193.37  360.05 8703.23  362.76 8753.22  356.64
 8923.21  356.0910163.13  356.1510218.12  362.48 10473.1  354.0210535.91  366.26
11007.88  381.9611525.04  384.0812799.03   388.313690.13  412.0514034.93  415.17
#Mann= 10 ,-1 , 0
       0     .05       0  732.47     .06       0 2473.35     .05       0
 5318.47      .1       0 6038.49    .045       0 6253.47      .1       0
 7062.29     .05       010535.91     .06       011525.04     .08       0
12799.03     .06       0
Levee=0,,,-1,7148.37,366.41,,
#XS Ineff= 2 ,-1
 3388.51 3718.61   371.5 7148.37   10713     372
Permanent Ineff=
       F       F
Bank Sta=6038.49,6253.47
XS Rating Curve= 0 ,0
Exp/Cntr=0.5,0.3