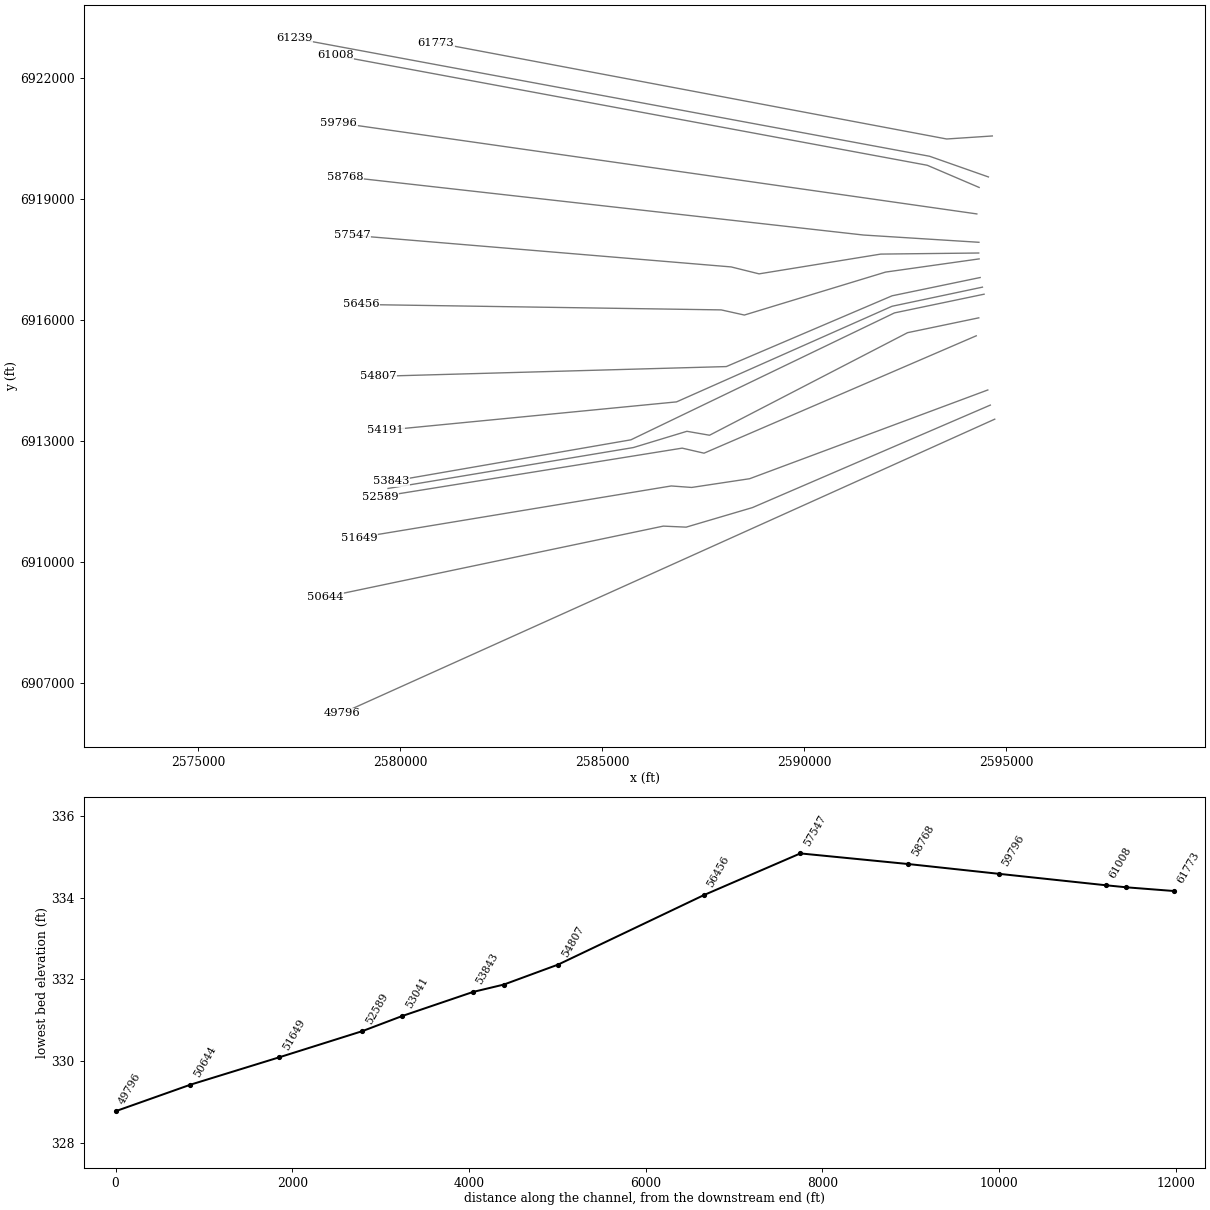
HEC-RAS study EF_FEMA.prj: East_Fork_FEMA

--- EF_FEMA.g03 (geometry) --- (continued)

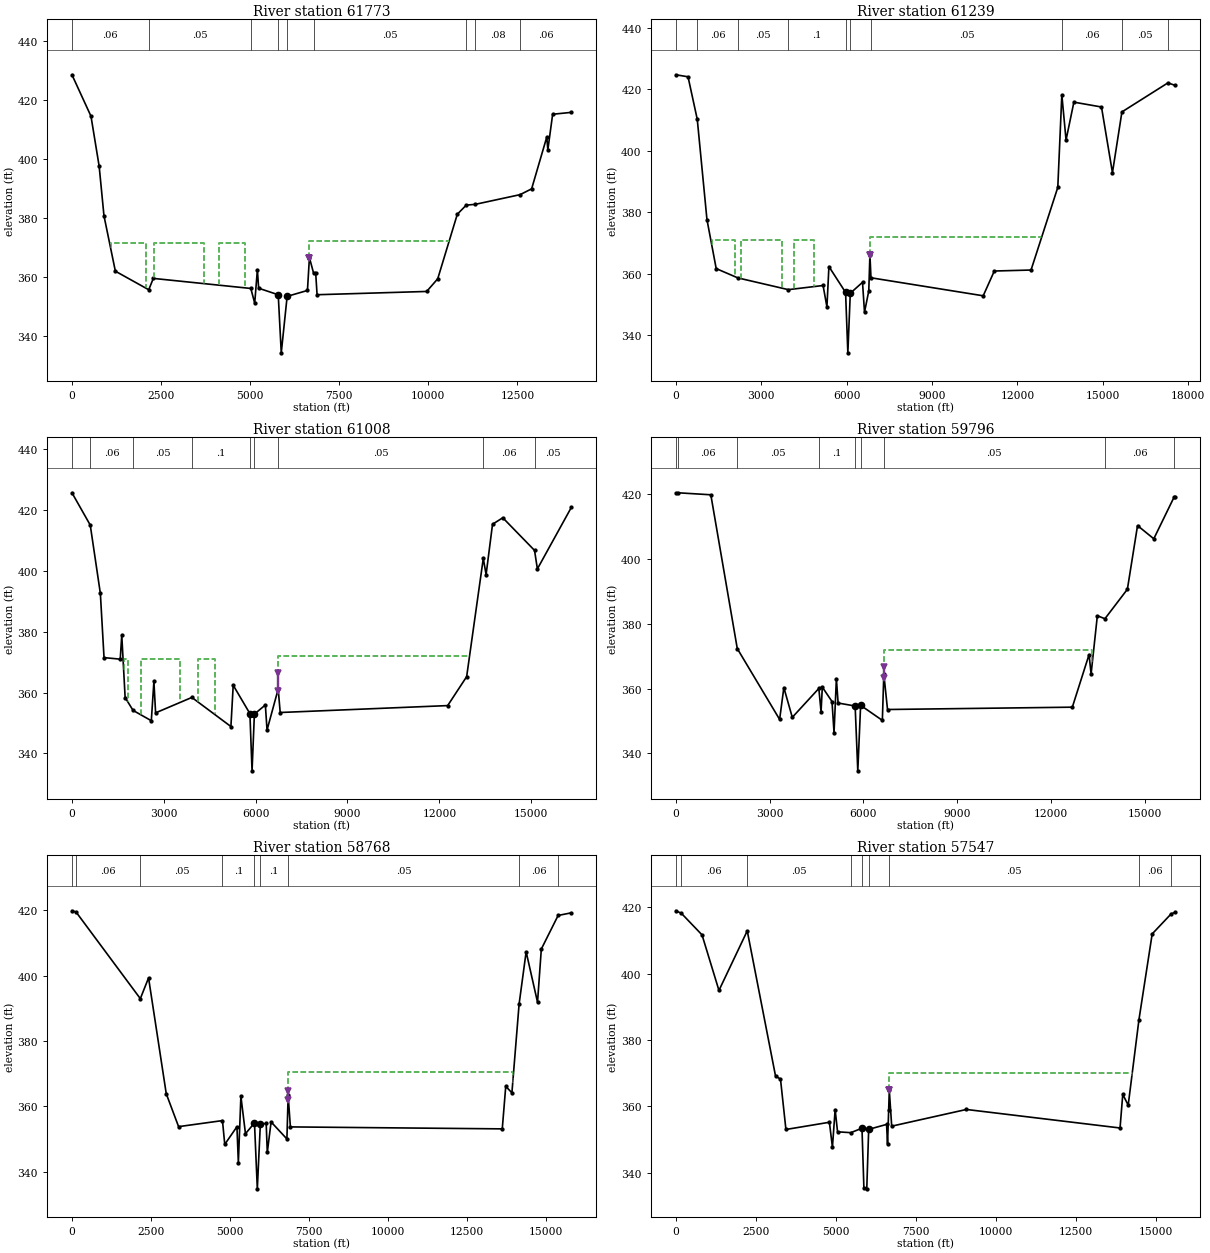
Type RM Length L Ch R = 1 ,61773   ,508.19,534.06,519.89
BEGIN DESCRIPTION:
US Bridge
ROB - Kaufman LID10
END DESCRIPTION:
XS GIS Cut Line= 3
2594662.83040021 6920562.79700092593532.223081386920487.75253156
2580875.706071636922875.23004006
#Sta/Elev= 30
       0  428.56   534.1  414.49  763.72  397.49  898.49  380.69 1218.09  361.88
 2154.83  355.58 2283.07  359.43  5018.7  356.02 5127.99  351.03 5202.99   362.4
 5237.99   356.1 5787.97  353.88 5872.96  334.16 6037.96  353.33 6607.94  355.34
 6662.93  366.49 6781.16  361.16 6837.93  361.41 6877.93  353.89 9952.87     355
10262.87  359.2910812.87  381.2211062.84   384.311319.55  384.5812573.11  387.86
12897.87  389.8313322.87  407.4113352.87  403.0813487.87  415.1614012.87   415.8
#Mann= 9 ,-1 , 0
       0     .06       0 2154.83     .05       0  5018.7      .1       0
 5787.97    .045       0 6037.96      .1       0 6781.16     .05       0
11062.84     .06       011319.55     .08       012573.11     .06       0
Levee=0,,,-1,6662.93,366.49,,
#XS Ineff= 4 ,-1
    1086    2065   371.5    2295    3715   371.5    4140    4860   371.5
 6662.93   10575     372
Permanent Ineff=
       F       F       F       F
Bank Sta=5787.97,6037.96
XS Rating Curve= 0 ,0
Exp/Cntr=0.5,0.3

Type RM Length L Ch R = 1 ,61239   ,231.81,230.66,231.9
BEGIN DESCRIPTION:
DS Bridge
ROB - Kaufman LID10
END DESCRIPTION:
XS GIS Cut Line= 3
2594565.608153726919547.172063652593109.176027226920059.67431948
2577378.631044816922982.72752848
#Sta/Elev= 30
       0  424.68  429.71  424.03  754.27  410.18 1094.27   377.6 1419.05  361.65
 2180.49  358.62 3954.08   354.8 5173.94  356.15 5308.94  349.16 5378.94   362.3
 5964.02  353.91 6043.79  334.25 6129.55  353.63 6558.94  357.19 6628.94  347.46
 6778.94   354.4 6818.94  366.23 6856.56  358.6610798.94   352.811188.94  360.86
12478.94  361.1813418.94  388.06   13561  418.1713708.94  403.4613983.94  415.78
14953.94   414.215338.94  392.8315671.59   412.617286.68  422.0417543.94  421.23
#Mann= 10 ,-1 , 0
       0     .07       0  754.27     .06       0 2180.49     .05       0
 3954.08      .1       0 5964.02    .045       0 6129.55      .1       0
 6856.56     .05       0   13561     .06       015671.59     .05       0
17286.68     .07       0
Levee=0,,,-1,6818.94,366.23,,
#XS Ineff= 4 ,-1
    1265    2065     371    2295    3715     371    4145    4860     371
 6818.94   12857     372
Permanent Ineff=
       F       F       F       F
Bank Sta=5964.02,6129.55
XS Rating Curve= 0 ,0
Exp/Cntr=0.5,0.3

Type RM Length L Ch R = 1 ,61008   ,1142.5,1211.73,1352.69
BEGIN DESCRIPTION:
ROB - Kaufman LID10
END DESCRIPTION:
XS GIS Cut Line= 3
2594336.441617316919286.755261642593052.01341188 6919836.3673514
2578387.745824476922559.55055331
#Sta/Elev= 30
       0  425.67   597.9  415.05  928.06  392.58 1047.81   371.5 1577.08     371
 1627.08  378.88 1737.08  358.39 1996.36  354.16 2592.07  350.77 2677.07  363.66
 2732.07  353.35 3916.25  358.42 5192.04  348.86 5267.04  362.42 5812.14  353.11
 5882.48   334.3 5958.82  352.94 6317.03  355.94 6372.03  347.71 6736.21  361.17
 6802.02  353.47   12272  355.74   12892  365.2513435.23  404.11   13527  398.79
   13737  415.33   14072  417.4615109.12  406.74   15202  400.65   16312  420.88
#Mann= 9 ,-1 , 0
       0     .07       0   597.9     .06       0 1996.36     .05       0
 3916.25      .1       0 5812.14    .045       0 5958.82      .1       0
 6736.21     .05       013435.23     .06       015109.12     .05       0
Levee=0,,,-1,6717.02,366.29,,
#XS Ineff= 4 ,-1
    1688 1828.11     371 2264.67 3529.53     371  4104.3 4662.68     371
 6717.02   13017     372
Permanent Ineff=
       F       F       F       F
Bank Sta=5812.14,5958.82
XS Rating Curve= 0 ,0
Exp/Cntr=0.3,0.1

Type RM Length L Ch R = 1 ,59796   ,966.46,1028.06,1097.97
BEGIN DESCRIPTION:
ROB - Kaufman LID10
END DESCRIPTION:
XS GIS Cut Line= 2
2594279.149737136918630.505261812578471.192179896920887.38263781
#Sta/Elev= 30
       0  420.43   63.08  420.49 1119.88  419.87 1965.58  372.35 3319.63  350.46
 3454.62  360.29 3724.59  351.11 4573.28  360.03 4644.49  352.85 4684.49  360.45
 4994.46     356 5059.45  346.36 5134.44  363.07 5189.44  355.53 5734.38  354.61
 5818.88  334.58 5909.37  354.82  6604.3  350.17 6651.09  364.47 6769.28  353.53
12678.61  354.2513213.55   370.513278.54  364.5113478.52  382.5113720.39  381.57
14438.41  390.6714763.37  410.3515283.31  406.28 15933.3  419.1815968.22  419.16
#Mann= 9 ,-1 , 0
       0     .07       0   63.08     .06       0 1965.58     .05       0
 4573.28      .1       0 5734.38    .045       0 5909.37      .1       0
 6651.09     .05       013720.39     .06       0 15933.3     .05       0
Levee=0,,,-1,6664.29,366.53,,
#XS Ineff= 2 ,-1
                         6664.29   13321     372
Permanent Ineff=
       F       F
Bank Sta=5734.38,5909.37
XS Rating Curve= 0 ,0
Exp/Cntr=0.3,0.1

Type RM Length L Ch R = 1 ,58768   ,995.35,1220.81,1240.8
BEGIN DESCRIPTION:
ROB - Kaufman LID10
END DESCRIPTION:
XS GIS Cut Line= 3
2594331.233294386917927.380355732591470.356470216918107.56076965
2578627.442195486919550.57724056
#Sta/Elev= 30
       0  419.81  129.38  419.44 2162.04  392.95 2422.08   399.3 2981.54  363.89
 3371.51  353.83 4758.75  355.68 4831.38  348.41 5216.35  353.81 5261.35   342.8
 5341.34  363.13 5486.33  351.67  5771.3  354.96  5860.8  334.82 5956.29  354.55
 6141.27   354.8 6176.27  345.96 6296.26  355.27 6796.21  350.07 6835.42  363.37
  6906.2  353.75 13605.3  353.1513715.28  366.1513910.25  364.1714137.73   391.3
14360.18  407.2714720.13  391.8614840.11  408.1115371.36  418.3815789.97  419.19
#Mann= 9 ,-1 , 0
       0     .07       0  129.38     .06       0 2162.04     .05       0
 4758.75      .1       0  5771.3    .045       0 5956.29      .1       0
 6835.42     .05       014137.73     .06       015371.36     .05       0
Levee=0,,,-1,6846.21,364.63,,
#XS Ineff= 1 ,-1
 6846.21   13936   370.5
Permanent Ineff=
       F
Bank Sta=5771.3,5956.29
XS Rating Curve= 0 ,0
Exp/Cntr=0.3,0.1

Type RM Length L Ch R = 1 ,57547   ,837.69,1091.62,1276.98
BEGIN DESCRIPTION:
ROB - Kaufman LID10
END DESCRIPTION:
XS GIS Cut Line= 5
2594326.024971476917661.755230812591898.227989816917634.89307982
2588885.705799646917144.938679142588193.448982066917317.00920114
2578809.733825646918100.92429997
#Sta/Elev= 30
       0  418.98  171.57  418.24  819.31  411.71 1348.86  394.95 2233.37  412.92
 3117.28  369.11 3272.13   368.2 3441.97  352.99 4800.67  355.17 4895.57  347.66
 4980.49  358.98 5055.42  352.29 5469.52  352.03 5819.22  353.37 5879.08  335.35
 5968.87  335.08 6028.73  353.03  6588.2  354.52 6618.19  348.63 6653.62  358.95
 6673.17  364.84 6748.15  353.99 9082.28  359.03 13885.4  353.4413970.37  363.58
 14140.3  360.33 14476.1  386.1214890.01     41215485.07  418.0715609.73  418.52
#Mann= 9 ,-1 , 0
       0     .07       0  171.57     .06       0 2233.37     .05       0
 5469.52      .1       0 5819.22    .045       0 6028.73      .1       0
 6653.62     .05       0 14476.1     .06       015485.07     .05       0
Levee=0,,,-1,6673.17,364.84,,
#XS Ineff= 1 ,-1
 6673.17   14256     370
Permanent Ineff=
       F
Bank Sta=5819.22,6028.73
XS Rating Curve= 0 ,0
Exp/Cntr=0.3,0.1

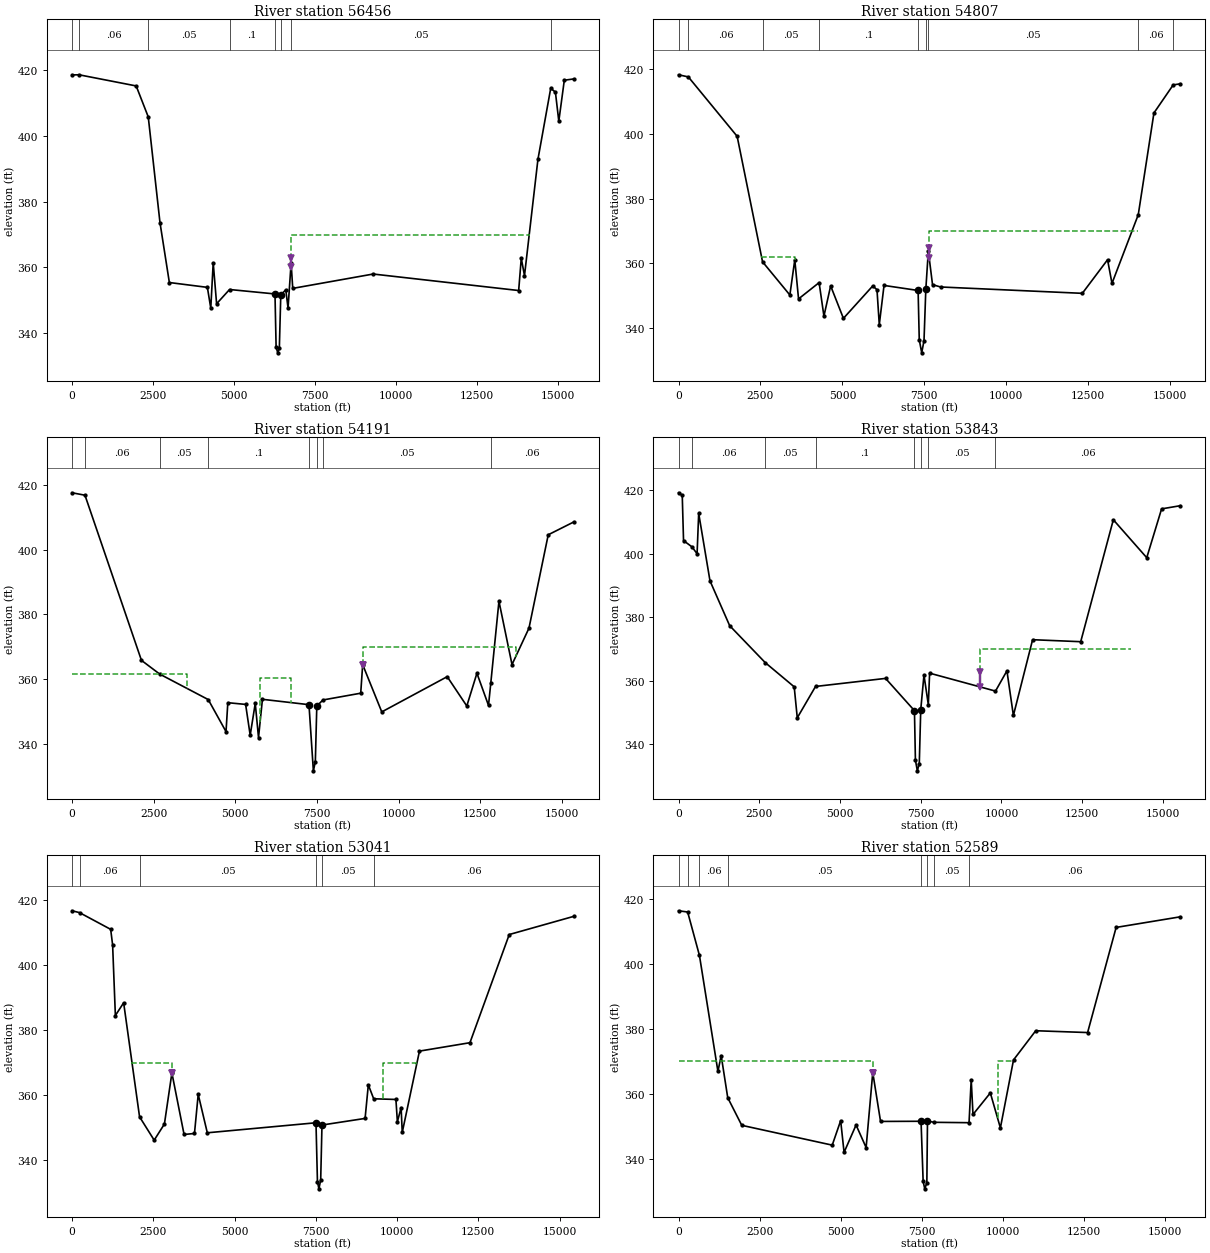
Type RM Length L Ch R = 1 ,56456   ,1050.99,1649.02,1533
BEGIN DESCRIPTION:
ROB - Kaufman LID10
END DESCRIPTION:
XS GIS Cut Line= 5
2594336.441617316917515.921861072592019.932142726917189.06621556
 2588521.1225393 6916124.10509092587948.01082464 6916251.7918434
2579038.787501386916385.50515865
#Sta/Elev= 30
       0  418.48  214.12  418.53 1979.53  415.14 2352.61  405.73 2714.17  373.65
 3003.95  355.42 4178.08  353.95    4283  347.63 4357.95  361.42 4462.87  348.97
 4862.76   353.3 6265.43  351.95 6300.26  335.86 6350.02  334.06 6399.78  335.47
 6444.57  351.62 6598.88  353.22 6668.84  347.66 6763.26  361.36 6813.76  353.64
 9297.36     35813789.86  352.9913869.82  362.7813969.76  357.5314384.53  392.83
14779.46  414.4414924.23  413.2515029.17  404.4415199.08  416.8815493.92  417.27
#Mann= 8 ,-1 , 0
       0     .07       0  214.12     .06       0 2352.61     .05       0
 4862.76      .1       0 6265.43    .045       0 6444.57      .1       0
 6763.26     .05       014779.46     .06       0
Levee=0,,,-1,6753.8,362.83,,
#XS Ineff= 1 ,-1
  6753.8   14146     370
Permanent Ineff=
       F
Bank Sta=6265.43,6444.57
XS Rating Curve= 0 ,0
Exp/Cntr=0.3,0.1

Type RM Length L Ch R = 1 ,54807   ,343.73,615.72,961.48
BEGIN DESCRIPTION:
ROB - Kaufman LID10
LOB IFA Station 3546.4: flow contraction due to natural high ground
END DESCRIPTION:
XS GIS Cut Line= 4
2594361.759808146917054.116354232592180.812398396916601.35708915
2588073.222844566914846.860926232579461.964476566914605.99132922
#Sta/Elev= 30
       0  418.24  299.19  417.58 1787.96  399.24 2563.43  360.47 3396.56  350.22
 3546.44  361.09 3661.36  349.02 4288.79  354.05 4435.77   343.7 4640.62  353.04
 5030.33  343.01 5924.66  353.02 6054.56  351.86 6124.51  341.07  6269.4  353.18
 7309.04  351.62 7344.04  336.42 7419.04  332.36 7489.03  336.14 7544.03  351.93
 7620.78  363.83 7749.02  353.42    7994   352.712318.99  350.7413088.99  361.11
13223.99  353.8114025.72  375.0214503.99  406.4515091.26  415.1115308.99  415.45
#Mann= 9 ,-1 , 0
       0     .07       0  299.19     .06       0 2563.43     .05       0
 4288.79      .1       0 7309.04    .045       0 7544.03      .1       0
 7620.78     .05       014025.72     .06       015091.26     .05       0
Levee=0,,,-1,7649.02,364.66,,
#XS Ineff= 2 ,-1
    2524  3546.4     362 7649.02   14009     370
Permanent Ineff=
       F       F
Bank Sta=7309.04,7544.03
XS Rating Curve= 0 ,0
Exp/Cntr=0.5,0.3

Type RM Length L Ch R = 1 ,54191   ,340.54,347.69,879.16
BEGIN DESCRIPTION:
ROB - Kaufman LID10
LOB IFA Station 3531.8: flow contraction due to natural high ground upstream
LOB IFA Station 5759-6715: flow contraction due to natural high ground downstream
END DESCRIPTION:
XS GIS Cut Line= 4
2594417.912911066916815.486582152592178.329463726916341.52821247
2586841.523864396913971.736364142579640.135051976913270.34767506
#Sta/Elev= 30
       0  417.47  394.86  416.72 2124.25  365.88 2684.15  361.65 4168.99  353.81
 4713.93  343.94 4768.92  352.85 5313.86  352.32 5453.85  342.83 5608.83  352.64
 5708.82  342.13 5828.81  353.89 7253.65  352.24 7388.64  331.87 7448.63  334.68
 7493.63  351.85 7683.61  353.69 8838.14  355.77 8898.11  364.57 9482.76  350.01
11486.59  360.8612086.24  351.8312396.06  361.9112750.85  352.0112820.81  358.88
13070.66  384.0813470.43  364.5913990.12   375.814579.78  404.5415364.32   408.5
#Mann= 8 ,-1 , 0
       0     .07       0  394.86     .06       0 2684.15     .05       0
 4168.99      .1       0 7253.65    .045       0 7493.63      .1       0
 7683.61     .05       012820.81     .06       0
Levee=0,,,-1,8898.11,364.57,,
#XS Ineff= 3 ,-1
       0  3531.8   361.6    5759    6715   360.5 8898.11   13579     370
Permanent Ineff=
       F       F       F
Bank Sta=7253.65,7493.63
XS Rating Curve= 0 ,0
Exp/Cntr=0.5,0.3

Type RM Length L Ch R = 1 ,53843   ,1413.54,802.88,201.58
BEGIN DESCRIPTION:
ROB - Kaufman LID10
END DESCRIPTION:
XS GIS Cut Line= 4
2594458.982054646916640.921970652592239.655128466916177.40550923
2585711.877173566913031.572233972579776.634450886912001.82462156
#Sta/Elev= 30
       0  419.28  114.86  418.49  154.81  404.22   417.3  402.23  574.29  400.08
  624.23   412.8   973.8  391.54 1583.05  377.42 2683.57  365.79 3581.54  358.15
 3676.49  348.39 4242.17  358.27 6410.11  360.81 7304.66  350.65 7334.65  335.05
 7394.62  331.69 7454.59     334 7499.57  350.95 7599.52  361.86 7734.38  352.55
 7774.43  362.46 9814.35  356.8110168.32  363.1910368.28  349.1310963.16     373
12452.87  372.3713462.67  410.7814497.47  398.8314957.38  414.2115537.27  415.21
#Mann= 8 ,-1 , 0
       0     .07       0   417.3     .06       0 2683.57     .05       0
 4242.17      .1       0 7304.66    .045       0 7499.57      .1       0
 7734.38     .05       0 9814.35     .06       0
Levee=0,,,-1,9348.54,362.89,,
#XS Ineff= 1 ,-1
 9348.54   14000     370
Permanent Ineff=
       F
Bank Sta=7304.66,7499.57
XS Rating Curve= 0 ,0
Exp/Cntr=0.8,0.6

Type RM Length L Ch R = 1 ,53041   ,887.56,451.48,215
BEGIN DESCRIPTION:
LOB - Kaufman 5 East
ROB IFA station 9582: flow expansion due to Kaufman LID10 levee upstream
END DESCRIPTION:
XS GIS Cut Line= 6
2594327.634876396916055.069795892592563.746015716915687.01442964
2587658.814880716913145.118266732587098.468232396913242.56984347
2585772.079480986912839.792105732579695.69038706 6911825.9030574
#Sta/Elev= 30
       0  416.78   229.6  416.21 1187.94  411.06 1247.84  406.25 1332.69  384.51
 1587.25  388.43 2076.85  353.29 2526.81   346.1 2841.78  351.07 3071.76  366.81
 3446.73  347.85  3766.7  348.16 3881.69  360.21 4161.66  348.37 7505.91  351.46
 7550.82  333.36 7595.72   331.1  7650.6  333.79 7690.52  350.76    9017   352.8
 9116.72  363.14 9281.27  358.85 9965.74  358.64 10010.7  351.7610125.61  356.14
10160.59   348.510690.17  373.5412243.96  376.1313453.01  409.4615441.46  415.07
#Mann= 6 ,-1 , 0
       0     .07       0   229.6     .06       0 2076.85     .05       0
 7505.91    .045       0 7690.52     .05       0 9281.27     .06       0
Levee=-1,3071.76,366.81,0,,,,
#XS Ineff= 2 ,-1
    1804 3071.76     370    9582   10585     370
Permanent Ineff=
       F       F
Bank Sta=7505.91,7690.52
XS Rating Curve= 0 ,0
Exp/Cntr=0.5,0.3

Type RM Length L Ch R = 1 ,52589   ,1237.78,939.78,994.4
BEGIN DESCRIPTION:
LOB - Kaufman 5 East
ROB IFA station 9838: flow expansion due to Kaufman LID10 levee upstream
END DESCRIPTION:
XS GIS Cut Line= 4
2594264.537561646915609.672064652587522.424733556912700.27696481
2586980.75816597 6912825.27704292579505.367276896911622.05044673
#Sta/Elev= 30
       0  416.45  281.37  416.07   644.9  402.67 1214.68  366.92 1314.65  371.83
 1516.82  358.83 1949.48  350.31 4738.75   344.2 4998.68  351.75 5103.65  341.97
 5473.54  350.41 5783.46  343.46  5988.4  366.58 6228.33  351.51 7477.03  351.56
 7541.55  333.01 7591.19  330.73 7655.71   332.6 7675.57  351.66 7872.82  351.24
 8956.65  351.12 9023.46  364.39 9078.43  353.65 9613.22   360.3 9923.09  349.52
10327.92  370.4711012.64  379.4712611.99  378.9113491.63  411.3215470.82  414.59
#Mann= 8 ,-1 , 0
       0     .07       0  281.37     .05       0   644.9     .06       0
 1516.82     .05       0 7477.03    .045       0 7675.57     .05       0
 7872.82     .05       0 8956.65     .06       0
Levee=-1,5988.4,366.58,0,,,,
#XS Ineff= 2 ,-1
       0  5988.4     370    9838   10320     370
Permanent Ineff=
       F       F
Bank Sta=7477.03,7675.57
XS Rating Curve= 0 ,0
Exp/Cntr=0.3,0.1

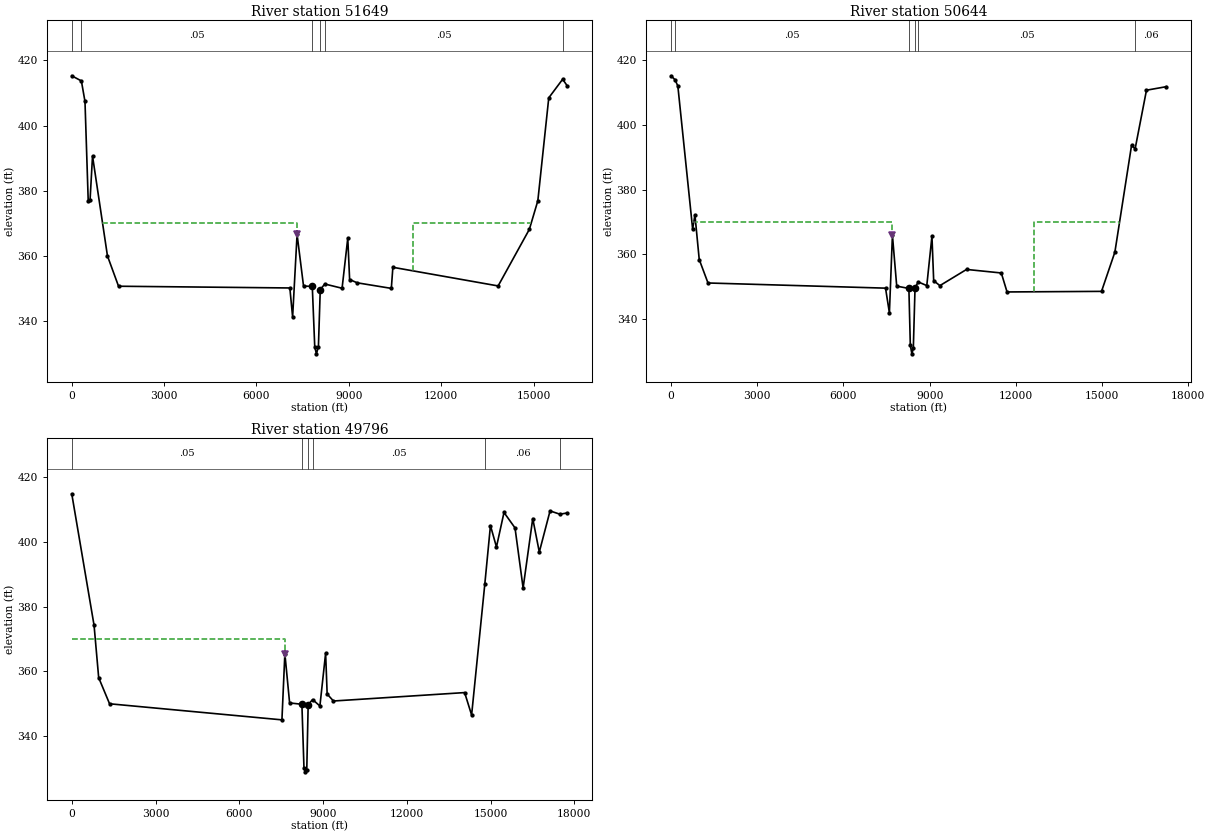
Type RM Length L Ch R = 1 ,51649   ,976.98,1004.9,1121.02
BEGIN DESCRIPTION:
LOB - Kaufman 5 East
ROB IFA station 11068: flow expansion due to Kaufman LID10 levee upstream
END DESCRIPTION:
XS GIS Cut Line= 5
2594550.648537966914266.963463982588652.855215486912067.51970014
2587215.985057736911850.876432642586709.924718146911887.77694939
2578983.345026976910609.60496506
#Sta/Elev= 30
       0  415.23  313.12  413.65  429.97  407.36  534.96  376.97  594.96  377.24
  674.95  390.66 1159.92  360.07 1519.89  350.79 7083.55  350.26 7173.43  341.38
 7318.25  366.65 7527.98  350.84 7812.37  350.74 7891.97  332.27 7946.69  330.09
 8011.36   332.3 8071.05  349.79 8218.76  351.47 8779.91  350.17 8964.83  365.51
 9024.81  352.85 9269.72  351.8410379.28  350.1310429.26  356.5913847.93  350.88
14862.53  368.2215137.42  376.9615492.28  408.4715943.32  414.1716087.05  412.22
#Mann= 6 ,-1 , 0
       0     .07       0  313.12     .05       0 7812.37    .045       0
 8071.05     .05       0 8218.76     .05       015943.32     .06       0
Levee=-1,7318.25,366.65,0,,,,
#XS Ineff= 2 ,-1
     975 7318.25     370   11068   14920     370
Permanent Ineff=
       F       F
Bank Sta=7812.37,8071.05
XS Rating Curve= 0 ,0
Exp/Cntr=0.3,0.1

Type RM Length L Ch R = 1 ,50644   ,692.75,848.13,1501.09
BEGIN DESCRIPTION:
LOB - Kaufman 5 East
ROB IFA station 12643: flow expansion due to Kaufman LID10 levee upstream
END DESCRIPTION:
XS GIS Cut Line= 5
2594613.148741056913891.96355781 2588721.42922536911351.62054139
2587079.716301386910866.943689232586513.192171986910892.49875623
2578149.030422646909137.24143998
#Sta/Elev= 30
       0  415.01  139.84  413.74  234.86  411.84  749.54  367.84  829.49  372.16
   979.4  358.44 1284.21  351.23 7464.13  349.64 7598.88  342.03 7703.68  365.95
  7853.4  350.26 8277.12  349.55 8326.87  332.07 8381.59  329.42 8431.34  331.13
 8491.03  349.78 8603.38  351.56 8899.91  350.42 9079.84  365.62 9139.82  351.96
 9354.73  350.4110284.37   355.4 11493.9  354.3111693.82  348.4714982.53  348.65
15447.35  360.7416027.12  393.5916151.85  392.5216546.92  410.5717241.65  411.66
#Mann= 6 ,-1 , 0
       0     .07       0  139.84     .05       0 8277.12    .045       0
 8491.03     .05       0 8603.38     .05       016151.85     .06       0
Levee=-1,7703.74,365.94,0,,,,
#XS Ineff= 2 ,-1
     726 7703.74     370   12643   15601     370
Permanent Ineff=
       F       F
Bank Sta=8277.12,8491.03
XS Rating Curve= 0 ,0
Exp/Cntr=0.3,0.1

Type RM Length L Ch R = 1 ,49796   ,1452.91,1476.31,1787.04
BEGIN DESCRIPTION:
LOB - Kaufman 5 East
END DESCRIPTION:
XS GIS Cut Line= 2
 2594722.52352236913543.005266232578550.505997646906250.95653014
#Sta/Elev= 30
       0  414.94  799.77  374.16  964.73  357.95 1354.62  349.86 7527.86  344.88
 7632.83  365.42 7802.79  350.12 8242.66  349.71 8317.64  329.84 8362.63  328.77
 8417.62  329.43  8467.6   349.6 8625.57  351.16  8887.5  349.18 9092.44  365.52
 9147.43  352.88 9372.37  350.7214071.18  353.3314321.12  346.38 14795.5   387.1
14995.95  405.0815210.89  398.4515480.82  409.1515875.72  404.3616165.65  385.74
16510.54  407.2616745.45  396.88 17130.3  409.6317483.55  408.6117740.06  408.99
#Mann= 6 ,-1 , 0
       0     .05       0 8242.66    .045       0  8467.6     .05       0
 8625.57     .05       0 14795.5     .06       017483.55     .07       0
Levee=-1,7632.84,365.42,0,,,,
#XS Ineff= 2 , 0
       0 7632.84     370   14463       0     357
Permanent Ineff=
       F       F
Bank Sta=8242.66,8467.6
XS Rating Curve= 0 ,0
Exp/Cntr=0.3,0.1