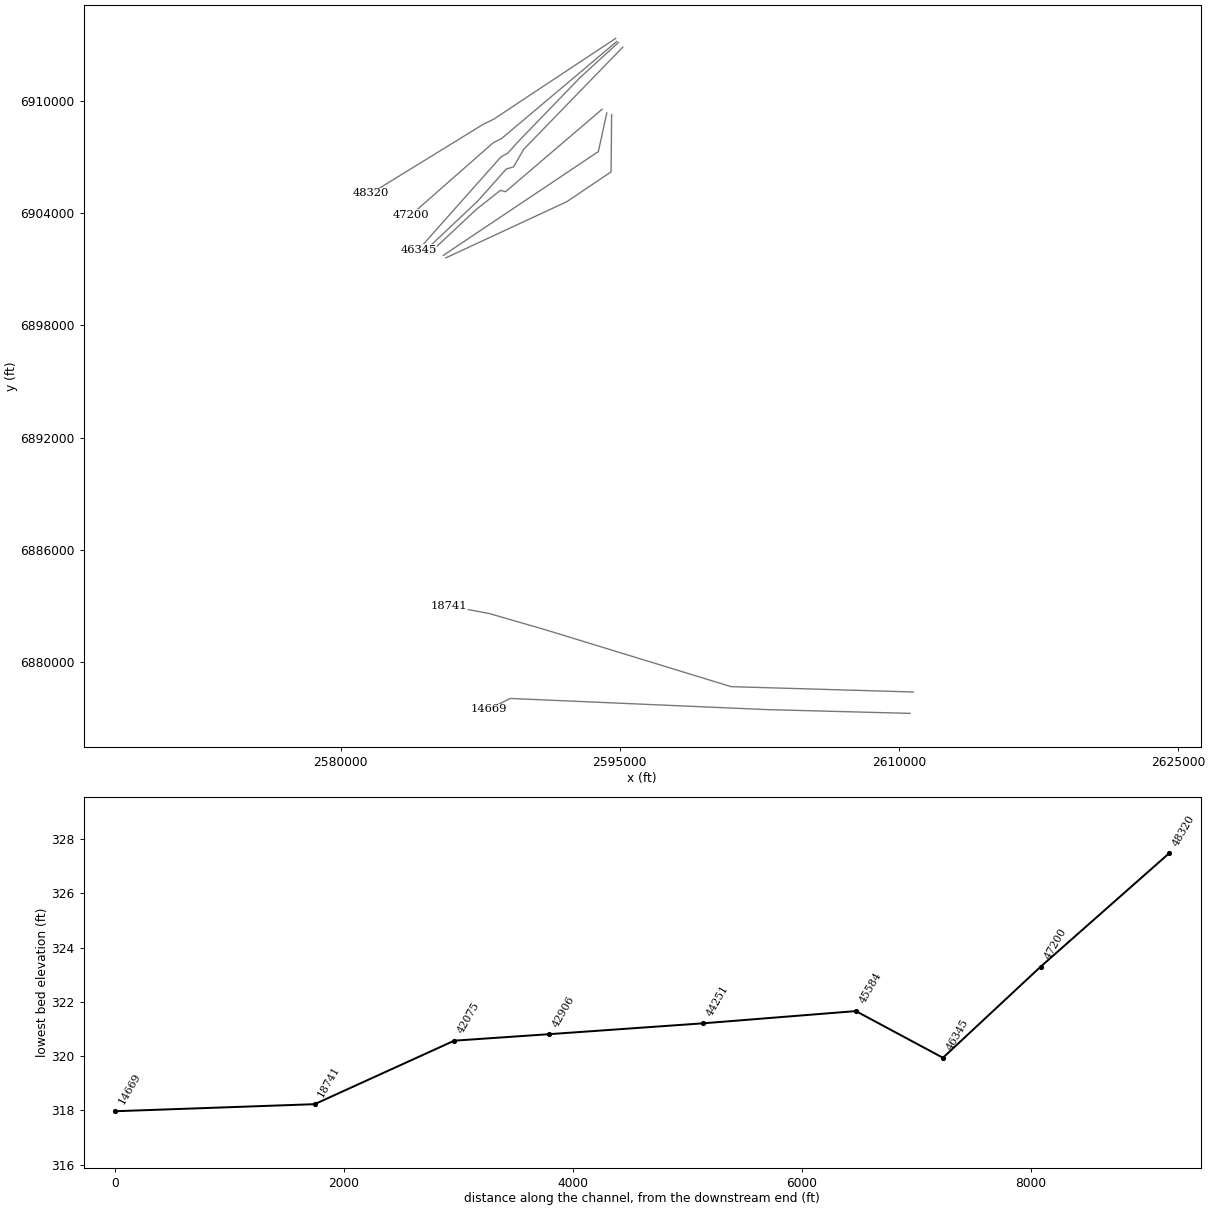
HEC-RAS study EF_FEMA.prj: East_Fork_FEMA

--- EF_FEMA.g03 (geometry) --- (continued)

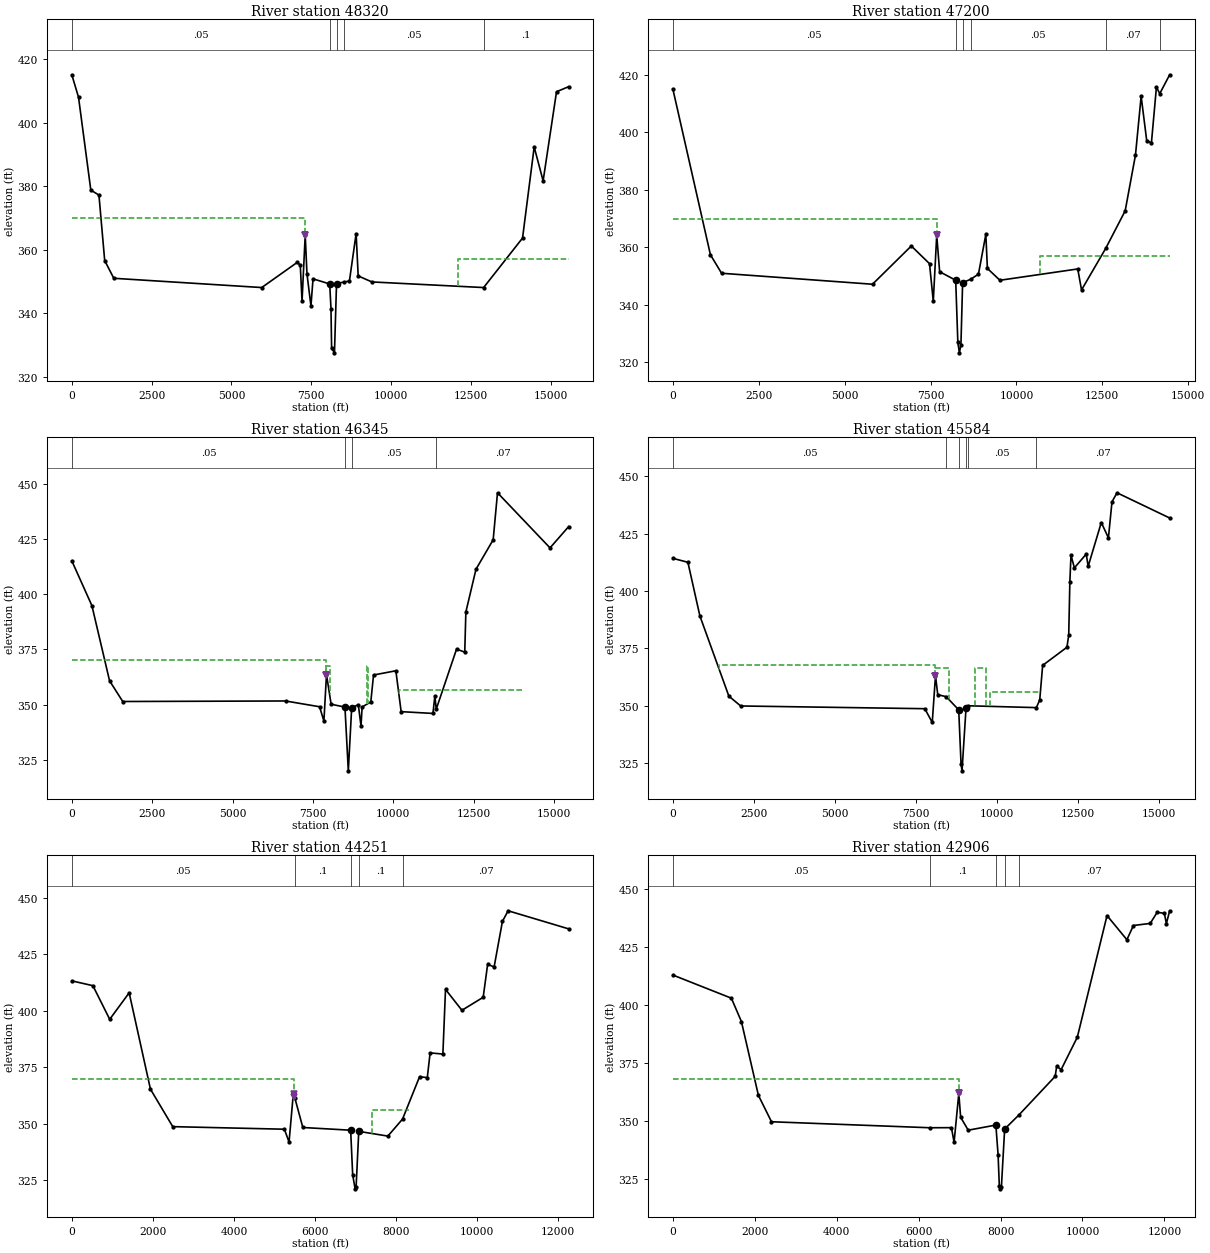
Type RM Length L Ch R = 1 ,48320   ,1117.07,1120.41,1502.42
BEGIN DESCRIPTION:
LOB - Kaufman 5 East
END DESCRIPTION:
XS GIS Cut Line= 5
2594779.815402466913365.921958982589704.538479556910018.63075331
2588220.341316716909033.61041364 2587673.45494336908773.21264048
2581622.233778066905062.72990398
#Sta/Elev= 30
       0  415.16  209.99  408.08  594.97   378.8  849.96  377.21 1029.95  356.57
 1314.93  350.98 5949.71  348.06 7062.67     356 7157.47   355.1 7212.36  343.75
 7312.15  364.63 7367.04  352.38 7491.78  342.27 7556.64   350.8 8079.47   349.2
 8119.19  341.41 8139.05  328.94 8228.42  327.47 8292.96  349.28  8540.6  349.84
 8696.68   350.1 8906.64  365.05 8971.62  351.72 9401.54  349.83 12901.2  348.06
14120.54  363.6614485.46  392.38 14765.4  381.7115185.32  409.8115565.24  411.41
#Mann= 5 ,-1 , 0
       0     .05       0 8079.47    .045       0 8292.96     .05       0
  8540.6     .05       0 12901.2      .1       0
Levee=-1,7312.18,364.63,0,,,,
#XS Ineff= 2 , 0
       0 7312.18     370   12104       0     357
Permanent Ineff=
       F       F
Bank Sta=8079.47,8292.96
XS Rating Curve= 0 ,0
Exp/Cntr=0.3,0.1

Type RM Length L Ch R = 1 ,47200   ,849.08,854.74,1118.27
BEGIN DESCRIPTION:
LOB - Kaufman 5 East
END DESCRIPTION:
XS GIS Cut Line= 4
2594837.106954566913199.255297562588663.692136056908017.22104223
2588173.46641047 6907757.56867442583775.011624726903908.21613689
#Sta/Elev= 30
       0  415.14 1094.33  357.42 1419.13  350.99 5811.45  347.17 6940.76  360.48
 7470.43  354.33 7580.36  341.23  7680.3  364.24 7765.25  351.53 8232.54  348.56
 8294.96  326.94 8339.95   323.3 8384.93  326.08 8434.05   347.7 8676.88  348.95
 8894.84  350.69 9109.84   364.5 9154.84  352.67 9519.84  348.5511784.84  352.49
11894.84  345.1912598.24  359.6313164.84   372.713464.84  392.1113629.84  412.57
13794.84  396.8713929.84  396.4714074.84  415.7714171.05  413.4814459.84  420.05
#Mann= 6 ,-1 , 0
       0     .05       0 8232.54    .045       0 8434.05     .05       0
 8676.88     .05       012598.24     .07       014171.05      .1       0
Levee=-1,7680.23,364.24,0,,,,
#XS Ineff= 2 , 0
       0 7680.23     370   10693       0     357
Permanent Ineff=
       F       F
Bank Sta=8232.54,8434.05
XS Rating Curve= 0 ,0
Exp/Cntr=0.5,0.3

Type RM Length L Ch R = 1 ,46345   ,777.22,761,653.03
BEGIN DESCRIPTION:
US Bridge
LOB - Kaufman 5 East
END DESCRIPTION:
XS GIS Cut Line= 6
2594925.64877222 6913141.96341742592858.618785566911263.34611164
2589469.304369976907767.00107023 2588993.98773536907233.66191381
2588610.966519716907017.985507892584191.103968386902062.58859456
#Sta/Elev= 30
       0  415.15  624.59  394.86 1174.23  360.77 1583.96  351.38 6647.79  351.62
 7707.65     349 7842.53  342.49 7922.46  363.58 8067.34  350.14 8496.97  348.85
 8601.87  319.94 8706.76  348.58 8912.49  349.94 8996.52  340.32 9031.49  348.89
 9301.28   351.2 9386.21  363.3910080.67  365.3210245.54  346.7811234.77  345.97
11294.72  353.9111336.75   347.911969.19  375.1312223.99  373.7712258.97  391.98
12573.72  411.36 13108.3  424.72 13243.2  446.0314876.92  421.0415456.47  430.69
#Mann= 4 ,-1 , 0
       0     .05       0 8496.97    .045       0 8706.76     .05       0
11336.75     .07       0
Levee=-1,7922.46,363.58,0,,,,
#XS Ineff= 4 ,-1
       0 7922.46     370 7922.46    8018   367.5  9176.9 9212.61   367.5
   10174   14000   356.6
Permanent Ineff=
       F       F       F       F
Bank Sta=8496.97,8706.76
XS Rating Curve= 0 ,0
Exp/Cntr=0.5,0.3

Type RM Length L Ch R = 1 ,45584   ,967.31,1332.53,361.44
BEGIN DESCRIPTION:
DS Bridge
LOB - Kaufman 5 East
END DESCRIPTION:
XS GIS Cut Line= 6
2595154.815308636912891.963589312589835.605474646907426.51093756
2589282.320491976906482.568599732588894.303223396906370.30307622
 2587378.35317136904669.299588472584516.62497088 6901975.7829939
#Sta/Elev= 30
       0  414.27  464.79  412.55  834.63  389.18 1729.24  354.22 2094.08  349.93
 7776.47  348.74 8006.28  342.75  8106.2  363.12 8176.15  354.84 8436.37  353.99
 8823.08  348.23 8895.26  324.59 8925.18  321.66 9048.47  348.95 9106.64  350.02
 11217.9  349.21 11323.3   352.511413.25  367.6212163.25  375.5212218.25  380.88
12253.25  404.1712288.25  415.6112393.25  410.1212758.25  416.1212818.25   410.8
13223.25  429.8713443.25  423.2113553.25  438.8813708.25  442.8415333.25  431.85
#Mann= 6 ,-1 , 0
       0     .05       0 8436.37      .1       0 8823.08    .045       0
 9048.47      .1       0 9106.64     .05       0 11217.9     .07       0
Levee=-1,8106.29,363.12,0,,,,
#XS Ineff= 4 ,-1
    1440 8106.29     368 8106.29    8533   366.5    9327    9668   366.5
    9792   11365     356
Permanent Ineff=
       F       F       F       F
Bank Sta=8823.08,9048.47
XS Rating Curve= 0 ,0
Exp/Cntr=0.5,0.3

Type RM Length L Ch R = 1 ,44251   ,1282.65,1345.57,1145.65
BEGIN DESCRIPTION:
LOB - Kaufman 5 East
END DESCRIPTION:
XS GIS Cut Line= 5
2594046.035702056909571.283878982588856.799689476905154.18346123
2588587.650949556905231.111456982587301.419270056904220.50422622
2584722.787944396901813.02249265
#Sta/Elev= 30
       0  413.19  519.97  411.06  934.95  396.19 1414.92  407.91 1939.89   365.3
 2489.86  348.72 5244.72  347.58 5359.71   341.9  5464.7  363.24  5501.6  361.48
 5699.69  348.34  6879.6  347.14 6929.58  327.44 6989.57  321.21 7014.56  322.15
 7079.55  346.63 7797.73  344.54 8160.12  352.07 8580.72  370.83 8770.32  370.38
 8840.28  381.34 9155.09  380.82 9220.05  409.42 9624.81  400.1810149.49  405.93
10259.43   420.510419.33  419.3510624.21  439.4910764.12  444.1912258.23  436.19
#Mann= 5 ,-1 , 0
       0     .05       0  5501.6      .1       0  6879.6    .045       0
 7079.55      .1       0 8160.12     .07       0
Levee=-1,5489.75,363.16,0,,,,
#XS Ineff= 2 ,-1
       0 5489.75     370    7410    8310     356
Permanent Ineff=
       F       F
Bank Sta=6879.6,7079.55
XS Rating Curve= 0 ,0
Exp/Cntr=0.3,0.1

Type RM Length L Ch R = 1 ,42906   ,907.64,831.04,782.67
BEGIN DESCRIPTION:
LOB - Kaufman 5 East
END DESCRIPTION:
XS GIS Cut Line= 3
2594297.772075226909371.631391142593845.622388976907306.79825048
2585514.888722396901747.91862023
#Sta/Elev= 30
       0  412.86 1429.16  402.89 1674.02  392.84 2088.78  361.07 2408.61  349.69
  6275.2  347.11 6801.43  347.15  6866.4  340.89 6981.34  361.89 7026.32  351.62
 7211.23  346.06  7885.9  348.27 7940.87  335.31 7970.86  321.87 7995.85  320.81
 8020.83   321.5 8100.79  346.56 8448.57  352.61 9335.21  369.26  9370.2  373.59
 9480.15  372.16 9874.96  386.1110599.62  438.46 11084.4  428.0711244.32  434.18
11654.13  435.0811824.05  439.8611998.97  439.4312048.95  435.0212128.91  440.52
#Mann= 5 ,-1 , 0
       0     .05       0  6275.2      .1       0  7885.9    .045       0
 8100.79      .1       0 8448.57     .07       0
Levee=-1,6981.34,361.89,0,,,,
#XS Ineff= 2 , 0
       0 6981.34     368    8821       0     356
Permanent Ineff=
       F       F
Bank Sta=7885.9,8100.79
XS Rating Curve= 0 ,0
Exp/Cntr=0.3,0.1

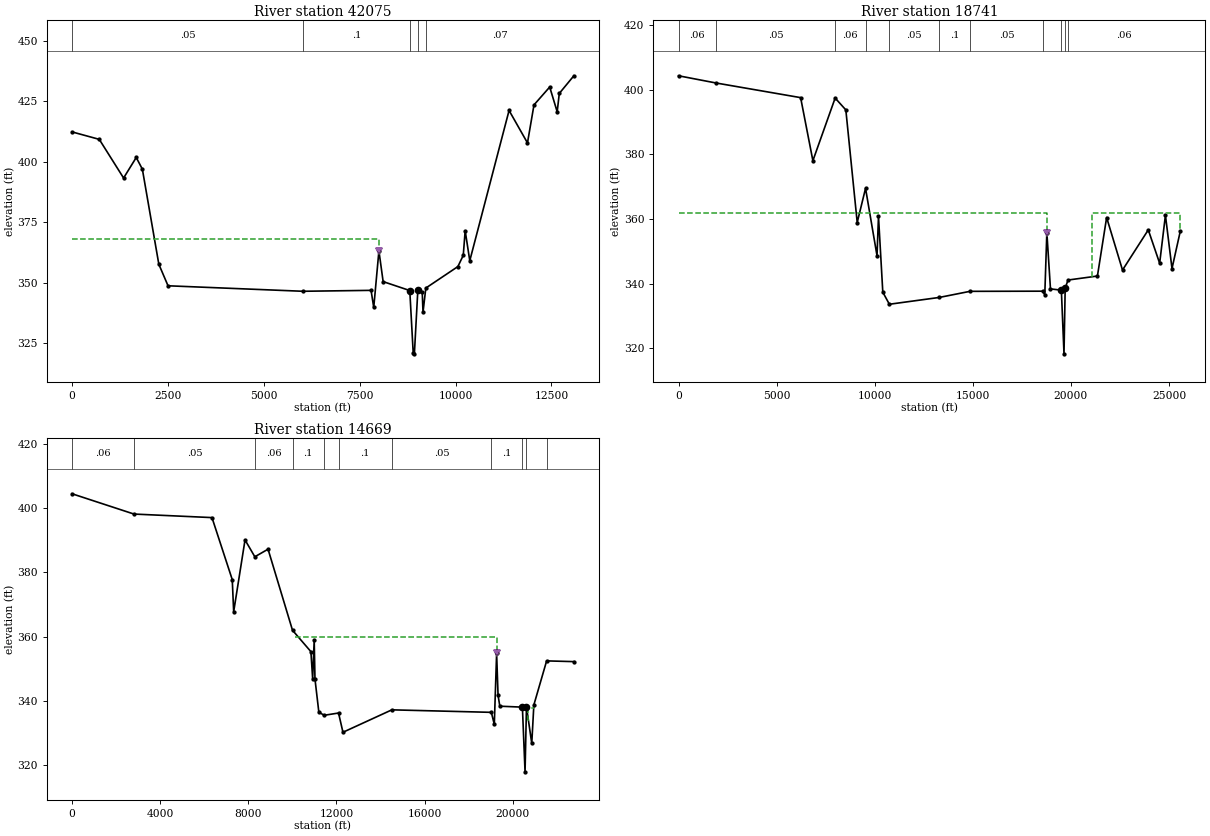
Type RM Length L Ch R = 1 ,42075   ,1066.9,1219.97,1124.41
BEGIN DESCRIPTION:
LOB - Kaufman 5 East
END DESCRIPTION:
XS GIS Cut Line= 4
2594558.188549136909284.82579048 2594527.03572436906218.12949607
2592143.249809476904619.118914562585655.947823466901617.71021923
#Sta/Elev= 30
       0  412.37  709.27  409.29 1343.62   393.3 1673.28  401.79 1833.12  396.96
 2262.68  357.62 2502.44  348.72 6018.52  346.45 7796.83  346.83 7866.81  339.75
 8001.77  363.17 8111.75  350.45 8806.54  346.75 8896.52  320.78 8926.51  320.57
 9016.48  346.92 9131.45  345.99 9151.44  337.76 9224.91  347.7810061.18  356.67
10201.14  361.3110251.12  371.4910371.09   359.111395.79  421.2411875.65  407.82
 12045.6  423.5412455.48  430.9412650.42   420.712705.41  428.29 13085.3  435.59
#Mann= 5 ,-1 , 0
       0     .05       0 6018.52      .1       0 8806.54    .045       0
 9016.48      .1       0 9224.91     .07       0
Levee=-1,8001.7,363.18,0,,,,
#XS Ineff= 2 , 0
       0  8001.7     368   10178       0   356.8
Permanent Ineff=
       F       F
Bank Sta=8806.54,9016.48
XS Rating Curve= 0 ,0
Exp/Cntr=0.3,0.1

Type RM Length L Ch R = 1 ,18741   ,1655.65,1742.82,1950.26
BEGIN DESCRIPTION:
LOB - Kaufman MUD1
ROB IFA station 211097: flow expansion due to natural high ground upstream
END DESCRIPTION:
XS GIS Cut Line= 5
2610763.852660066878378.988652142600975.607472816878665.28499556
2590955.961501646881722.923565312587971.051132896882582.00747706
 2585804.89962536882984.95319347
#Sta/Elev= 30
       0  404.36 1899.51  402.14 6223.41  397.59 6848.26  378.06 7982.98  397.46
 8527.83  393.79 9107.67  358.91 9532.54   369.510117.34  348.6210192.31   360.8
10412.23  337.3310747.09  333.59 13291.1   335.714855.49  337.5918569.04  337.64
   18669  336.5118773.96  355.8118958.89  338.3419513.67  337.9619648.62  318.23
19708.59  338.5719853.54  341.09 21352.1  342.3321821.55  360.46 22630.6  344.18
23944.29  356.6324523.83  346.29 24818.6  361.1525153.34  344.6625578.01  356.27
#Mann= 11 ,-1 , 0
       0     .06       0 1899.51     .05       0 7982.98     .06       0
 9532.54      .1       010747.09     .05       0 13291.1      .1       0
14855.49     .05       018569.04      .1       019513.67    .045       0
19708.59      .1       019853.54     .06       0
Levee=-1,18773.96,355.81,0,,,,
#XS Ineff= 2 ,-1
        18773.96     362 21097.425578.01     362
Permanent Ineff=
       F       F
Bank Sta=19513.67,19708.59
XS Rating Curve= 0 ,0
Exp/Cntr=0.3,0.1

Type RM Length L Ch R = 1 ,14669   ,1925.16,2040.36,2071.02
BEGIN DESCRIPTION:
LOB - Kaufman MUD1
END DESCRIPTION:
XS GIS Cut Line= 4
2610583.787731476877234.965021572602891.72535972 6877436.8990009
2589111.343471726878033.687505482587959.75128672 6877462.1194229
#Sta/Elev= 30
       0  404.48  2809.9  398.17 6349.68  397.07 7269.61  377.78  7334.6  367.79
 7849.56  390.13  8294.5  384.88 8894.38  387.2410004.17  362.02   10839  355.37
10918.99  346.9810988.97  358.9411023.97  346.8511198.93  336.5711438.88  335.56
12093.76  336.2712293.72  330.2814513.28  337.2619027.92  336.4819162.92  332.74
19267.92  354.8319332.92  341.8319412.92  338.3920437.92   338.120557.92  317.97
20622.92  338.1920862.92  326.8120957.92  338.7921537.74  352.4922773.38  352.26
#Mann= 11 ,-1 , 0
       0     .06       0  2809.9     .05       0  8294.5     .06       0
10004.17      .1       011438.88     .05       012093.76      .1       0
14513.28     .05       019027.92      .1       020437.92    .045       0
20622.92      .1       021537.74     .06       0
Levee=-1,19267.92,354.83,0,,,,
#XS Ineff= 2 ,-1
   1011519267.92     36020712.92 20952.5  337.85
Permanent Ineff=
       F       F
Bank Sta=20437.92,20622.92
XS Rating Curve= 0 ,0
Exp/Cntr=0.3,0.1

--- EF_FEMA.g04 (geometry) ---

Geom Title=EastFork_NV_Kauf_LID10
Program Version=5.06
BEGIN GEOM DESCRIPTION:
Scenario J
END GEOM DESCRIPTION:

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
River Reach=East Fork       ,1

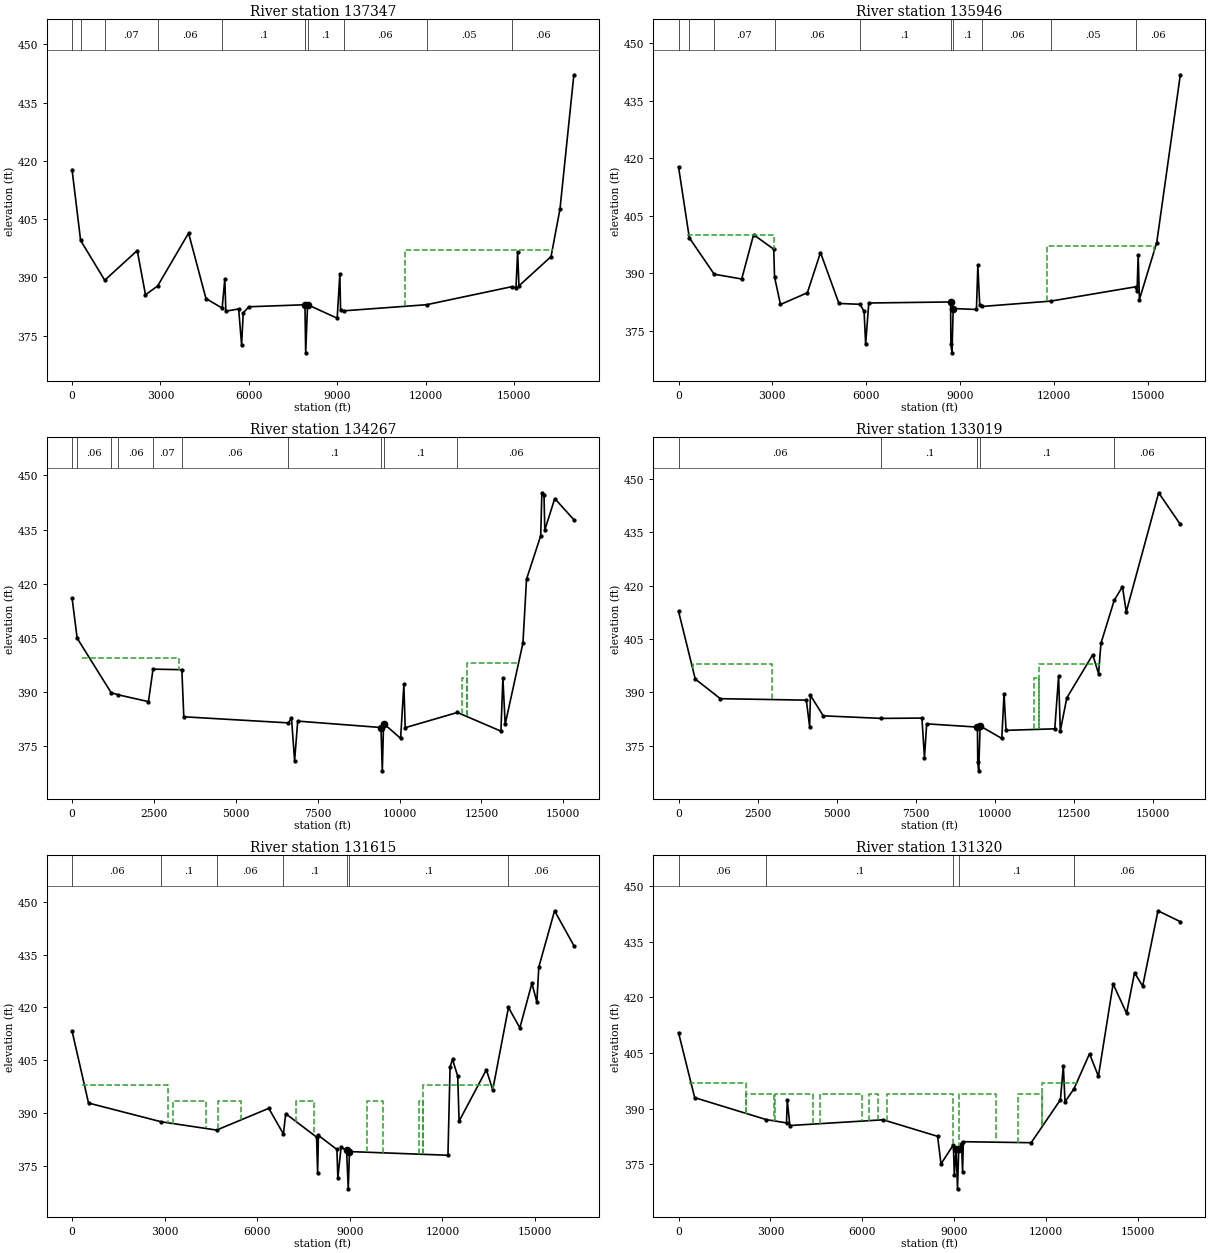
Type RM Length L Ch R = 1 ,137347  ,1140.97,1400.58,978.45
BEGIN DESCRIPTION:
LOB IFA station 3953.68: flow contraction due to natural high ground
END DESCRIPTION:
XS GIS Cut Line= 5
2588787.69779356 6964514.75043542587225.197637726964556.41701873
2585029.793892066965464.120911972573906.166861136968072.27514447
2572454.730787636967259.87585065
#Sta/Elev= 30
       0  417.72  289.64  399.51 1108.62  389.24 2211.87   396.9 2491.35   385.5
  2900.6  387.74 3953.68  401.38 4543.44  384.52 5093.21  382.07 5183.18  389.58
 5218.16  381.28 5652.98  381.84 5752.94  372.55 5807.92  380.84 6002.84  382.41
 7902.06  382.93 7927.05  370.54 7992.02  382.94 8996.63  379.46 9086.59  390.92
 9111.58  381.48 9211.54  381.3612030.44  382.9414919.31  387.5815064.25  387.34
15119.23  396.5615164.22   387.816253.27  395.3416557.95  407.6617027.45  442.18
#Mann= 10 ,-1 , 0
       0     .07       0  289.64     .06       0 1108.62     .07       0
  2900.6     .06       0 5093.21      .1       0 7902.06    .045       0
 7992.02      .1       0 9211.54     .06       012030.44     .05       0
14919.31     .06       0
#XS Ineff= 2 ,-1
     235 3953.68  401.38 11285.9   16316     397
Permanent Ineff=
       F       F
Bank Sta=7902.06,7992.02
XS Rating Curve= 0 ,0
Exp/Cntr=0.3,0.1

Type RM Length L Ch R = 1 ,135946  ,940.19,1679.57,1522.42
BEGIN DESCRIPTION:
LOB IFA station 4539.01: flow contraction due to natural high ground
END DESCRIPTION:
XS GIS Cut Line= 6
2588792.906116476964431.417268722584150.093551736964534.61555314
2580302.000198056965452.483468062580109.291593976965663.42103831
2574802.434097476966908.357196732573353.168295226966005.53551157
#Sta/Elev= 30
       0  417.71  344.92  399.25 1139.74  389.77 2019.54  388.52 2399.46  400.06
 3044.33  396.28 3069.32  389.04 3259.28  381.88  4119.1  384.93 4539.01  395.41
  5128.5  382.15 5797.82  381.93 5932.68  380.11 5982.63  371.58 6082.53  382.27
 8698.51  382.54 8708.36   371.5 8742.84  369.29 8782.25  380.83 9525.19  380.58
 9570.15  392.06 9630.11  381.72 9715.04  381.3711908.33  382.7714611.02  386.48
14660.95  385.3914695.89  394.8314735.83  383.18   15290  398.0216043.86   441.7
#Mann= 10 ,-1 , 0
       0     .07       0  344.92     .06       0 1139.74     .07       0
 3069.32     .06       0 5797.82      .1       0 8698.51    .045       0
 8782.25      .1       0 9715.04     .06       011908.33     .05       0
14611.02     .06       0
#XS Ineff= 3 ,-1
     280 3044.33     400 3044.33 4539.01  395.41 11795.9   15196     397
Permanent Ineff=
       F       F       F
Bank Sta=8698.51,8782.25
XS Rating Curve= 0 ,0
Exp/Cntr=0.3,0.1

Type RM Length L Ch R = 1 ,134267  ,945.86,1247.61,984.8
BEGIN DESCRIPTION:
LOB IFA station 3271.67: flow contraction due to natural high ground
END DESCRIPTION:
XS GIS Cut Line= 6
2588765.04134281 6964353.29209692587657.48942405 6964353.2920969
2585886.656023476963587.667315812579703.193652886964540.00497806
2576021.786645646964703.762524562573752.039544726964430.88282098
#Sta/Elev= 30
       0  416.04  154.66  404.91 1192.52  389.82 1402.44  389.24 2332.08  387.33
 2472.03  396.33 3351.63  396.18 3411.59  383.14 6604.72  381.45 6699.67  382.82
 6794.61  370.95 6889.55  381.94 9432.35  380.17 9472.12  368.17  9511.9  381.27
10031.17  377.1710131.13   392.110171.11  380.1211765.49  384.33 13094.6  379.16
13154.33  393.8813224.02  381.0613766.57  403.5613876.08  421.2414309.42  433.28
14344.31  445.1714409.11  444.6914434.03  434.8614738.08  443.5815321.25  437.71
#Mann= 10 ,-1 , 0
       0     .07       0  154.66     .06       0 1192.52     .07       0
 1402.44     .06       0 2472.03     .07       0 3351.63     .06       0
 6604.72      .1       0 9432.35    .045       0  9511.9      .1       0
11765.49     .06       0
#XS Ineff= 3 ,-1
     296 3271.67   399.5 11907.712051.15     39412051.15   13675     398
Permanent Ineff=
       F       F       F
Bank Sta=9432.35,9511.9
XS Rating Curve= 0 ,0
Exp/Cntr=0.3,0.1

Type RM Length L Ch R = 1 ,133019  ,1384.23,1404.04,669.16
XS GIS Cut Line= 6
2588754.190642716964308.587461892587669.034348476964243.83037356
2585644.468515726962879.449572152577308.228298476963605.97731856
2577133.749316726963332.53987332 2573698.65415286964403.53904365
#Sta/Elev= 30
       0  412.81  528.58  393.76 1321.74  388.24 4037.95  387.83 4142.85  380.42
 4167.82   389.2 4572.66  383.42 6407.22   382.7 7691.92  382.79  7771.9  371.67
 7841.88  381.17 9446.45  380.25 9456.44  370.33 9486.43  367.96 9531.42  380.58
10216.23  377.0610286.21  389.6410351.19  379.3411890.76  379.77 12010.6  394.56
12065.49  379.23 12270.1  388.4513089.62  400.5913274.52  395.2613349.47  403.79
13769.23   415.914029.07  419.72   14149  412.64 15173.4  446.11   15858  437.22
#Mann= 5 ,-1 , 0
       0     .06       0 6407.22      .1       0 9446.45    .045       0
 9531.42      .1       013769.23     .06       0
#XS Ineff= 3 ,-1
     454    2945     398 11247.311390.75     39411390.75   13291     398
Permanent Ineff=
       F       F       F
Bank Sta=9446.45,9531.42
XS Rating Curve= 0 ,0
Exp/Cntr=0.3,0.1

Type RM Length L Ch R = 1 ,131615  ,369.03,295,387.25
XS GIS Cut Line= 6
 2588747.15948886964284.194794152587668.760726976964143.37617815
2584852.372658976962150.103589892582383.203056636961929.92128748
2577347.612734146963234.825829892573662.195892396964391.82023506
#Sta/Elev= 30
       0  413.26  533.43   392.8 2888.33  387.47 4683.03  385.11 6372.96   391.3
  6846.4     384 6921.16  389.77 7920.21  383.12 7955.18   372.8 7980.17   383.6
  8579.8   379.6 8609.78  371.55 8714.72   380.2 8893.24  379.32 8947.46   368.4
 8986.89     37912176.84  377.9512245.58  403.1412324.14  405.2112492.83  400.45
 12537.8  387.6513422.28  402.2713627.16  396.5214136.86  419.9914506.64  414.18
14896.42  426.8615056.32  421.5615121.28  431.5215630.99  447.4816255.62  437.57
#Mann= 7 ,-1 , 0
       0     .06       0 2888.33      .1       0 4683.03     .06       0
  6846.4      .1       0 8893.24    .045       0 8986.89      .1       0
14136.86     .06       0
#XS Ineff= 7 ,-1
     306  3102.4     398  3278.5  4337.6   393.5  4728.8    5473   393.5
  7256.4  7839.6   393.5  9555.7 10058.1   393.5   1123111374.45   393.5
11374.45   13635     398
Permanent Ineff=
       F       F       F       F       F       F       F
Bank Sta=8893.24,8986.89
XS Rating Curve= 0 ,0
Exp/Cntr=0.5,0.3

Type RM Length L Ch R = 1 ,131320  ,172.92,142.52,224.66
BEGIN DESCRIPTION:
US Bridge
END DESCRIPTION:
XS GIS Cut Line= 6
2588737.414429566964257.794584482587680.556963226964114.56554022
2584666.667977886961956.290001142583241.320762986961464.97044572
2582687.501332556961497.956600232573617.924983556964386.61191215
#Sta/Elev= 30
       0  410.48  526.75  392.94 2864.51  387.01 3524.75  386.12 3549.73  392.26
 3634.65  385.41 6678.04  386.96 8457.71  382.49 8567.68  375.03 8972.61   380.2
  9002.6  372.04 9062.59  379.12 9107.58  368.31 9148.43  379.19 9237.55  380.64
 9272.55   372.9 9297.54  381.0411512.11  380.7712466.92  392.36 12561.9  401.53
12616.89  391.7912911.93  395.3713416.74  404.7913706.68  398.7314186.59  423.64
 14626.5  415.7314886.45  426.68 15151.4  423.05 15651.3  443.4116381.16  440.47
#Mann= 5 ,-1 , 0
       0     .06       0 2864.51      .1       0 8972.61    .045       0
 9148.43      .1       012911.93     .06       0
#XS Ineff= 9 ,-1
     350    2215     397    2215    3121     394    3163    4396     394
    4630    6005     394 6209.61    6503     394 6792.79    8960     394
    9165   10375     394   11085   11880     394   11880   13035     397
Permanent Ineff=
       F       F       F       F       F       F       F       F       F
Bank Sta=9062.59,9148.43
XS Rating Curve= 0 ,0
Exp/Cntr=0.5,0.3

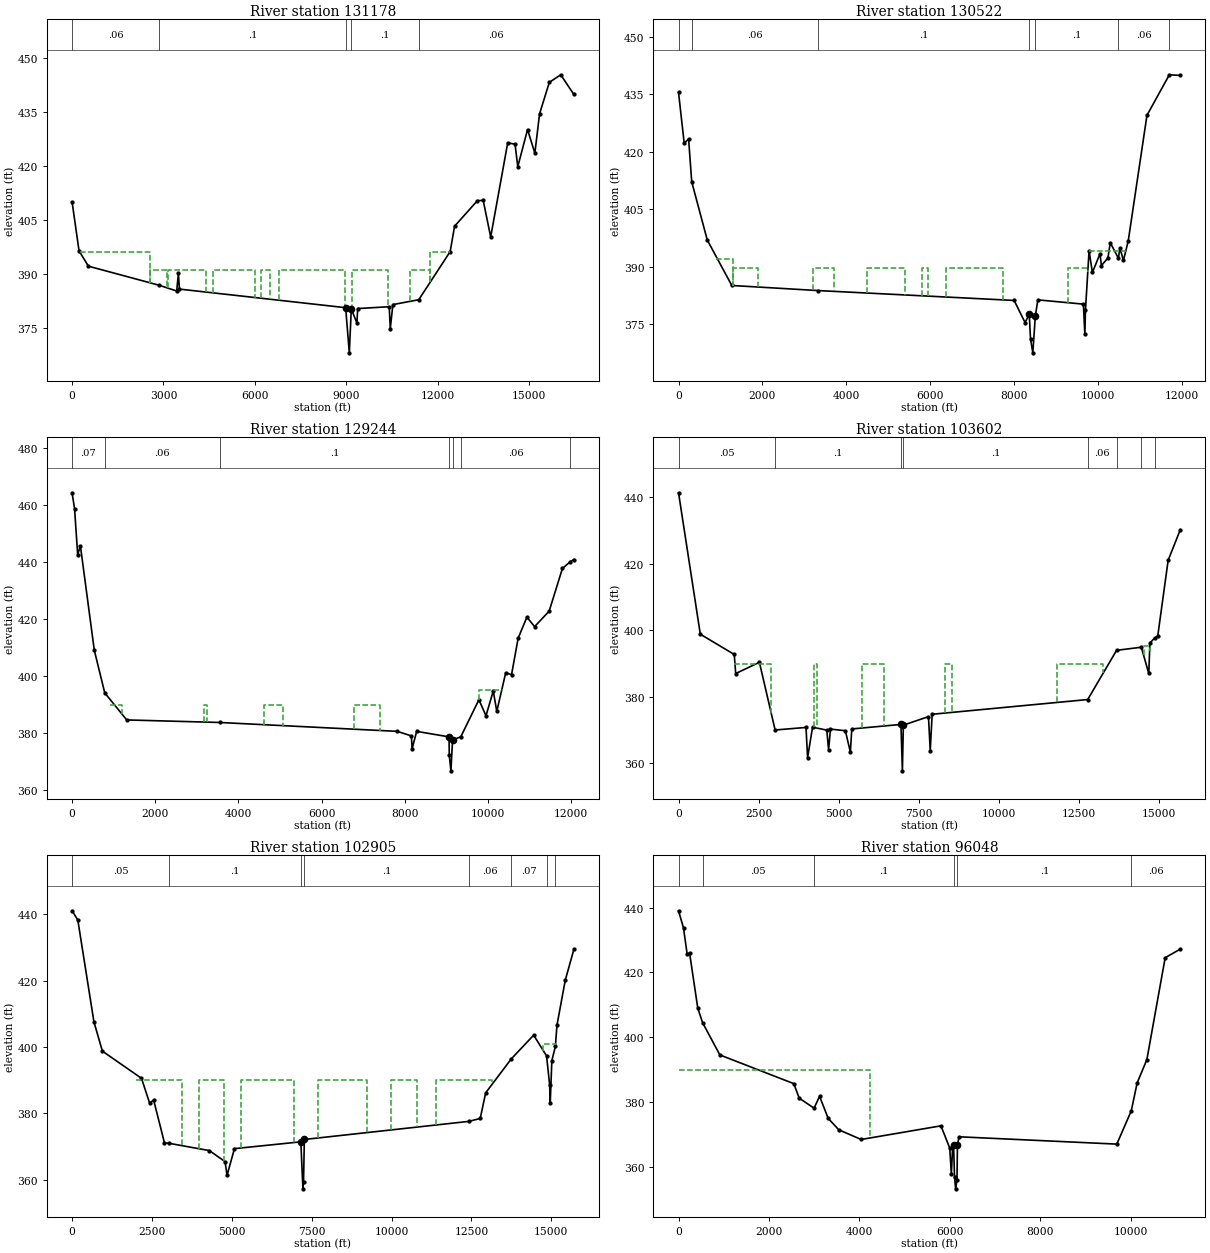
Type RM Length L Ch R = 1 ,131178  ,422.59,655.81,1080.74
BEGIN DESCRIPTION:
DS Bridge
END DESCRIPTION:
XS GIS Cut Line= 6
2588751.538417066964138.107815982587631.747021476963951.91002564
2584272.805904726961633.116434892583239.819781726961368.35974656
2582661.477762556961371.614661312573552.820783056964356.23008314
#Sta/Elev= 30
       0  410.02  228.84  396.38  537.27  392.11 2858.58  386.81 3433.69  385.21
  3488.6  390.14 3523.55  385.74 8977.57  380.57 9097.55  368.01 9162.53  380.19
  9347.5  376.33 9372.49  380.3310407.29  380.8410442.28  374.7810527.27  381.43
11375.92  382.78 12406.9  396.1712551.87  403.2313301.73  410.3513491.69   410.4
13736.64  400.2414296.53  426.4614536.48  426.0214626.47  419.81 14946.4  430.12
15186.36  423.5615341.33  434.5215661.26  443.2516036.19  445.3616466.12  439.89
#Mann= 5 ,-1 , 0
       0     .06       0 2858.58      .1       0 8977.57    .045       0
 9162.53      .1       011375.92     .06       0
#XS Ineff= 9 ,-1
     250    2570     396    2570    3120     391    3156    4397     391
    4630    6005     391 6205.54    6500     391    6790    8970     391
    9170   10375     391   11100   11760     391   11760   12400     396
Permanent Ineff=
       F       F       F       F       F       F       F       F       F
Bank Sta=8977.57,9162.53
XS Rating Curve= 0 ,0
Exp/Cntr=0.5,0.3

Type RM Length L Ch R = 1 ,130522  ,825.93,1278.14,964.51
XS GIS Cut Line= 4
2588948.37726222 6960912.01551492584693.881178056961031.34434448
2582688.672918146961070.406602312577053.341669146961888.04440273
#Sta/Elev= 30
       0  435.45  134.88  422.19  239.78  423.32  314.15  412.16  684.38  396.99
 1268.86  385.14 3316.13  383.82  7996.6  381.24 8256.57  375.48 8356.56  377.63
 8386.56  371.21 8441.55  367.59 8501.54  377.22 8561.53  381.39  9646.4  380.28
 9681.39  372.43 9696.39  378.83 9781.38  394.15 9861.37  388.5310041.35  393.38
10076.34  390.3310231.32  392.3210286.32  396.2910480.97  392.2410516.29  394.91
10601.28  391.6510716.26  396.8311161.21  429.4811694.34  440.0411956.11  439.87
#Mann= 7 ,-1 , 0
       0     .07       0  314.15     .06       0 3316.13      .1       0
 8356.56    .045       0 8501.54      .1       010480.97     .06       0
11694.34     .05       0
#XS Ineff= 8 ,-1
     890    1300     392    1300    1887  389.75    3199    3704  389.75
 4487.91  5401.7  389.75 5803.14 5954.81  389.75 6370.56 7740.43  389.75
 9288.19    9751  389.75 9781.38   10656  394.15
Permanent Ineff=
       F       F       F       F       F       F       F       F
Bank Sta=8356.56,8501.54
XS Rating Curve= 0 ,0
Exp/Cntr=0.3,0.1

Type RM Length L Ch R = 1 ,129244  ,922.95,1040.29,819.79
XS GIS Cut Line= 4
2588788.655140716959898.126794652579823.828582216960512.30896522
2579563.252331726960609.753324152576761.67492963 6960679.7108614
#Sta/Elev= 30
       0  464.15   59.97   458.6  134.94  442.42  199.91  445.61  534.75  408.98
  786.12  394.05 1314.39  384.59  3547.4   383.7  7821.4  380.59 8161.24  378.98
 8176.23  374.44 8286.19  380.58  9065.4  378.66 9070.37  372.34 9110.11  366.76
 9149.85  377.56 9347.56  378.69 9783.65  391.66  9953.5  386.0510128.34  394.73
10213.27   387.610428.07  401.1110567.95  400.4410727.81  413.2710937.62  420.59
11122.45  417.2711472.14  422.6811791.86  437.64 11985.7  440.0712066.61  440.76
#Mann= 7 ,-1 , 0
       0     .07       0  786.12     .06       0  3547.4      .1       0
  9065.4    .045       0 9149.85      .1       0 9347.56     .06       0
 11985.7     .05       0
#XS Ineff= 5 ,-1
     920    1198  389.75    3164    3250  389.75 4620.21 5073.91  389.75
 6790.06 7416.27  389.75 9783.65   10358     395
Permanent Ineff=
       F       F       F       F       F
Bank Sta=9065.4,9149.85
XS Rating Curve= 0 ,0
Exp/Cntr=0.3,0.1

Type RM Length L Ch R = 1 ,103602  ,491.43,697.56,687.23
XS GIS Cut Line= 4
2581338.134280646944053.508549562574691.724345136944075.03114431
2570026.547323816944689.645072562565718.344654146944640.17830798
#Sta/Elev= 30
       0  441.38  679.64  398.86 1739.07  392.76 1784.05  387.03 2523.65   390.4
 3014.39  370.05 3977.86  370.82 4027.83  361.74 4182.75   370.9 4627.52  370.01
 4682.49  364.11 4742.46  370.32 5207.23  369.83 5362.15  363.39 5407.13  370.37
 6941.21  371.72 6986.16  357.77 7016.13  371.51 7800.37  374.07 7855.31  363.88
 7915.26  374.7812769.61  379.2113671.06  394.01 14443.2  394.94 14675.6  387.04
14710.58  396.17 14855.6   397.714955.49   398.315280.36  421.0915660.21   430.3
#Mann= 8 ,-1 , 0
       0     .05       0 3014.39      .1       0 6941.21    .045       0
 7016.13      .1       012769.61     .06       013671.06     .07       0
 14443.2      .1       0 14855.6     .06       0
#XS Ineff= 6 ,-1
    1730    2900     390 4213.59  4331.1     390 5717.27 6426.55     390
 8328.54 8538.55     39011818.01   13255     390   14511   14702   395.2
Permanent Ineff=
       F       F       F       F       F       F
Bank Sta=6941.21,7016.13
XS Rating Curve= 0 ,0
Exp/Cntr=0.5,0.3

Type RM Length L Ch R = 1 ,102905  ,527.41,553.15,508.18
BEGIN DESCRIPTION:
US Bridge
END DESCRIPTION:
XS GIS Cut Line= 6
 2581358.96757236943845.175304822578354.728502056943702.54665306
2574397.366338066943461.575350232573800.467925556943472.64192915
2568610.761769556944282.465440722565739.177945816944570.73389307
#Sta/Elev= 30
       0  441.09  179.86   438.3  684.46   407.6  949.25  398.78 2173.28  390.59
 2428.08  383.09 2552.98  384.05 2892.71  371.11 3038.95  370.99 4297.52   368.8
 4787.47  365.49 4852.46  361.37 5082.44  369.39 7161.31  371.44 7225.99  357.27
 7245.89  359.26 7270.76  372.1512416.83   377.612776.88  378.4812946.69   386.2
 13747.8  396.4314449.63   403.614853.04  397.3514948.95  388.7114968.92  383.26
15018.85  395.9415129.72  400.2115178.63  406.5615438.28  420.1415707.91  429.44
#Mann= 8 ,-1 , 0
       0     .05       0 3038.95      .1       0 7161.31    .045       0
 7270.76      .1       012416.83     .06       0 13747.8     .07       0
14853.04      .1       015129.72     .06       0
#XS Ineff= 7 ,-1
    2000    3447     390    3972    4752     390    5279    6934     390
    7698    9248     390    9976   10806     390   11395   13150     390
   14749   15140   400.9
Permanent Ineff=
       F       F       F       F       F       F       F
Bank Sta=7161.31,7270.76
XS Rating Curve= 0 ,0
Exp/Cntr=0.5,0.3

Type RM Length L Ch R = 1 ,96048   ,1090.05,1281.61,847.13
BEGIN DESCRIPTION:
LOB IFA station 4227: flow contraction due to natural high ground downstream
END DESCRIPTION:
XS GIS Cut Line= 4
2581233.967494226941900.731030972579112.051134396941810.50188072
 2575562.78231436940223.360698062570878.066946226938251.28951098
#Sta/Elev= 30
       0  439.01  109.94   433.7   189.9  425.69  244.87  425.94  424.77  409.05
   531.7   404.5   914.5  394.55 2548.61  385.71 2668.55  381.23 2997.16  378.14
 3118.31  381.82 3308.21  375.01 3543.09  371.48 4037.82  368.49 5801.96   372.7
 5996.86   365.8 6031.85  357.79 6061.83  366.49 6081.83  366.73 6101.82  356.97
 6126.81  353.27 6156.79  356.02 6166.79  366.72 6201.77  369.32 9690.34  367.06
10009.93   377.310140.16  385.9210355.08  393.1310759.92  424.5411094.79   427.2
#Mann= 6 ,-1 , 0
       0     .07       0   531.7     .05       0 2997.16      .1       0
 6081.83    .045       0 6166.79      .1       010009.93     .06       0
#XS Ineff= 2 , 0
       0    4227     390               0
Permanent Ineff=
       F       F
Bank Sta=6081.83,6166.79
XS Rating Curve= 0 ,0
Exp/Cntr=0.3,0.1

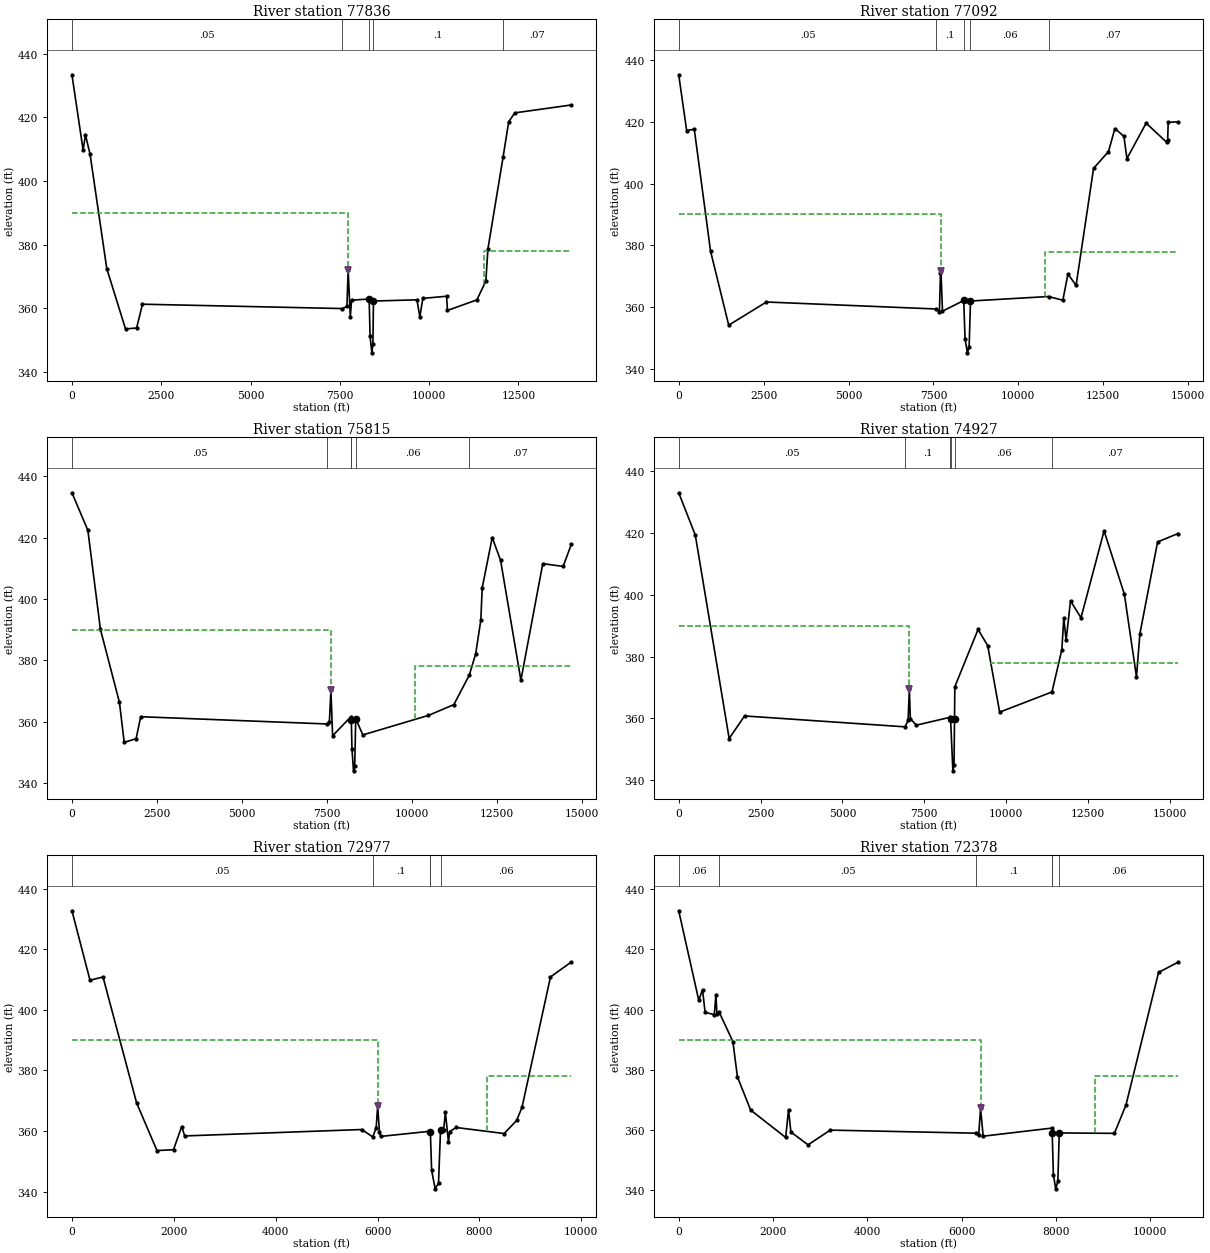
Type RM Length L Ch R = 1 ,77836   ,308.65,744.14,1041.53
BEGIN DESCRIPTION:
LOB - Kaufman LID15
ROB IFA station 11533: flow contraction due to natural high ground downstream
END DESCRIPTION:
XS GIS Cut Line= 6
2586329.106582146932169.480808482585634.53480855 6931884.9669418
2579288.946777976928005.586577222578886.169040226928005.58657722
2575587.846568636926473.917724562573967.606698896927143.31763248
#Sta/Elev= 30
       0  433.37  313.16  409.69  377.78   414.5  507.02  408.41  975.51  372.46
 1500.33  353.52 1810.23  353.82 1975.17  361.29 7574.07  359.92 7698.24  360.57
 7733.23  371.94 7793.21  357.31  7828.2  362.56 8321.11  362.92 8347.21   351.2
 8396.93  346.01 8426.77  348.88 8441.69  362.28 9659.82  362.67 9739.74  357.27
 9824.66  363.1210489.01  363.7910513.99  359.3211338.18  362.6611587.94  368.56
11647.88  378.7712069.63  407.4112227.31  418.5612397.11   421.413980.25  423.88
#Mann= 5 ,-1 , 0
       0     .05       0 7574.07      .1       0 8321.11    .045       0
 8441.69      .1       012069.63     .07       0
Levee=-1,7733.23,371.94,0,,,,
#XS Ineff= 2 , 0
       0 7733.23     390   11533       0     378
Permanent Ineff=
       F       F
Bank Sta=8321.11,8441.69
XS Rating Curve= 0 ,0
Exp/Cntr=0.3,0.1

Type RM Length L Ch R = 1 ,77092   ,943.98,1276.8,1378.67
BEGIN DESCRIPTION:
LOB - Kaufman LID15
ROB IFA station 10783.6: flow contraction due to natural high ground downstream
END DESCRIPTION:
XS GIS Cut Line= 6
2586356.884085646932096.56428765 2585642.12042336931804.04846847
2579052.835701636927186.142349972576169.750588556925433.65865023
2575728.610722816926049.683008732574162.919300396926785.24485782
#Sta/Elev= 30
       0  435.19  234.18  417.11   458.4  417.58  937.29  378.12 1472.24  354.16
 2582.12  361.66 7580.45   359.4 7676.66  358.53 7706.66  370.91 7721.65  371.63
 7766.65  358.69 8392.23  362.15 8431.57  349.61 8501.55  345.21 8551.53  347.26
 8591.52  361.9810888.78  363.4411310.65  362.23 11460.6  370.7311700.52  367.03
12215.35  404.9112653.98  410.3212843.39   417.813107.97  415.2913197.97  408.08
13762.92  419.5414362.87   413.414397.87  414.1914412.87  419.8214702.85  419.97
#Mann= 5 ,-1 , 0
       0     .05       0 7580.45      .1       0 8392.23    .045       0
 8591.52     .06       010888.78     .07       0
Levee=-1,7721.65,371.63,0,,,,
#XS Ineff= 2 , 0
       0 7721.65     390 10783.6       0     378
Permanent Ineff=
       F       F
Bank Sta=8392.23,8591.52
XS Rating Curve= 0 ,0
Exp/Cntr=0.3,0.1

Type RM Length L Ch R = 1 ,75815   ,500.58,888.74,1416.72
BEGIN DESCRIPTION:
LOB - Kaufman LID15
ROB IFA station 10102.8: flow contraction due to natural high ground downstream
END DESCRIPTION:
XS GIS Cut Line= 4
2586398.550997056932002.814147062585663.920248466931693.04376923
 2577151.74764036923830.090991232574868.214477726924105.12324956
#Sta/Elev= 30
       0  434.66   468.4   422.4  837.26  390.12 1397.17  366.24 1537.15  353.21
 1887.09  354.44 2022.07  361.59 7513.93  359.22 7571.07  359.76 7616.06  370.16
 7666.05  355.37 8204.61  361.59 8215.96  360.56 8235.95  350.92 8280.94  343.93
 8315.94  345.52 8345.93  360.93 8555.89  355.6510485.51  362.0211230.37  365.53
11683.22   375.111875.24  382.1612025.21  393.15 12065.2   403.612360.15  420.04
12604.67  412.6813203.38   373.513846.99  411.54 14445.7  410.6314685.19  417.79
#Mann= 6 ,-1 , 0
       0     .05       0 7513.93      .1       0 8204.61     .06       0
 8215.96    .045       0 8345.93     .06       011683.22     .07       0
Levee=-1,7616.06,370.16,0,,,,
#XS Ineff= 2 , 0
       0 7616.06     390 10102.8       0     378
Permanent Ineff=
       F       F
Bank Sta=8215.96,8345.93
XS Rating Curve= 0 ,0
Exp/Cntr=0.3,0.1

Type RM Length L Ch R = 1 ,74927   ,1396.59,1949.18,1764.62
BEGIN DESCRIPTION:
LOB - Kaufman LID15
ROB IFA station 9544: flow contraction due to natural high ground
END DESCRIPTION:
XS GIS Cut Line= 6
2586402.023102976931905.591900562585701.455606486931572.75004657
2580747.280147396926297.253379732580582.989137386925660.03910297
 2578264.4816353 6923421.52947242574955.020078396923964.06414847
#Sta/Elev= 30
       0  432.95  507.13  419.24  1540.3  353.48 2010.11  360.78 6912.73  357.26
 7003.05  359.31 7043.04  369.48 7073.02  359.85 7257.95   357.8 8294.15  360.37
 8301.79   359.7 8371.59  343.03 8406.49  345.02 8421.44  359.65 8431.41  370.24
 9140.39  388.75 9435.19  383.51 9799.93  362.0111397.72  368.5411698.64  382.23
 11758.6  392.5611828.55  385.2111963.48  397.9912283.36  392.5212988.08  420.63
13607.84  400.1513977.69  373.4414082.65  387.3914622.44  417.05 15247.2  419.77
#Mann= 6 ,-1 , 0
       0     .05       0 6912.73      .1       0 8294.15     .06       0
 8301.79    .045       0 8431.41     .06       011397.72     .07       0
Levee=-1,7043.04,369.48,0,,,,
#XS Ineff= 2 , 0
       0 7043.04     390    9544       0     378
Permanent Ineff=
       F       F
Bank Sta=8301.79,8421.44
XS Rating Curve= 0 ,0
Exp/Cntr=0.3,0.1

Type RM Length L Ch R = 1 ,72977   ,812.59,599.81,512.27
BEGIN DESCRIPTION:
LOB - Kaufman LID15
ROB IFA station 8157: flow expansion due to natural high ground upstream
END DESCRIPTION:
XS GIS Cut Line= 4
2586402.023102976931787.536362392585870.115374136931432.29625922
2581529.340919236923958.793161652581049.317272986923751.96614748
#Sta/Elev= 30
       0  432.67  354.79  409.74  609.64  410.83 1269.46  369.28 1669.35  353.53
 1994.26  353.82 2154.21  361.46  2214.2  358.36 5693.21  360.48  5906.6  358.02
 5973.14  360.96 6003.13  368.16 6038.12  359.81 6063.11   358.2 7023.05  359.89
 7037.98  359.62 7062.84  346.99 7132.82   340.9  7197.8   342.8 7237.79  360.36
 7297.77  360.17 7332.76  366.14 7392.75   356.5 7417.74  359.78 7542.71  361.15
 8487.46  359.15 8732.41  363.49 8837.38  367.79 9396.78  410.84 9804.96  415.76
#Mann= 5 ,-1 , 0
       0     .05       0  5906.6      .1       0 7023.05     .06       0
 7037.98    .045       0 7237.79     .06       0
Levee=-1,6003.13,368.16,0,,,,
#XS Ineff= 2 , 0
       0 6003.13     390    8157       0     378
Permanent Ineff=
       F       F
Bank Sta=7037.98,7237.79
XS Rating Curve= 0 ,0
Exp/Cntr=0.3,0.1

Type RM Length L Ch R = 1 ,72378   ,1353.88,1719.75,835.38
BEGIN DESCRIPTION:
LOB - Kaufman LID15
ROB IFA station 8827: flow expansion due to natural high ground upstream
END DESCRIPTION:
XS GIS Cut Line= 3
2587608.57679223 6931849.90631642582029.768724146924041.25625131
2581101.400502136923682.52140448
#Sta/Elev= 30
       0  432.87  424.86  403.08  504.83   406.6  559.81  399.06  754.75  398.29
  789.73  404.99  809.73  398.64  861.56  399.02 1149.61   389.3 1244.58   377.6
 1524.49  366.55 2269.24   357.4 2329.22  366.66  2379.2  359.21 2744.08  354.95
 3213.93  359.85 6295.71  358.83 6362.87  358.06 6402.85  367.13 6457.84  357.83
 7914.71  360.52 7922.34  358.84 7947.33  345.05 7997.32   340.3  8042.3  342.84
 8072.29  358.91 9241.86  358.77 9486.77  368.1710178.99  412.3610592.04  415.73
#Mann= 6 ,-1 , 0
       0     .06       0  861.56     .05       0 6295.71      .1       0
 7914.71     .06       0 7922.34    .045       0 8072.29     .06       0
Levee=-1,6402.85,367.13,0,,,,
#XS Ineff= 2 , 0
       0 6402.85     390    8827       0     378
Permanent Ineff=
       F       F
Bank Sta=7922.34,8072.29
XS Rating Curve= 0 ,0
Exp/Cntr=0.3,0.1