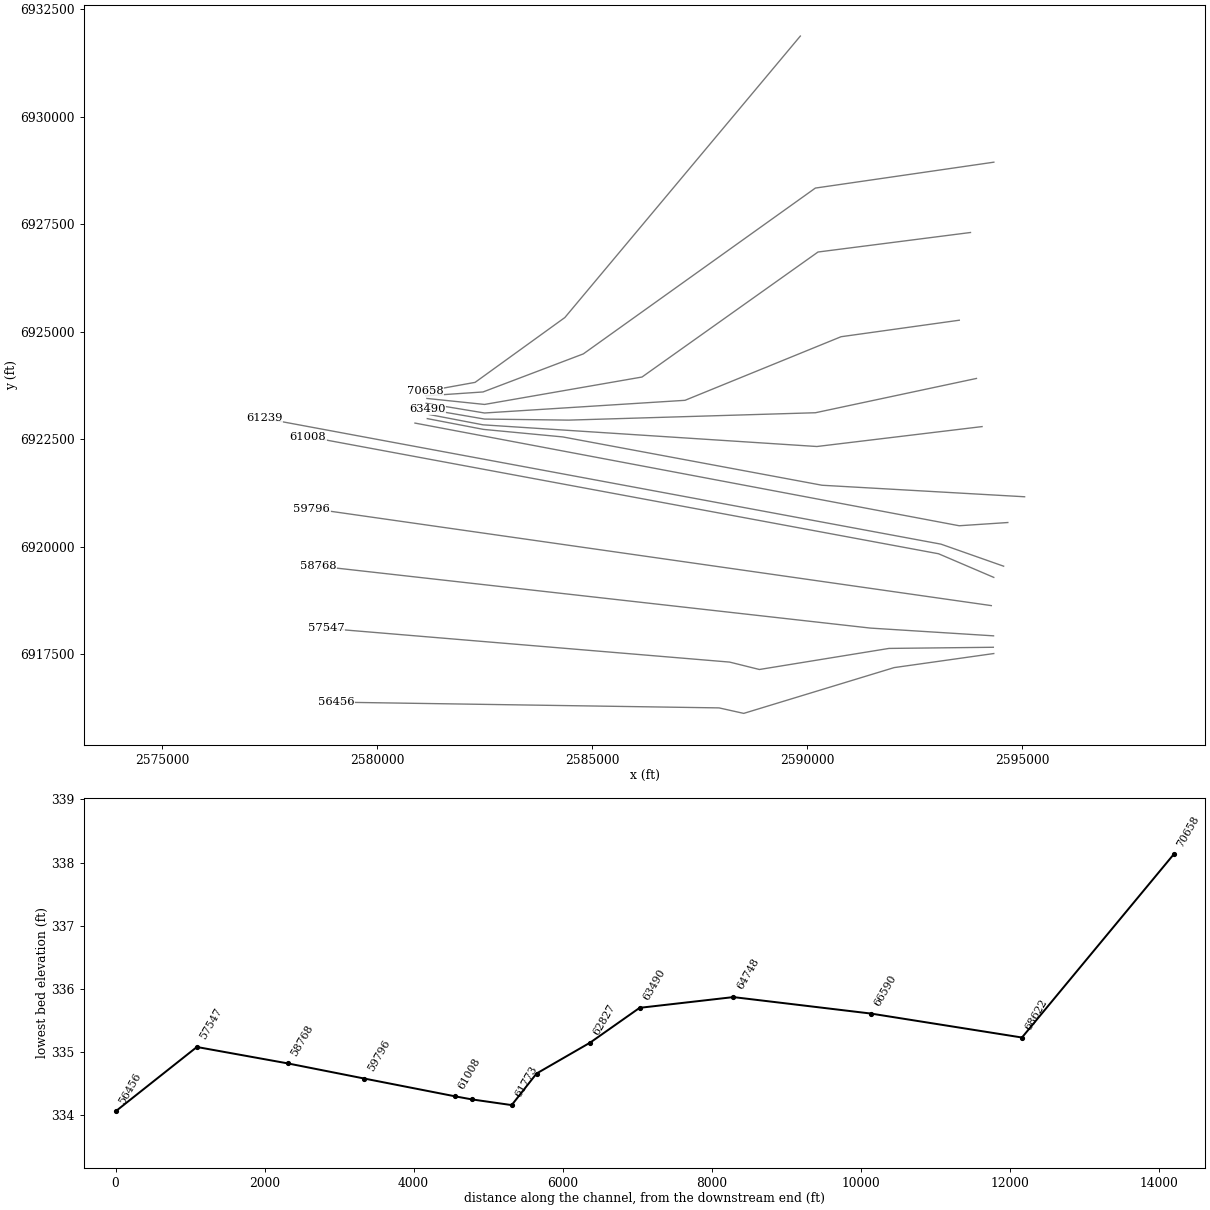
HEC-RAS study EF_FEMA.prj: East_Fork_FEMA

--- EF_FEMA.g04 (geometry) --- (continued)

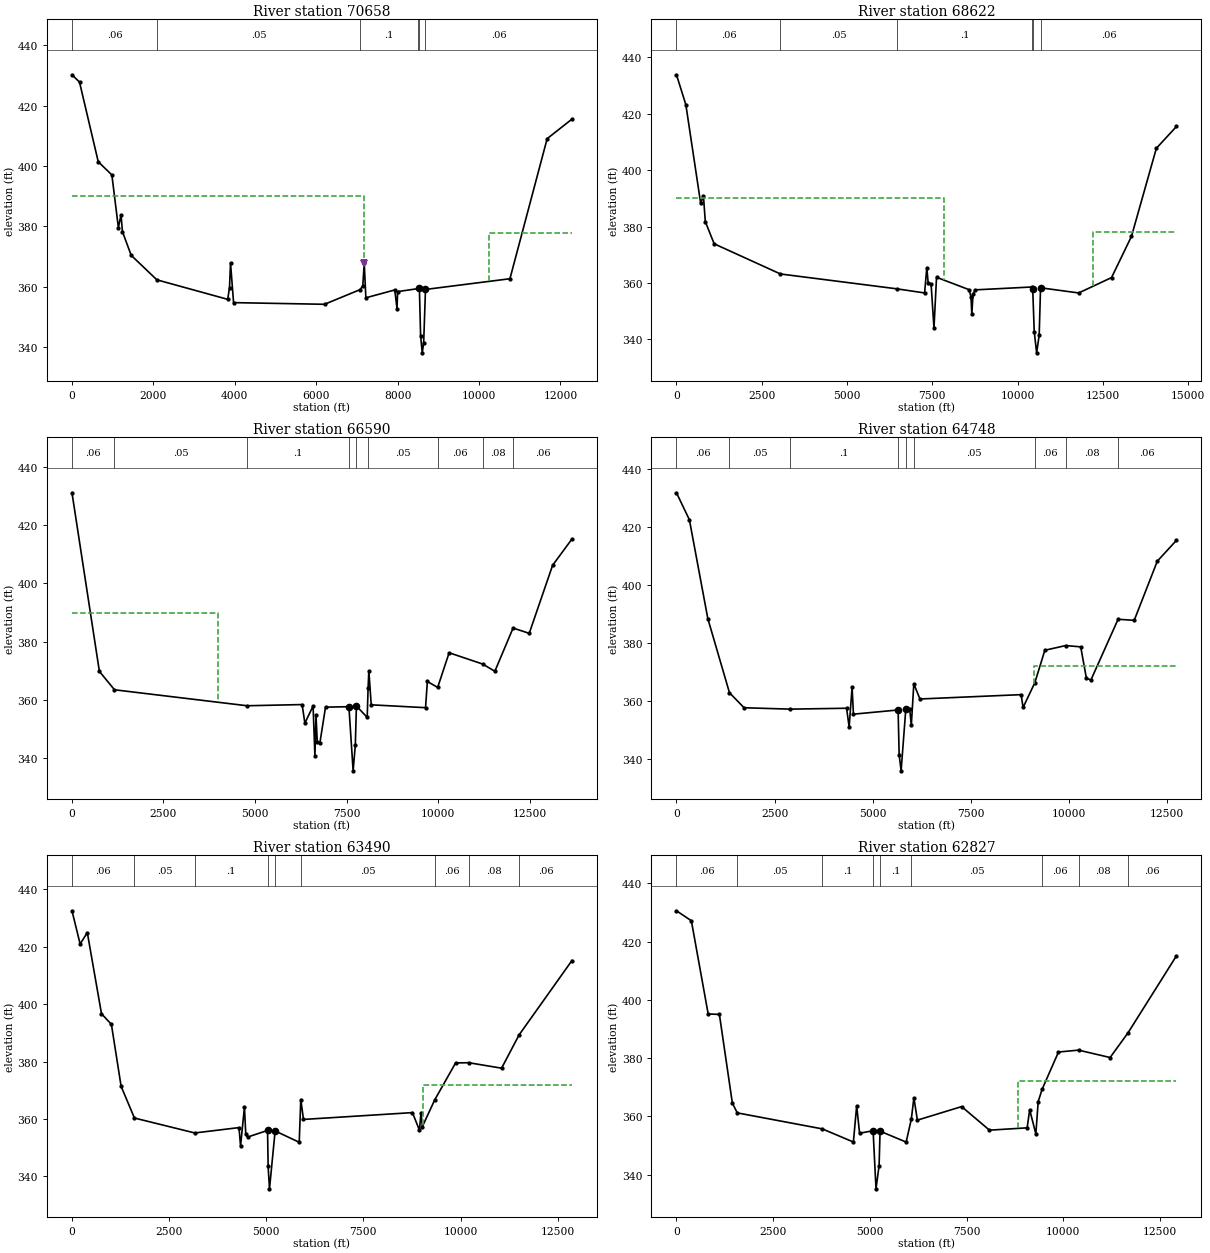
Type RM Length L Ch R = 1 ,70658   ,1805.09,2036.2,1079.67
BEGIN DESCRIPTION:
LOB - Kaufman LID15
ROB IFA station 10237: flow expansion due to natural high ground upstream
END DESCRIPTION:
XS GIS Cut Line= 4
2589837.743593726931875.947930982584361.332302476925329.66345139
2582274.02545346 6923822.32394642581118.761687896923613.07698956
#Sta/Elev= 30
       0  430.28     185  427.86  644.99  401.47  979.99  397.09 1139.99  379.62
 1204.99  383.88 1239.99  378.28 1454.99  370.44 2085.93  362.32 3824.95  355.86
 3869.95  359.66 3894.95  367.91 3969.95  354.77 6204.95  354.22 7078.08  359.08
 7144.95  360.34 7179.95  367.97 7219.95  356.37 7929.95  358.97 7984.95   352.8
 7999.95  358.42 8500.74  359.41 8534.86   359.5 8564.94  343.81 8604.93  338.13
 8639.93  341.39 8684.92  359.1410759.55  362.6911674.04  409.1112283.57  415.59
#Mann= 6 ,-1 , 0
       0     .06       0 2085.93     .05       0 7078.08      .1       0
 8500.74     .06       0 8534.86    .045       0 8684.92     .06       0
Levee=-1,7179.95,367.97,0,,,,
#XS Ineff= 2 , 0
       0 7179.95     390   10237       0     378
Permanent Ineff=
       F       F
Bank Sta=8534.86,8684.92
XS Rating Curve= 0 ,0
Exp/Cntr=0.3,0.1

Type RM Length L Ch R = 1 ,68622   ,1568.87,2031.43,1299.5
BEGIN DESCRIPTION:
LOB IFA station 7840: flow expansion due to Kaufman LID15 levee upstream
ROB IFA station 12204: flow expansion due to natural high ground upstream
END DESCRIPTION:
XS GIS Cut Line= 5
2594338.177506226928943.005306072590187.13757996 6928340.6866288
 2584791.22251886924484.626755642582458.030006726923599.30569164
2581127.442116726923508.91053122
#Sta/Elev= 30
       0  433.85  274.97  423.25  709.92  388.23  789.91     391   844.9  381.79
 1104.87   373.9 3047.63   363.2 6467.94  357.92 7273.27  356.47 7338.25  365.48
 7378.23  359.99  7463.2  359.71 7548.17  344.04 7623.14  362.03 8572.76  357.65
 8632.74  355.17 8657.73  348.83 8692.71  356.08 8762.69  357.5710429.59  358.59
10442.03  358.0410487.01  342.7910556.99  335.2310631.96  341.4910671.94   358.3
11790.18  356.4712753.49  361.9213337.47  376.5514066.76  407.7714656.18  415.51
#Mann= 6 ,-1 , 0
       0     .06       0 3047.63     .05       0 6467.94      .1       0
10429.59     .06       010442.03    .045       010671.94     .06       0
#XS Ineff= 2 , 0
       0    7840     390   12204       0     378
Permanent Ineff=
       F       F
Bank Sta=10442.03,10671.94
XS Rating Curve= 0 ,0
Exp/Cntr=0.3,0.1

Type RM Length L Ch R = 1 ,66590   ,1845.22,1842.01,825.61
BEGIN DESCRIPTION:
LOB IFA station 4000: flow expansion due to Kaufman LID15 levee upstream
END DESCRIPTION:
XS GIS Cut Line= 5
2593794.774721646927307.588629392590248.669609136926853.69485214
2586155.986521566923946.590758232582493.689384226923308.87746672
 2581153.48373136923448.14654514
#Sta/Elev= 30
       0  431.18  748.96  369.79 1161.54  363.47 4784.37  357.98 6287.38  358.39
  6362.3  352.01 6587.08  357.88 6637.03  340.84    6667  354.67 6701.97  345.36
  6771.9  345.12 6926.75   357.5 7566.11  357.66    7681  335.61 7740.94  344.51
 7770.91  357.89 8065.62  353.99 8089.95  364.14 8110.57  369.99 8175.51   358.3
  9659.4  357.32 9709.37  366.32 9990.46  364.2810303.98  376.19 11216.7  372.33
11553.15  369.8312050.78  384.69 12492.3  382.8713131.05  406.2613660.02  415.29
#Mann= 9 ,-1 , 0
       0     .06       0 1161.54     .05       0 4784.37      .1       0
 7566.11    .045       0 7770.91      .1       0 8089.95     .05       0
 9990.46     .06       0 11216.7     .08       012050.78     .06       0
#XS Ineff= 2 , 0
       0    4000     39010482.13       0     372
Permanent Ineff=
       F       F
Bank Sta=7566.11,7770.91
XS Rating Curve= 0 ,0
Exp/Cntr=0.3,0.1

Type RM Length L Ch R = 1 ,64748   ,1485.94,1258.36,388.27
XS GIS Cut Line= 5
2593534.358247736925267.657997982590784.831594566924883.80279456
2587155.986490066923404.924190642582493.076524566923110.03665707
2581136.122545566923335.29932989
#Sta/Elev= 30
       0  431.73  329.55  422.42   798.9  388.36 1350.37  362.81 1722.64  357.62
 2900.35  357.14 4335.63  357.45  4400.6  350.99 4475.58  364.62 4510.56  355.41
 5648.22  356.85 5675.12  341.43  5725.1  335.87 5845.05  357.18 5945.01  357.03
    5985   351.6 6048.89  365.87 6204.92  360.64 8783.47  362.14 8833.44  357.71
 9133.62  366.27 9388.11  377.44 9922.23  379.0610302.58  378.6110447.49  367.78
10562.42  367.1911254.62  388.1211665.99  387.7612254.09  408.1412742.51  415.34
#Mann= 9 ,-1 , 0
       0     .06       0 1350.37     .05       0 2900.35      .1       0
 5648.22    .045       0 5845.05      .1       0 6048.89     .05       0
 9133.62     .06       0 9922.23     .08       011254.62     .06       0
#XS Ineff= 2 , 0
       0                 9113.08       0     372
Permanent Ineff=
       F       F
Bank Sta=5648.22,5845.05
XS Rating Curve= 0 ,0
Exp/Cntr=0.3,0.1

Type RM Length L Ch R = 1 ,63490   ,807.88,662.89,436.52
XS GIS Cut Line= 5
2593933.663879566923913.491414982590188.802274816923115.88999181
2584451.816373476922944.351949072582493.237613476922968.49396114
2581170.844917066923196.41050006
#Sta/Elev= 30
       0  432.54  209.94  420.96  394.88  424.94  759.77  396.67  1014.7  392.98
 1264.62   371.4 1607.43  360.36 3161.18  355.16 4298.83  357.03 4338.82  350.59
 4438.81  364.14 4473.81  354.65 4518.81  353.72 5033.76  356.05 5048.76  343.51
 5083.75   335.7 5228.74  355.86 5848.68  351.92 5889.26  366.81 5958.67  359.87
 8763.46  362.25 8943.46   356.1 8983.46  362.23 9018.46  357.39 9337.22   366.7
 9873.28  379.5410209.89  379.6311057.58  377.7211507.35   389.312869.15  415.22
#Mann= 9 ,-1 , 0
       0     .06       0 1607.43     .05       0 3161.18      .1       0
 5033.76    .045       0 5228.74      .1       0 5889.26     .05       0
 9337.22     .06       010209.89     .08       011507.35     .06       0
#XS Ineff= 2 , 0
       0                 9039.74       0     372
Permanent Ineff=
       F       F
Bank Sta=5033.76,5228.74
XS Rating Curve= 0 ,0
Exp/Cntr=0.3,0.1

Type RM Length L Ch R = 1 ,62827   ,933.3,720.09,426.45
XS GIS Cut Line= 4
2594063.871952476922793.699691312590222.728059966922330.61728415
2582458.835123236922834.600528152581205.567288556923074.88252789
#Sta/Elev= 30
       0  430.59   384.9  427.17  819.78  395.17  1109.7  395.02 1444.61   364.6
 1571.64  361.22 3769.35  355.73 4573.52  351.22 4658.47  363.65 4733.42  354.24
 5083.21  355.09 5158.16  335.15 5238.11  343.15  5263.1  354.94 5937.68   351.2
 6071.76   359.1 6137.56  366.42  6227.5  358.73  7371.8  363.38 8091.36  355.29
 9065.78  356.09 9130.75  362.29 9290.65  354.01 9350.62   365.1 9454.11  369.38
 9875.31  382.1110394.37  382.7611209.53  380.22   11675  388.7412925.27  415.13
#Mann= 9 ,-1 , 0
       0     .06       0 1571.64     .05       0 3769.35      .1       0
 5083.21    .045       0  5263.1      .1       0 6071.76     .05       0
 9454.11     .06       010394.37     .08       0   11675     .06       0
#XS Ineff= 2 , 0
       0                 8824.77       0     372
Permanent Ineff=
       F       F
Bank Sta=5083.21,5263.1
XS Rating Curve= 0 ,0
Exp/Cntr=0.3,0.1

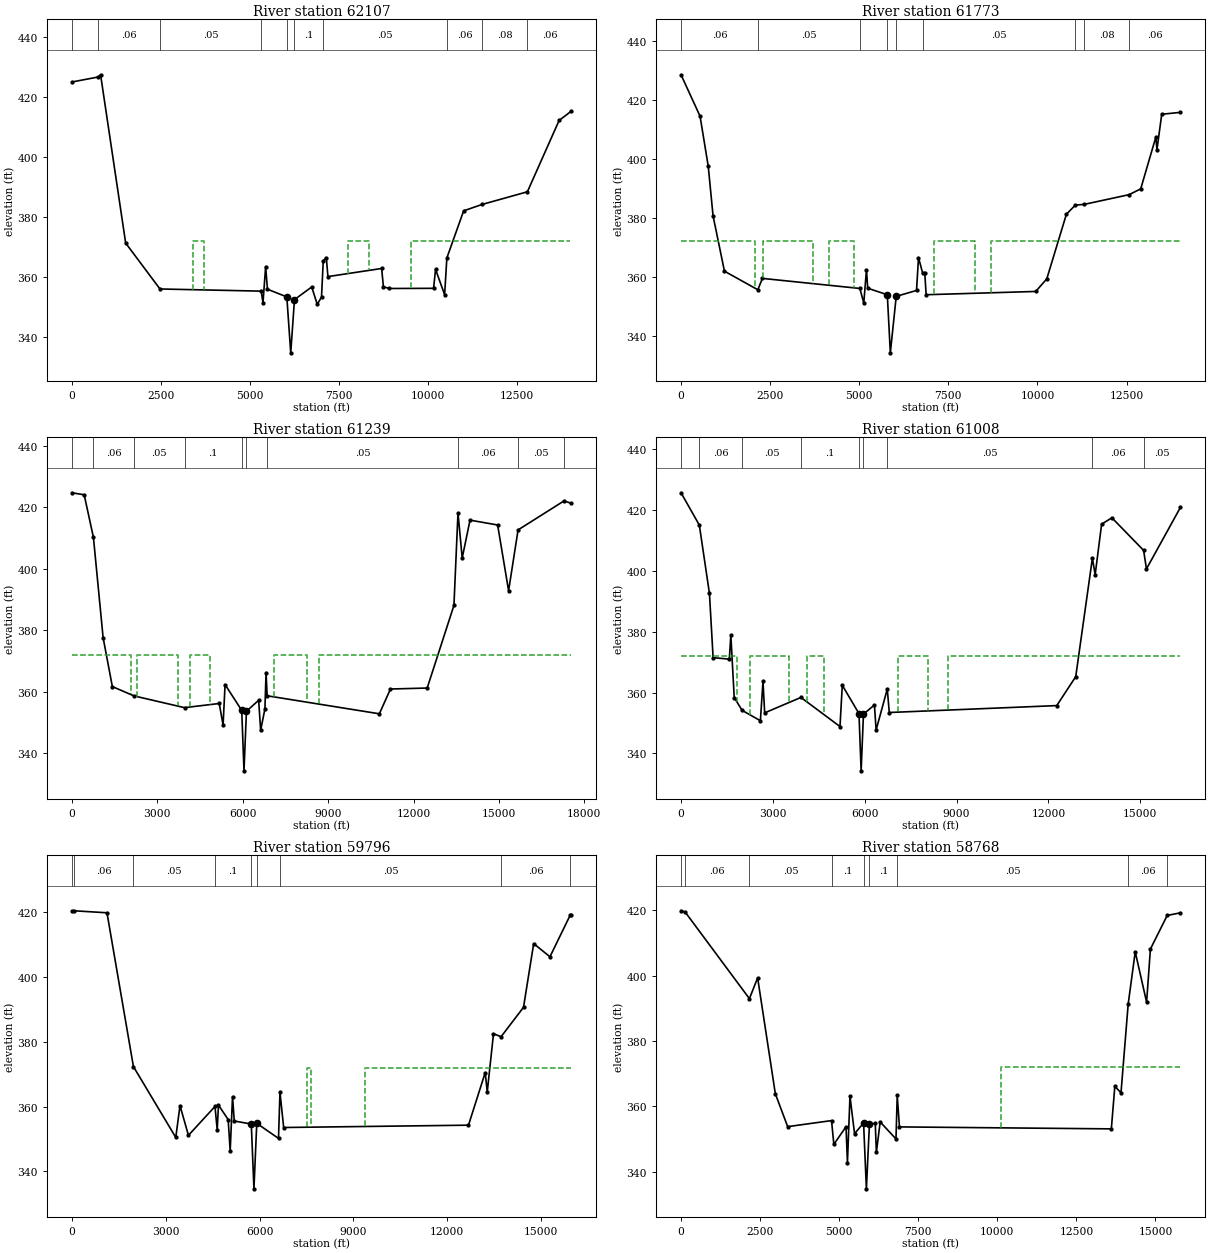
Type RM Length L Ch R = 1 ,62107   ,347.84,334.05,325.77
XS GIS Cut Line= 5
2595053.455275136921161.755120562590342.430904556921429.73555572
2584311.848149466922553.571234552582467.506693816922728.78577915
2581162.16448823 6922979.3964984
#Sta/Elev= 30
       0  424.87  732.47  426.52  804.77  427.27 1509.56  371.22 2473.35  355.93
 5318.47  355.21 5368.56  351.33 5443.56   363.4 5493.55  355.85 6038.49  353.29
 6148.48  334.66 6253.47  352.39 6738.42   356.6  6893.4  350.81 7013.39  353.24
 7062.29   365.3 7148.37  366.41 7193.37  360.05 8703.23  362.76 8753.22  356.64
 8923.21  356.0910163.13  356.1510218.12  362.48 10473.1  354.0210535.91  366.26
11007.88  381.9611525.04  384.0812799.03   388.313690.13  412.0514034.93  415.17
#Mann= 10 ,-1 , 0
       0     .05       0  732.47     .06       0 2473.35     .05       0
 5318.47      .1       0 6038.49    .045       0 6253.47      .1       0
 7062.29     .05       010535.91     .06       011525.04     .08       0
12799.03     .06       0
#XS Ineff= 3 ,-1
 3388.51 3718.61     372 7765.84 8348.32     372 9539.29   14000     372
Permanent Ineff=
       F       F       F
Bank Sta=6038.49,6253.47
XS Rating Curve= 0 ,0
Exp/Cntr=0.5,0.3

Type RM Length L Ch R = 1 ,61773   ,508.19,534.06,519.89
BEGIN DESCRIPTION:
US Bridge
ROB - Kaufman LID10
END DESCRIPTION:
XS GIS Cut Line= 3
2594662.83040021 6920562.79700092593532.223081386920487.75253156
2580875.706071636922875.23004006
#Sta/Elev= 30
       0  428.56   534.1  414.49  763.72  397.49  898.49  380.69 1218.09  361.88
 2154.83  355.58 2283.07  359.43  5018.7  356.02 5127.99  351.03 5202.99   362.4
 5237.99   356.1 5787.97  353.88 5872.96  334.16 6037.96  353.33 6607.94  355.34
 6662.93  366.49 6781.16  361.16 6837.93  361.41 6877.93  353.89 9952.87     355
10262.87  359.2910812.87  381.2211062.84   384.311319.55  384.5812573.11  387.86
12897.87  389.8313322.87  407.4113352.87  403.0813487.87  415.1614012.87   415.8
#Mann= 9 ,-1 , 0
       0     .06       0 2154.83     .05       0  5018.7      .1       0
 5787.97    .045       0 6037.96      .1       0 6781.16     .05       0
11062.84     .06       011319.55     .08       012573.11     .06       0
#XS Ineff= 5 ,-1
       0    2065     372    2295    3715     372    4140    4860     372
    7100 8257.24     372    8695   14000     372
Permanent Ineff=
       F       F       F       F       F
Bank Sta=5787.97,6037.96
XS Rating Curve= 0 ,0
Exp/Cntr=0.5,0.3

Type RM Length L Ch R = 1 ,61239   ,231.81,230.66,231.9
BEGIN DESCRIPTION:
DS Bridge
END DESCRIPTION:
XS GIS Cut Line= 3
2594565.608153726919547.172063652593109.176027226920059.67431948
2577378.631044816922982.72752848
#Sta/Elev= 30
       0  424.68  429.71  424.03  754.27  410.18 1094.27   377.6 1419.05  361.65
 2180.49  358.62 3954.08   354.8 5173.94  356.15 5308.94  349.16 5378.94   362.3
 5964.02  353.91 6043.79  334.25 6129.55  353.63 6558.94  357.19 6628.94  347.46
 6778.94   354.4 6818.94  366.23 6856.56  358.6610798.94   352.811188.94  360.86
12478.94  361.1813418.94  388.06   13561  418.1713708.94  403.4613983.94  415.78
14953.94   414.215338.94  392.8315671.59   412.617286.68  422.0417543.94  421.23
#Mann= 10 ,-1 , 0
       0     .07       0  754.27     .06       0 2180.49     .05       0
 3954.08      .1       0 5964.02    .045       0 6129.55      .1       0
 6856.56     .05       0   13561     .06       015671.59     .05       0
17286.68     .07       0
#XS Ineff= 5 ,-1
       0    2065     372    2295    3715     372    4145    4860     372
    7100    8265     372    869517543.94     372
Permanent Ineff=
       F       F       F       F       F
Bank Sta=5964.02,6129.55
XS Rating Curve= 0 ,0
Exp/Cntr=0.5,0.3

Type RM Length L Ch R = 1 ,61008   ,1142.5,1211.73,1352.69
XS GIS Cut Line= 3
2594336.441617316919286.755261642593052.01341188 6919836.3673514
2578387.745824476922559.55055331
#Sta/Elev= 30
       0  425.67   597.9  415.05  928.06  392.58 1047.81   371.5 1577.08     371
 1627.08  378.88 1737.08  358.39 1996.36  354.16 2592.07  350.77 2677.07  363.66
 2732.07  353.35 3916.25  358.42 5192.04  348.86 5267.04  362.42 5812.14  353.11
 5882.48   334.3 5958.82  352.94 6317.03  355.94 6372.03  347.71 6736.21  361.17
 6802.02  353.47   12272  355.74   12892  365.2513435.23  404.11   13527  398.79
   13737  415.33   14072  417.4615109.12  406.74   15202  400.65   16312  420.88
#Mann= 9 ,-1 , 0
       0     .07       0   597.9     .06       0 1996.36     .05       0
 3916.25      .1       0 5812.14    .045       0 5958.82      .1       0
 6736.21     .05       013435.23     .06       015109.12     .05       0
#XS Ineff= 5 ,-1
       0 1828.11     372 2264.67 3529.53     372  4104.3 4662.68     372
 7092.51 8079.34     372 8705.72   16312     372
Permanent Ineff=
       F       F       F       F       F
Bank Sta=5812.14,5958.82
XS Rating Curve= 0 ,0
Exp/Cntr=0.3,0.1

Type RM Length L Ch R = 1 ,59796   ,966.46,1028.06,1097.97
XS GIS Cut Line= 2
2594279.149737136918630.505261812578471.192179896920887.38263781
#Sta/Elev= 30
       0  420.43   63.08  420.49 1119.88  419.87 1965.58  372.35 3319.63  350.46
 3454.62  360.29 3724.59  351.11 4573.28  360.03 4644.49  352.85 4684.49  360.45
 4994.46     356 5059.45  346.36 5134.44  363.07 5189.44  355.53 5734.38  354.61
 5818.88  334.58 5909.37  354.82  6604.3  350.17 6651.09  364.47 6769.28  353.53
12678.61  354.2513213.55   370.513278.54  364.5113478.52  382.5113720.39  381.57
14438.41  390.6714763.37  410.3515283.31  406.28 15933.3  419.1815968.22  419.16
#Mann= 9 ,-1 , 0
       0     .07       0   63.08     .06       0 1965.58     .05       0
 4573.28      .1       0 5734.38    .045       0 5909.37      .1       0
 6651.09     .05       013720.39     .06       0 15933.3     .05       0
#XS Ineff= 3 ,-1
                         7501.77 7627.43     372 9368.8815968.22     372
Permanent Ineff=
       F       F       F
Bank Sta=5734.38,5909.37
XS Rating Curve= 0 ,0
Exp/Cntr=0.3,0.1

Type RM Length L Ch R = 1 ,58768   ,995.35,1220.81,1240.8
XS GIS Cut Line= 3
2594331.233294386917927.380355732591470.356470216918107.56076965
2578627.442195486919550.57724056
#Sta/Elev= 30
       0  419.81  129.38  419.44 2162.04  392.95 2422.08   399.3 2981.54  363.89
 3371.51  353.83 4758.75  355.68 4831.38  348.41 5216.35  353.81 5261.35   342.8
 5341.34  363.13 5486.33  351.67  5771.3  354.96  5860.8  334.82 5956.29  354.55
 6141.27   354.8 6176.27  345.96 6296.26  355.27 6796.21  350.07 6835.42  363.37
  6906.2  353.75 13605.3  353.1513715.28  366.1513910.25  364.1714137.73   391.3
14360.18  407.2714720.13  391.8614840.11  408.1115371.36  418.3815789.97  419.19
#Mann= 9 ,-1 , 0
       0     .07       0  129.38     .06       0 2162.04     .05       0
 4758.75      .1       0  5771.3    .045       0 5956.29      .1       0
 6835.42     .05       014137.73     .06       015371.36     .05       0
#XS Ineff= 1 ,-1
10113.3315789.97     372
Permanent Ineff=
       F
Bank Sta=5771.3,5956.29
XS Rating Curve= 0 ,0
Exp/Cntr=0.3,0.1

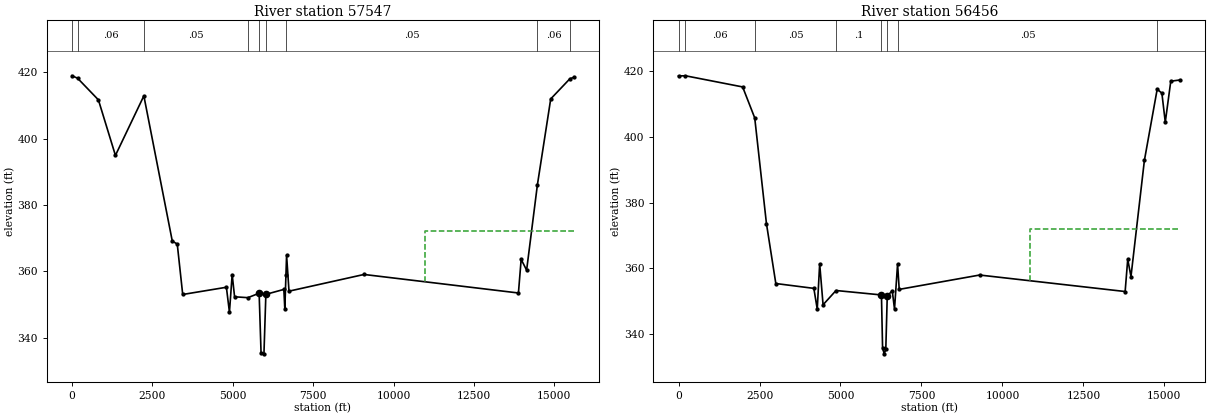
Type RM Length L Ch R = 1 ,57547   ,837.69,1091.62,1276.98
XS GIS Cut Line= 5
2594326.024971476917661.755230812591898.227989816917634.89307982
2588885.705799646917144.938679142588193.448982066917317.00920114
2578809.733825646918100.92429997
#Sta/Elev= 30
       0  418.98  171.57  418.24  819.31  411.71 1348.86  394.95 2233.37  412.92
 3117.28  369.11 3272.13   368.2 3441.97  352.99 4800.67  355.17 4895.57  347.66
 4980.49  358.98 5055.42  352.29 5469.52  352.03 5819.22  353.37 5879.08  335.35
 5968.87  335.08 6028.73  353.03  6588.2  354.52 6618.19  348.63 6653.62  358.95
 6673.17  364.84 6748.15  353.99 9082.28  359.03 13885.4  353.4413970.37  363.58
 14140.3  360.33 14476.1  386.1214890.01     41215485.07  418.0715609.73  418.52
#Mann= 9 ,-1 , 0
       0     .07       0  171.57     .06       0 2233.37     .05       0
 5469.52      .1       0 5819.22    .045       0 6028.73      .1       0
 6653.62     .05       0 14476.1     .06       015485.07     .05       0
#XS Ineff= 1 ,-1
10985.7415609.73     372
Permanent Ineff=
       F
Bank Sta=5819.22,6028.73
XS Rating Curve= 0 ,0
Exp/Cntr=0.3,0.1

Type RM Length L Ch R = 1 ,56456   ,1050.99,1649.02,1533
BEGIN DESCRIPTION:
ROB IFA station 10858: flow contraction due toKaufman 5 West levee downstream
END DESCRIPTION:
XS GIS Cut Line= 5
2594336.441617316917515.921861072592019.932142726917189.06621556
 2588521.1225393 6916124.10509092587948.01082464 6916251.7918434
2579038.787501386916385.50515865
#Sta/Elev= 30
       0  418.48  214.12  418.53 1979.53  415.14 2352.61  405.73 2714.17  373.65
 3003.95  355.42 4178.08  353.95    4283  347.63 4357.95  361.42 4462.87  348.97
 4862.76   353.3 6265.43  351.95 6300.26  335.86 6350.02  334.06 6399.78  335.47
 6444.57  351.62 6598.88  353.22 6668.84  347.66 6763.26  361.36 6813.76  353.64
 9297.36     35813789.86  352.9913869.82  362.7813969.76  357.5314384.53  392.83
14779.46  414.4414924.23  413.2515029.17  404.4415199.08  416.8815493.92  417.27
#Mann= 8 ,-1 , 0
       0     .07       0  214.12     .06       0 2352.61     .05       0
 4862.76      .1       0 6265.43    .045       0 6444.57      .1       0
 6763.26     .05       014779.46     .06       0
#XS Ineff= 1 ,-1
   1085815493.92     372
Permanent Ineff=
       F
Bank Sta=6265.43,6444.57
XS Rating Curve= 0 ,0
Exp/Cntr=0.3,0.1