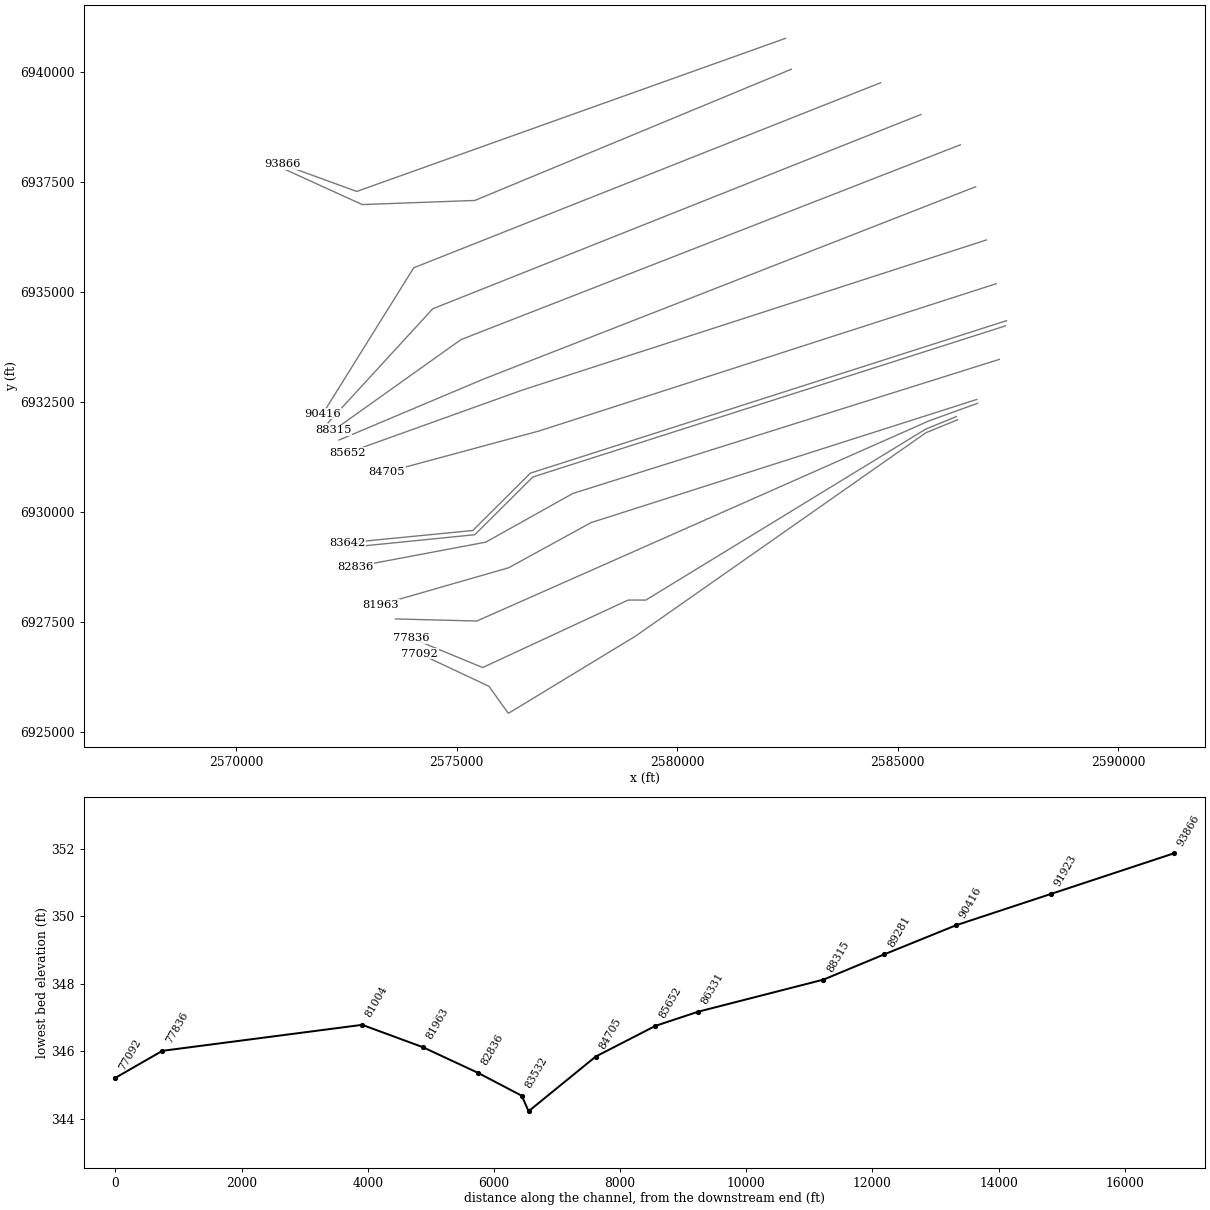
HEC-RAS study EF_FEMA.prj: East_Fork_FEMA

--- EF_FEMA.g05 (geometry) --- (continued)

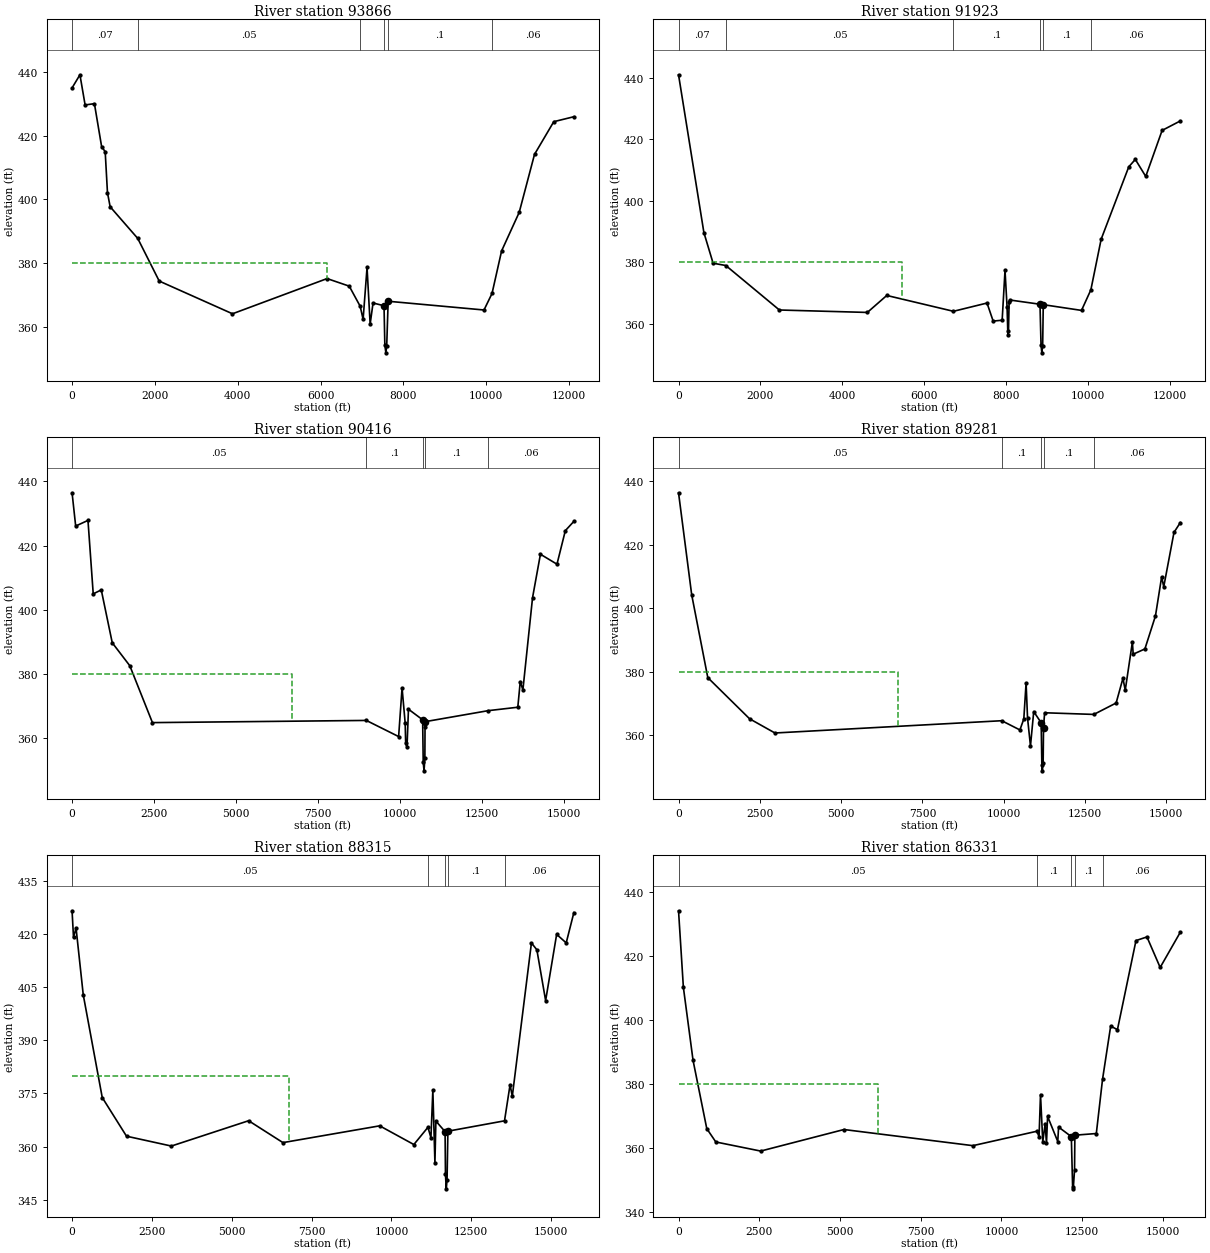
Type RM Length L Ch R = 1 ,93866   ,1064.64,1943.09,664.51
BEGIN DESCRIPTION:
LOB IFA station 6157: flow expansionn due to natural high ground upstream
END DESCRIPTION:
XS GIS Cut Line= 3
 2582456.18978736940754.897692732572731.197754386937279.81638831
2571049.507876316937892.78235398
#Sta/Elev= 30
       0  435.02  189.95  439.14  314.92  429.67  539.86  430.07  714.81   416.5
  799.78  415.03  854.77  402.14  919.75  397.71 1585.61  387.78 2104.44  374.39
 3873.96  364.12 6158.37  375.17 6693.24  372.79 6957.36  366.48 7028.15  362.38
 7123.13  378.65 7198.11  360.88 7268.09  367.51 7533.02  366.64 7553.02  354.29
 7578.01  351.86    7598     354    7633  368.05 9947.48  365.31 10141.2  370.49
10372.41  383.8510797.41  395.95 11167.4  414.16 11632.4  424.42 12117.4  425.97
#Mann= 6 ,-1 , 0
       0     .07       0 1585.61     .05       0 6957.36      .1       0
 7533.02    .045       0    7633      .1       0 10141.2     .06       0
#XS Ineff= 2 , 0
       0    6157     380               0
Permanent Ineff=
       F       F
Bank Sta=7533.02,7633
XS Rating Curve= 0 ,0
Exp/Cntr=0.3,0.1

Type RM Length L Ch R = 1 ,91923   ,989.78,1507.45,1487.6
BEGIN DESCRIPTION:
LOB IFA station 5469: flow expansionn due to natural high ground upstream
END DESCRIPTION:
XS GIS Cut Line= 4
2582588.134077226940053.508675562575408.796073726937075.24789982
2572856.712595226936981.497759222571096.296168556937783.58112881
#Sta/Elev= 30
       0  440.89  619.81  389.67  844.74  379.74 1154.81     379 2464.23  364.56
 4613.55  363.77  5088.4  369.28 6717.32  364.14 7537.66  366.82 7687.61  360.97
 7907.52  361.24 7977.49  377.41 8027.46  365.56 8047.45  356.47 8062.45  357.66
 8077.44  367.17 8092.43  367.81 8832.09  366.43 8857.08  353.27 8877.07  350.66
 8897.06  352.91 8912.05  366.29 9846.62  364.43   10075   371.1 10326.4  387.53
11001.26  411.0211161.23  413.4311416.18   407.9 11816.1  422.8412261.02  425.91
#Mann= 6 ,-1 , 0
       0     .07       0 1154.81     .05       0 6717.32      .1       0
 8832.09    .045       0 8912.05      .1       0   10075     .06       0
#XS Ineff= 2 , 0
       0    5469     380               0
Permanent Ineff=
       F       F
Bank Sta=8832.09,8912.05
XS Rating Curve= 0 ,0
Exp/Cntr=0.3,0.1

Type RM Length L Ch R = 1 ,90416   ,1035.09,1134.87,1123.78
BEGIN DESCRIPTION:
LOB IFA station 6716: flow expansionn due to natural high ground upstream
END DESCRIPTION:
XS GIS Cut Line= 3
 2584615.91184586939747.953184312574023.915641386935547.15581164
2571961.313467386932234.53579648
#Sta/Elev= 30
       0  436.45     110  426.07  484.98  427.84  644.98  404.92  889.97  406.16
 1224.96  389.67 1759.94  382.51 2449.91  364.77 8970.28  365.45 9954.86  360.42
10059.86  375.5810154.86  364.6110169.86  358.2810209.86  357.0210254.86  368.95
10687.03  365.6510704.86  352.3710729.86  349.7310754.86  353.6910759.86  363.41
10765.61  365.0712686.94   368.513588.21  369.5713663.15  377.5913743.09  374.96
14037.87  403.7614277.69  417.2814782.31  414.1815037.12  424.6415296.92  427.53
#Mann= 5 ,-1 , 0
       0     .05       0 8970.28      .1       010687.03    .045       0
10765.61      .1       012686.94     .06       0
#XS Ineff= 2 , 0
       0    6716     380               0
Permanent Ineff=
       F       F
Bank Sta=10687.03,10765.61
XS Rating Curve= 0 ,0
Exp/Cntr=0.3,0.1

Type RM Length L Ch R = 1 ,89281   ,910.58,965.47,940.73
BEGIN DESCRIPTION:
LOB IFA station 6734: flow expansionn due to natural high ground upstream
END DESCRIPTION:
XS GIS Cut Line= 3
2585525.634107726939025.730875482574455.613268816934616.69769882
 2572080.67116836932028.37282299
#Sta/Elev= 30
       0   436.3  404.86  404.21  899.68  378.18 2184.23  365.24 2963.95  360.77
 9937.83  364.6310496.17  361.7310616.13  365.18 10686.1  376.5310731.08  365.46
10821.05   356.710921.01   367.511150.26  363.9711170.91  350.7911185.91  348.87
 11210.9  351.4611222.05  362.4511255.88  367.1312769.57  366.6113454.72   370.2
 13664.6  377.9713734.56   374.213954.43  389.3413979.42  385.54 14339.2   387.2
14664.01  397.58 14853.9  409.8614918.86  406.7515233.68  423.8415428.57  426.93
#Mann= 5 ,-1 , 0
       0     .05       0 9937.83      .1       011150.26    .045       0
11222.05      .1       012769.57     .06       0
#XS Ineff= 2 , 0
       0    6734     380               0
Permanent Ineff=
       F       F
Bank Sta=11150.26,11222.05
XS Rating Curve= 0 ,0
Exp/Cntr=0.3,0.1

Type RM Length L Ch R = 1 ,88315   ,1019.33,1984.52,897.83
BEGIN DESCRIPTION:
LOB IFA station 6791: flow expansionn due to natural high ground upstream
END DESCRIPTION:
XS GIS Cut Line= 3
2586421.467617886938338.230938152575096.479113066933917.55998948
2572200.028541136931854.76162164
#Sta/Elev= 30
       0   426.5   44.99  418.99  124.97  421.65  349.92  402.83  944.78  373.86
 1704.61  362.96 3109.28  360.18  5528.7  367.32 6603.44  361.15 9632.77  365.88
10702.57  360.61 11143.8  365.4711237.46  362.5311297.45   375.911362.44  355.44
11392.43  367.2311680.33  364.2411692.37  352.2511717.37  348.1211742.36  350.61
11768.54  364.3713541.43  367.2913715.45  377.4713785.37  374.2214384.67  417.43
14554.47  415.5114829.15  401.1815173.74  419.8515473.39  417.4515713.11  425.98
#Mann= 5 ,-1 , 0
       0     .05       0 11143.8      .1       011680.33    .045       0
11768.54      .1       013541.43     .06       0
#XS Ineff= 2 , 0
       0    6791     380               0
Permanent Ineff=
       F       F
Bank Sta=11680.33,11768.54
XS Rating Curve= 0 ,0
Exp/Cntr=0.3,0.1

Type RM Length L Ch R = 1 ,86331   ,684.5,678.4,518.16
BEGIN DESCRIPTION:
LOB IFA station 6191: flow expansionn due to natural high ground upstream
END DESCRIPTION:
XS GIS Cut Line= 3
2586768.68969247 6937386.84209292575601.844900226933018.82294181
2572330.236942146931637.74761997
#Sta/Elev= 30
       0  434.04  149.95  410.13  449.84   387.3  874.69  365.98 1154.59  361.81
 2544.09  358.97 5123.21   365.7 9116.82  360.6611101.23  365.1711166.02  363.39
   11211  376.6411280.98  361.9111355.95  367.5411395.93  361.3611430.92  369.79
11745.79  361.9511770.78  366.47 12165.5  363.4912205.45  347.8812225.43  347.17
12265.38  353.1112275.37  363.9312939.61  364.4513132.21  381.38 13384.1  398.01
13593.86   396.914168.21  424.7314507.82  425.8714917.35  416.3315541.64  427.35
#Mann= 5 ,-1 , 0
       0     .05       011101.23      .1       0 12165.5    .045       0
12275.37      .1       013132.21     .06       0
#XS Ineff= 2 , 0
       0    6191     380               0
Permanent Ineff=
       F       F
Bank Sta=12165.5,12275.37
XS Rating Curve= 0 ,0
Exp/Cntr=0.3,0.1

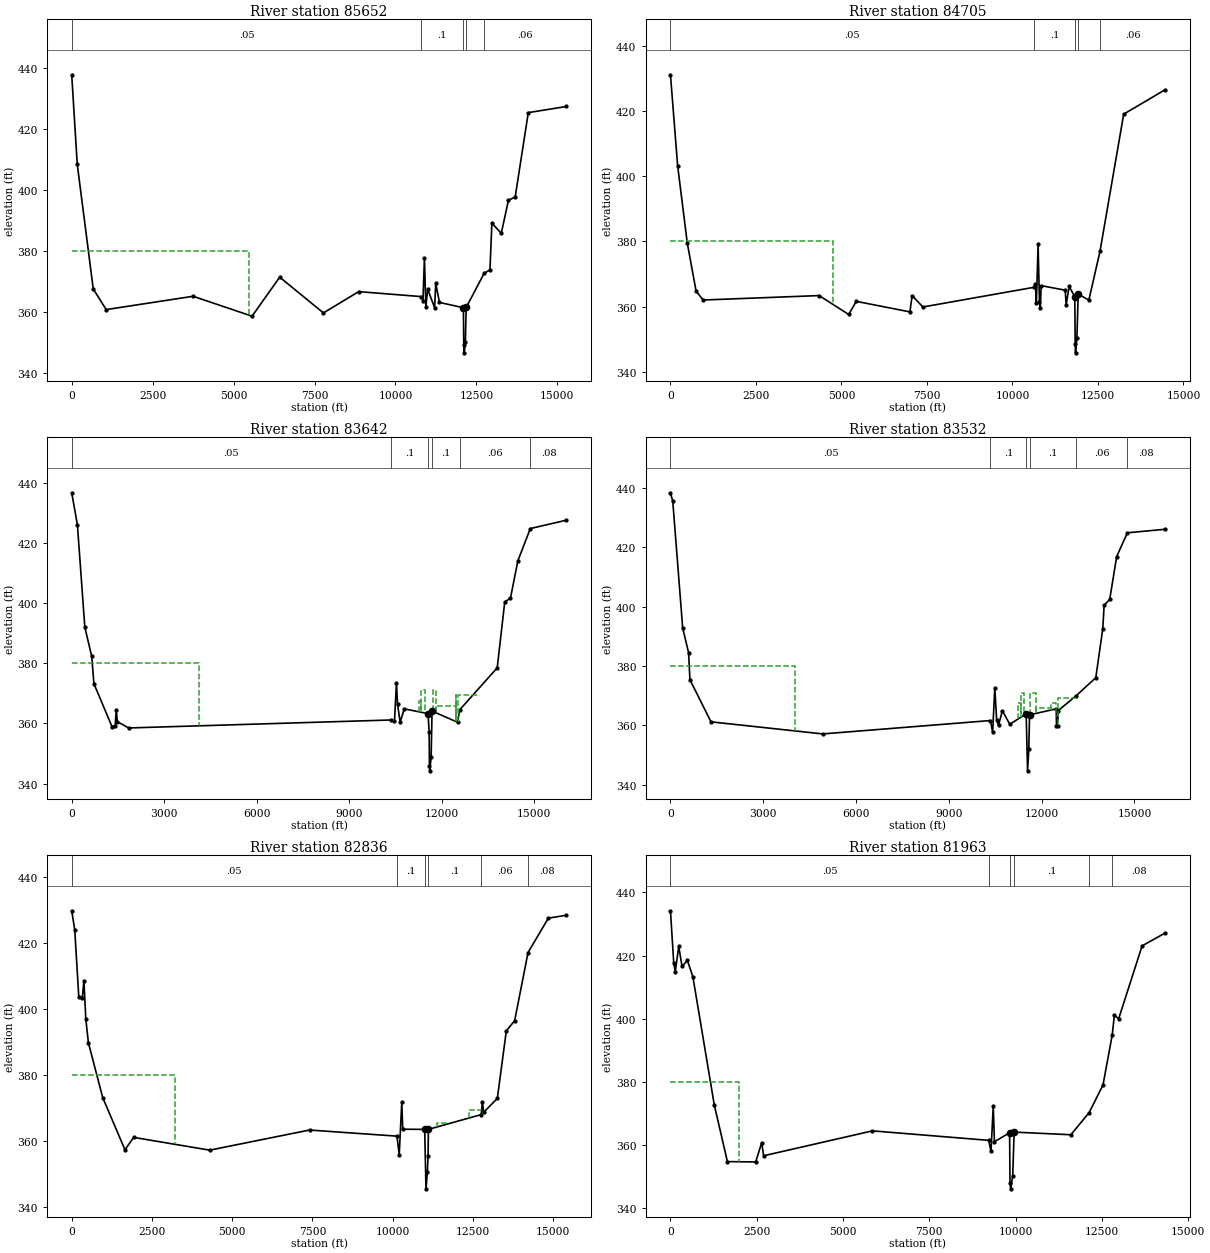
Type RM Length L Ch R = 1 ,85652   ,1013.2,947.16,954.31
BEGIN DESCRIPTION:
LOB IFA station 5474: flow expansionn due to natural high ground upstream
END DESCRIPTION:
XS GIS Cut Line= 3
2587011.745308736936178.508551572576480.14727747 6932769.2548714
2572514.698843556931344.77904581
#Sta/Elev= 30
       0  437.65  169.99  408.47  664.98  367.65 1064.97  360.89 3749.89  365.24
 5569.85  358.73 6424.83  371.48 7774.81   359.8  8864.8  366.7610794.88  365.14
 10849.8  363.73 10894.8  377.66 10939.8  361.85 10994.8  367.5711209.75  361.48
11244.73  369.4611359.69  363.23 12099.4  361.4912109.39  349.4312124.39  346.75
12159.38  350.2412184.37  361.5812738.84  372.7312919.08   373.912979.05  389.17
13268.94  385.8113488.86  396.6113698.77  397.7314103.62  425.2815283.15  427.29
#Mann= 5 ,-1 , 0
       0     .05       010794.88      .1       0 12099.4    .045       0
12184.37      .1       012738.84     .06       0
#XS Ineff= 2 , 0
       0    5474     380               0
Permanent Ineff=
       F       F
Bank Sta=12099.4,12184.37
XS Rating Curve= 0 ,0
Exp/Cntr=0.3,0.1

Type RM Length L Ch R = 1 ,84705   ,862.37,1063.63,1377.28
BEGIN DESCRIPTION:
LOB IFA station 4739: flow expansionn due to natural high ground upstream
END DESCRIPTION:
XS GIS Cut Line= 3
2587233.967633316935185.453122972576864.320065566931842.42437598
2573415.306294316930910.75137056
#Sta/Elev= 30
       0  431.11  209.91  403.22  489.78  379.65  749.67  364.75  954.58  362.04
  4348.1   363.4 5212.72   357.6 5432.62  361.63 7001.93   358.4  7066.9  363.39
 7381.77   359.910631.43  365.9410670.44  367.0410700.43  361.0910750.41  379.11
10790.39  361.3710815.38  359.6110840.38  366.4511544.97  365.0511569.95  360.52
 11659.9   366.211824.54  363.0211834.79  348.5211844.79  345.8411884.77  350.43
11924.23  363.8512234.56  362.01 12559.7  376.9213253.95  419.0414468.23  426.54
#Mann= 5 ,-1 , 0
       0     .05       010631.43      .1       011824.54    .045       0
11924.23      .1       0 12559.7     .06       0
#XS Ineff= 2 , 0
       0    4739     380               0
Permanent Ineff=
       F       F
Bank Sta=11824.54,11924.23
XS Rating Curve= 0 ,0
Exp/Cntr=0.5,0.3

Type RM Length L Ch R = 1 ,83642   ,101.77,109.11,115.85
BEGIN DESCRIPTION:
US Bridge
LOB IFA station 4139: flow expansionn due to natural high ground upstream
END DESCRIPTION:
XS GIS Cut Line= 4
2587467.995380486934346.564380812576670.911003566930886.36362407
2575365.001869986929584.878366142572512.52857231 6929303.9803059
#Sta/Elev= 30
       0   436.7  184.97  426.02  424.92     392  649.88  382.25  719.87  373.21
 1304.77  358.95 1409.75  359.27 1444.75  364.53 1479.74  360.59 1844.68  358.48
10343.22  361.1310468.19  360.6610533.18  373.5710568.17  366.2910653.16  360.46
10788.13  364.8311557.87  363.2611592.85  357.2211602.84   345.711612.84  344.22
11657.81   348.811687.79   364.112516.89  360.3712582.18   364.513800.92  378.47
14045.59  400.4214230.33  401.6214470.01  414.0414874.45   424.816047.85  427.59
#Mann= 6 ,-1 , 0
       0     .05       010343.22      .1       011557.87    .045       0
11687.79      .1       012582.18     .06       014874.45     .08       0
#XS Ineff= 7 ,-1
       0    4139     380   11250   11321   367.6   11321   11467     371
   11704   11820     371   11820   12459   365.8   12459   12477   369.4
   12518   13170   369.4
Permanent Ineff=
       F       F       F       F       F       F       F
Bank Sta=11557.87,11687.79
XS Rating Curve= 0 ,0
Exp/Cntr=0.5,0.3

Type RM Length L Ch R = 1 ,83532   ,653.52,696.01,503.42
BEGIN DESCRIPTION:
DS Bridge
LOB IFA station 4023: flow expansionn due to natural high ground upstream
END DESCRIPTION:
XS GIS Cut Line= 4
 2587443.68965486934228.508842652576724.39580472 6930798.4851909
2575410.315427636929488.856248482572540.306403896929199.81384756
#Sta/Elev= 30
       0  438.44      75  435.53  394.99  392.88  584.98  384.55  629.98   375.4
 1309.96   361.2 4924.86  357.1310344.69  361.6410414.75  357.6610484.75  372.55
10544.75  361.9510604.75  360.0210729.75  364.9510969.75  360.3811499.13   363.9
11544.01  344.6811583.91  351.8811608.85  363.5612471.65  365.5912478.85  359.96
12516.84  359.9612536.49  365.0113123.95  370.08 13749.9  376.0913974.86  392.56
14019.85  400.5214199.81  402.4614424.77  416.93 14771.4  424.9515994.46  426.14
#Mann= 6 ,-1 , 0
       0     .05       010344.69      .1       011499.13    .045       0
11608.85      .1       013123.95     .06       0 14771.4     .08       0
#XS Ineff= 7 ,-1
       0    4023     380   11250   11321   367.6   11321   11413     371
   11626   11820     371   11820   12298   365.8   12298   12475   367.6
   12518   13120   369.4
Permanent Ineff=
       F       F       F       F       F       F       F
Bank Sta=11499.13,11608.85
XS Rating Curve= 0 ,0
Exp/Cntr=0.5,0.3

Type RM Length L Ch R = 1 ,82836   ,757.82,873.74,766.88
BEGIN DESCRIPTION:
LOB IFA station 3226: flow expansionn due to natural high ground upstream
END DESCRIPTION:
XS GIS Cut Line= 4
2587304.800824976933468.092056392577635.153169566930425.75758989
2575656.730289136929319.511442812572700.028525386928762.31373832
#Sta/Elev= 30
       0  429.75   94.97  423.88  219.93  403.67   329.9  403.41  379.89  408.49
  439.87   396.8  519.84  389.69  964.71  373.07  1659.5  357.19 1929.42  360.98
 4298.74   357.1 7407.85  363.21 10133.1  361.3510201.81  355.7310281.69  371.64
10311.64  363.4610995.64   363.411035.58  345.3611080.51  350.5411100.48  355.34
11110.84  363.4112755.36  367.8912793.41  371.76 12828.4  368.5613258.23  372.79
13538.12   393.313798.02   396.414214.28  417.0614847.61  427.5215412.39  428.39
#Mann= 6 ,-1 , 0
       0     .05       0 10133.1      .1       010995.64    .045       0
11110.84      .1       012755.36     .06       014214.28     .08       0
#XS Ineff= 3 ,-1
       0    3226     380   11364   11711   365.2   12385   12770   369.4
Permanent Ineff=
       F       F       F
Bank Sta=10995.64,11110.84
XS Rating Curve= 0 ,0
Exp/Cntr=0.3,0.1

Type RM Length L Ch R = 1 ,81963   ,763.86,958.88,840.21
BEGIN DESCRIPTION:
LOB IFA station 1987: flow expansionn due to natural high ground upstream
END DESCRIPTION:
XS GIS Cut Line= 4
2586794.384194886932558.369794472578043.976170816929762.79664548
2576176.819800146928738.257684072573276.417464466927904.67470557
#Sta/Elev= 30
       0  434.18   94.96  417.62  139.94  414.95   239.9  422.89  334.86  416.56
  489.79  418.45  649.73  413.28 1269.47  372.72 1649.31  354.75 2468.96  354.63
 2643.88  360.75 2698.86  356.59 5852.56  364.48 9219.59  361.48 9286.24  357.97
 9351.23  372.32 9386.23  361.03 9825.15   363.9 9836.18  347.92 9856.17  346.12
 9916.17  350.28 9956.16  364.0911600.78  363.2512129.63  370.2812530.05  378.97
12799.39  394.91 12859.8  401.08 12984.7  399.9913664.17  423.0814333.64  427.15
#Mann= 6 ,-1 , 0
       0     .05       0 9219.59      .1       0 9825.15    .045       0
 9956.16      .1       012129.63     .06       012799.39     .08       0
#XS Ineff= 2 , 0
       0    1987     380               0
Permanent Ineff=
       F       F
Bank Sta=9825.15,9956.16
XS Rating Curve= 0 ,0
Exp/Cntr=0.3,0.1

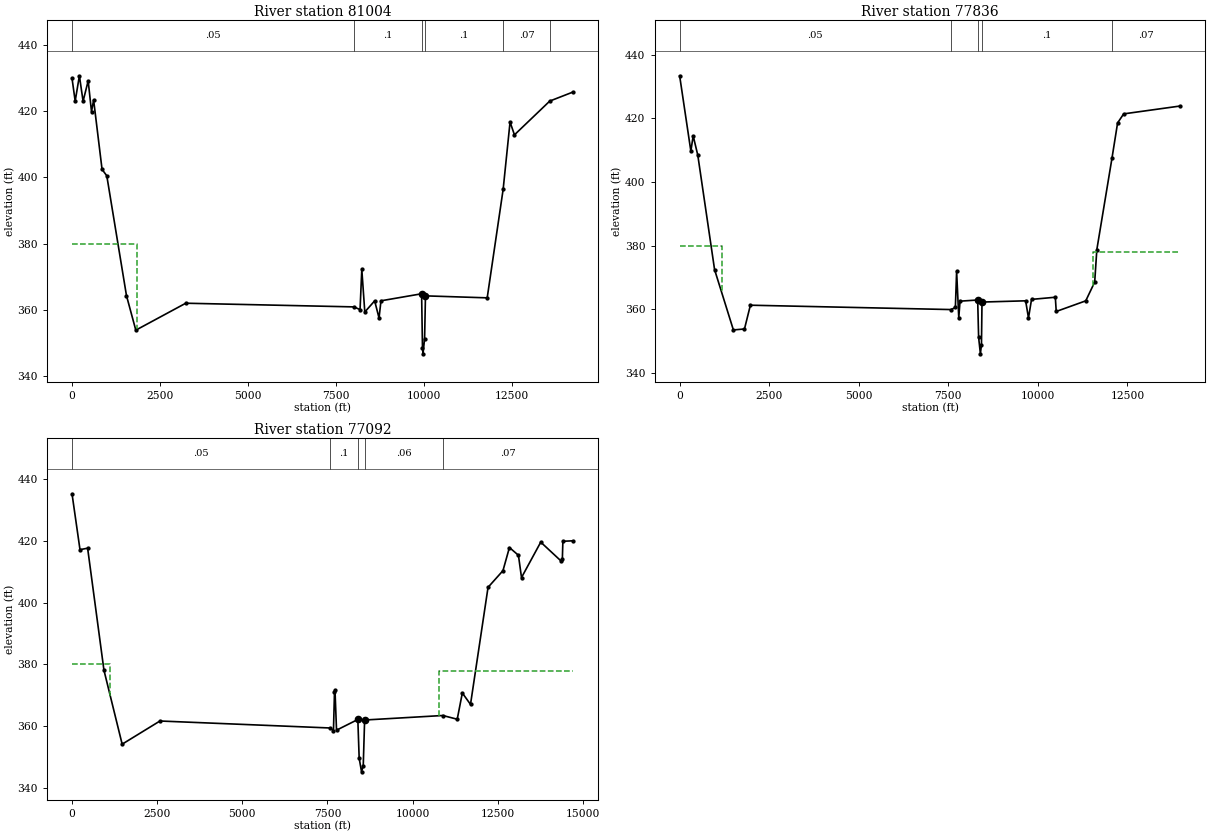
Type RM Length L Ch R = 1 ,81004   ,893.94,3167.54,1000.79
BEGIN DESCRIPTION:
LOB IFA station 1850: flow expansionn due to natural high ground upstream
END DESCRIPTION:
XS GIS Cut Line= 4
2586811.745380646932471.564193822585703.914591066932070.11224081
2575455.980690646927529.815219062573609.533924226927577.34563582
#Sta/Elev= 30
       0  429.93   89.87  423.01   209.7  430.66  314.55  422.98  459.35  429.14
  554.21  419.83  614.13  423.35  853.79  402.43  988.59  400.49 1548.28  364.33
 1813.24  353.92 3233.08  362.05 8018.91  360.94 8187.58  360.11 8237.57  372.23
 8322.56   359.4 8602.51  362.76 8727.49  357.59 8782.48  362.78 9937.27   364.9
 9962.27   348.6 9977.26  346.7810022.26  351.3310047.25  364.2711801.94  363.67
12255.38   396.412451.74  416.7112576.54  412.8413580.55  423.0314233.95  425.73
#Mann= 6 ,-1 , 0
       0     .05       0 8018.91      .1       0 9937.27    .045       0
10047.25      .1       012255.38     .07       013580.55     .08       0
#XS Ineff= 2 , 0
       0    1850     380               0
Permanent Ineff=
       F       F
Bank Sta=9937.27,10047.25
XS Rating Curve= 0 ,0
Exp/Cntr=0.3,0.1

Type RM Length L Ch R = 1 ,77836   ,308.65,744.14,1041.53
BEGIN DESCRIPTION:
LOB IFA station 1177: flow expansionn due to natural high ground upstream
END DESCRIPTION:
XS GIS Cut Line= 6
2586329.106582146932169.480808482585634.53480855 6931884.9669418
2579288.946777976928005.586577222578886.169040226928005.58657722
2575587.846568636926473.917724562573967.606698896927143.31763248
#Sta/Elev= 30
       0  433.37  313.16  409.69  377.78   414.5  507.02  408.41  975.51  372.46
 1500.33  353.52 1810.23  353.82 1975.17  361.29 7574.07  359.92 7698.24  360.57
 7733.23  371.94 7793.21  357.31  7828.2  362.56 8321.11  362.92 8347.21   351.2
 8396.93  346.01 8426.77  348.88 8441.69  362.28 9659.82  362.67 9739.74  357.27
 9824.66  363.1210489.01  363.7910513.99  359.3211338.18  362.6611587.94  368.56
11647.88  378.7712069.63  407.4112227.31  418.5612397.11   421.413980.25  423.88
#Mann= 5 ,-1 , 0
       0     .05       0 7574.07      .1       0 8321.11    .045       0
 8441.69      .1       012069.63     .07       0
#XS Ineff= 2 , 0
       0    1177     380   11533       0     378
Permanent Ineff=
       F       F
Bank Sta=8321.11,8441.69
XS Rating Curve= 0 ,0
Exp/Cntr=0.3,0.1

Type RM Length L Ch R = 1 ,77092   ,943.98,1276.8,1378.67
BEGIN DESCRIPTION:
LOB IFA station 1121: flow expansionn due to natural high ground upstream
END DESCRIPTION:
XS GIS Cut Line= 6
2586356.884085646932096.56428765 2585642.12042336931804.04846847
2579052.835701636927186.142349972576169.750588556925433.65865023
2575728.610722816926049.683008732574162.919300396926785.24485782
#Sta/Elev= 30
       0  435.19  234.18  417.11   458.4  417.58  937.29  378.12 1472.24  354.16
 2582.12  361.66 7580.45   359.4 7676.66  358.53 7706.66  370.91 7721.65  371.63
 7766.65  358.69 8392.23  362.15 8431.57  349.61 8501.55  345.21 8551.53  347.26
 8591.52  361.9810888.78  363.4411310.65  362.23 11460.6  370.7311700.52  367.03
12215.35  404.9112653.98  410.3212843.39   417.813107.97  415.2913197.97  408.08
13762.92  419.5414362.87   413.414397.87  414.1914412.87  419.8214702.85  419.97
#Mann= 5 ,-1 , 0
       0     .05       0 7580.45      .1       0 8392.23    .045       0
 8591.52     .06       010888.78     .07       0
#XS Ineff= 2 , 0
       0    1121     380 10783.6       0     378
Permanent Ineff=
       F       F
Bank Sta=8392.23,8591.52
XS Rating Curve= 0 ,0
Exp/Cntr=0.3,0.1