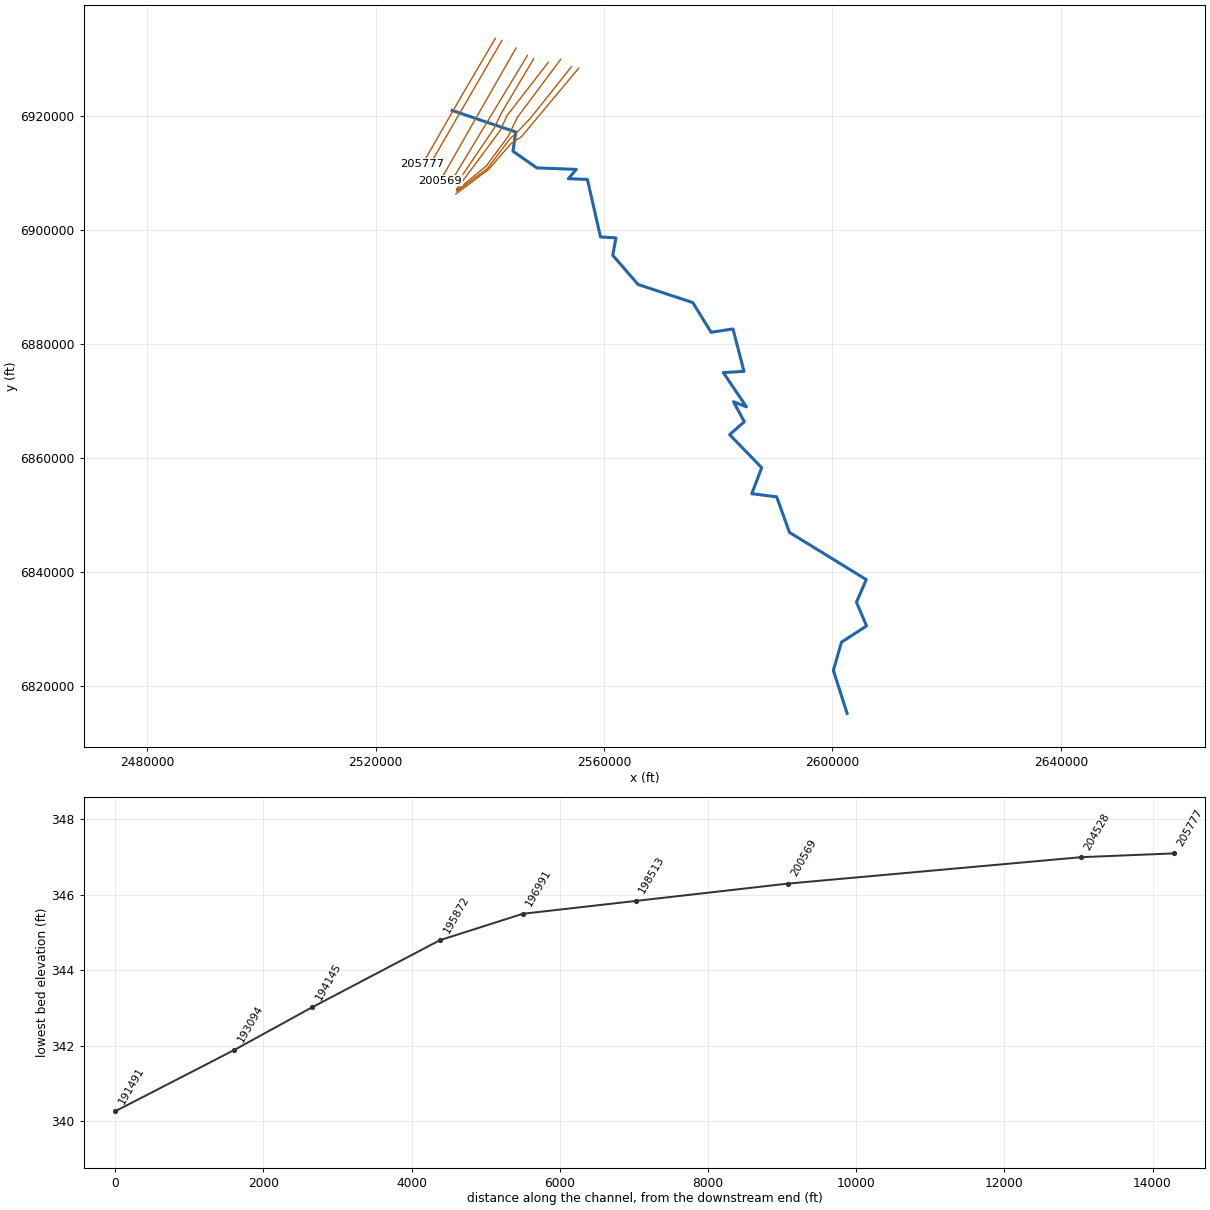
HEC-RAS study TR_FEMA.prj: Trinity_River_FEMA

--- TR_FEMA.f08 (steady flow) ---

Flow Title=2020 BoisDArc Reduced Discharges
Program Version=5.06
BEGIN FILE DESCRIPTION:
Full discharges through Bois D'Arc Levee with reduced discharges elsewhere based on With Levee supplemental model that used lateral structures to represent levees
Boundary condition - Known WS based on With Levee supplemental model
END FILE DESCRIPTION:
Number of Profiles= 7
Profile Names=10yr,25yr,50yr,100yr,500yr,1PCT_MINUS,1PCT_PLUS
River Rch & RM=Trinity River,1               ,205777
   50100   75100   95700  120200  185200   87400  193600
River Rch & RM=Trinity River,1               ,200569
   50100   75091   94845  117604  177387   87001  184767
River Rch & RM=Trinity River,1               ,198513
   50100   75059   94005  115435  171504   86543  178140
River Rch & RM=Trinity River,1               ,196991
   50100   74828   93020  113486  167115   85860  173248
River Rch & RM=Trinity River,1               ,195872
   50100   74766   92518  112383  164541   85541  170364
River Rch & RM=Trinity River,1               ,194145
   50100   74649   91729  110743  160793   85020  166172
River Rch & RM=Trinity River,1               ,193094
   50100   75100   95700  120200  185200   87400  193600
River Rch & RM=Trinity River,1               ,191491
   50100   75100   95700  120200  185200   87400  193600
River Rch & RM=Trinity River,1               ,189380
   50100   75100   95700  120200  185200   87400  193600
River Rch & RM=Trinity River,1               ,187750
   50100   75100   95700  120200  185200   87400  193600
River Rch & RM=Trinity River,1               ,186516
   50100   75100   95700  120200  185200   87400  193600
River Rch & RM=Trinity River,1               ,186264
   50100   75100   95700  120200  185200   87400  193600
River Rch & RM=Trinity River,1               ,184503
   50100   75100   95700  120200  185200   87400  193600
River Rch & RM=Trinity River,1               ,181750
   50100   75100   95700  120200  185200   87400  193600
River Rch & RM=Trinity River,1               ,179572
   50100   75100   95700  120200  185200   87400  193600
River Rch & RM=Trinity River,1               ,178698
   50100   75100   95700  120200  185200   87400  193600
River Rch & RM=Trinity River,1               ,176021
   44300   66300   86400  108900  166400   80600  171100
River Rch & RM=Trinity River,1               ,172483
   44300   66300   86400  108900  166400   80600  171100
River Rch & RM=Trinity River,1               ,169025
   44300   66300   86400  108900  166400   80600  171100
River Rch & RM=Trinity River,1               ,167085
   44300   66300   86400  108900  166400   80600  171100
River Rch & RM=Trinity River,1               ,165454
   44300   66300   86400  108900  166400   80600  171100
River Rch & RM=Trinity River,1               ,165204
   44300   66300   86400  108900  166400   80600  171100
River Rch & RM=Trinity River,1               ,164199
   44300   66300   86400  108900  166400   80600  171100
River Rch & RM=Trinity River,1               ,162832
   44300   66300   86400  108900  166400   80600  171100
River Rch & RM=Trinity River,1               ,161707
   44300   66300   86400  108900  166400   80600  171100
River Rch & RM=Trinity River,1               ,159456
   44300   66300   86400  108900  166400   80600  171100
River Rch & RM=Trinity River,1               ,157344
   44300   66300   86400  108900  166400   80600  171100
River Rch & RM=Trinity River,1               ,154267
   44700   67000   87100  109800  167700   81200  172800
River Rch & RM=Trinity River,1               ,151264
   44700   67000   87100  109800  167700   81200  172800
River Rch & RM=Trinity River,1               ,148768
   44700   67000   87100  109800  167700   81200  172800
River Rch & RM=Trinity River,1               ,147333
   44700   67000   87100  109800  167700   81200  172800
River Rch & RM=Trinity River,1               ,145717
   44700   67000   87100  109800  167700   81200  172800
River Rch & RM=Trinity River,1               ,143893
   44700   67000   87100  109800  167700   81200  172800
River Rch & RM=Trinity River,1               ,141890
   44700   67000   87100  109800  167700   81200  172800
River Rch & RM=Trinity River,1               ,139225
   44700   67000   87100  109800  167700   81200  172800
River Rch & RM=Trinity River,1               ,137179
   44700   67000   87100  109800  167700   81200  172800
River Rch & RM=Trinity River,1               ,135104
   44700   67000   87100  109800  167700   81200  172800
River Rch & RM=Trinity River,1               ,133245
   44700   67000   87100  109800  167700   81200  172800
River Rch & RM=Trinity River,1               ,131382
   44700   67000   87100  109800  167700   81200  172800
River Rch & RM=Trinity River,1               ,129561
   44700   67000   87100  109800  167700   81200  172800
River Rch & RM=Trinity River,1               ,127110
   44700   67000   87100  109800  167700   81200  172800
River Rch & RM=Trinity River,1               ,124996
   44700   67000   87100  109800  167700   81200  172800
River Rch & RM=Trinity River,1               ,123554
   44700   67000   87100  109800  167700   81200  172800
River Rch & RM=Trinity River,1               ,122155
   44700   67000   87100  109800  167700   81200  172800
River Rch & RM=Trinity River,1               ,120905
   44700   67000   87100  109800  167700   81200  172800
River Rch & RM=Trinity River,1               ,118211
   44700   67000   87100  109800  167700   81200  172800
River Rch & RM=Trinity River,1               ,116211
   44700   67000   87100  109800  167700   81200  172800
River Rch & RM=Trinity River,1               ,113969
   40000   62600   81000  105400  160900   79100  162800
River Rch & RM=Trinity River,1               ,112556
   40000   62600   81000  105400  160900   79100  162800
River Rch & RM=Trinity River,1               ,110130
   40000   62600   81000  105400  160900   79100  162800
River Rch & RM=Trinity River,1               ,108725
   40000   62600   81000  105400  160900   79100  162800
River Rch & RM=Trinity River,1               ,107532
   40000   61291   71262   79394   83402   72131   84529
River Rch & RM=Trinity River,1               ,104348
   40000   62008   73422   84781  106737   73589  109056
River Rch & RM=Trinity River,1               ,96265
   40000   62005   73273   83325   99225   73526  101078
River Rch & RM=Trinity River,1               ,95077
   40000   62005   73246   82957   97670   73518   99415
River Rch & RM=Trinity River,1               ,91978
   40000   62000   73037   82047   94619   73393   96168
River Rch & RM=Trinity River,1               ,83613
   56100   86267  102499  115869  147207   98335  150100
River Rch & RM=Trinity River,1               ,80593
   56100   86297  103199  118346  156321   98860  159388
River Rch & RM=Trinity River,1               ,76398
   56100   86297  102909  117395  153572   98669  156563
River Rch & RM=Trinity River,1               ,74608
   56100   86900  110479  138421  209309  104114  212555
River Rch & RM=Trinity River,1               ,72672
   56100   86896  109963  137070  205824  103731  208981
River Rch & RM=Trinity River,1               ,71053
   56100   86861  109210  135335  201676  103136  204734
River Rch & RM=Trinity River,1               ,68028
   56100   86838  108124  132522  192141  102287  194934
River Rch & RM=Trinity River,1               ,65984
   56100   86836  107011  129170  182626  101459  185223
River Rch & RM=Trinity River,1               ,64637
   56100   86834  106583  127365  176781  101167  179271
River Rch & RM=Trinity River,1               ,62238
   56100   86831  105966  125051  169878  100728  172248
River Rch & RM=Trinity River,1               ,59702
   56100   86800  104338  120222  156737   99453  158935
River Rch & RM=Trinity River,1               ,56823
   56100   86800  103899  118920  152495   99098  154591
River Rch & RM=Trinity River,1               ,55303
   56100   86800  103899  118888  151146   99098  153198
River Rch & RM=Trinity River,1               ,53117
   56100   86875  109244  131796  181011  103218  183863
River Rch & RM=Trinity River,1               ,51036
   56100   86875  109005  130576  176441  103046  179203
River Rch & RM=Trinity River,1               ,48916
   51600   78575  102701  126168  167459  100774  168767
River Rch & RM=Trinity River,1               ,46568
   51600   78575  102301  123596  159545  100474  160751
River Rch & RM=Trinity River,1               ,45073
   51600   78575  101772  121544  154452  100036  155579
River Rch & RM=Trinity River,1               ,44793
   51600   78575  101772  121544  154452  100036  155579
River Rch & RM=Trinity River,1               ,43746
   51600   78575  101397  120399  151548   99708  152598
River Rch & RM=Trinity River,1               ,42372
   51600   78403   99736  117205  145757   98179  146712
River Rch & RM=Trinity River,1               ,39787
   51600   78400   99218  115868  142484   97711  143359
River Rch & RM=Trinity River,1               ,38724
   51600   78375   98359  113963  138763   96928  139570
River Rch & RM=Trinity River,1               ,37337
   51600   78266   97508  112342  135723   96140  136463
River Rch & RM=Trinity River,1               ,35159
   51600   77976   96109  109477  130089   94854  130684
River Rch & RM=Trinity River,1               ,32786
   51600   77976   96085  109217  128917   94838  129436
River Rch & RM=Trinity River,1               ,30239
   51600   77976   95951  108396  126459   94736  126840
River Rch & RM=Trinity River,1               ,28041
   51600   77976   95899  107960  124932   94696  125230
River Rch & RM=Trinity River,1               ,26191
   51600   77975   95621  106827  121908   94467  122064
River Rch & RM=Trinity River,1               ,24046
   51600   77975   95591  106502  120583   94451  120641
River Rch & RM=Trinity River,1               ,19761
   51600   77975   95591  106502  120357   94451  120374
River Rch & RM=Trinity River,1               ,17358
   51600   77975   95488  105875  118183   94379  118115
River Rch & RM=Trinity River,1               ,15600
   51600   77975   95488  105768  116821   94379  116665
River Rch & RM=Trinity River,1               ,13539
   51600   77975   95488  105742  116296   94379  116118
River Rch & RM=Trinity River,1               ,11371
   51600   78600  104501  133942  196620  102015  198170
River Rch & RM=Trinity River,1               ,9505
   51600   78600  104500  133677  195527  102015  197064
River Rch & RM=Trinity River,1               ,7604
   51600   78600  104500  133585  194701  102015  196225
River Rch & RM=Trinity River,1               ,6288
   51600   78600  104500  133542  194157  102015  195673
Boundary for River Rch & Prof#=Trinity River,1               , 1
Up Type= 0
Dn Type= 1
Dn Known WS=322.4
Boundary for River Rch & Prof#=Trinity River,1               , 2
Up Type= 0
Dn Type= 1
Dn Known WS=325.55
Boundary for River Rch & Prof#=Trinity River,1               , 3
Up Type= 0
Dn Type= 1
Dn Known WS=327.49
Boundary for River Rch & Prof#=Trinity River,1               , 4
Up Type= 0
Dn Type= 1
Dn Known WS=329.3
Boundary for River Rch & Prof#=Trinity River,1               , 5
Up Type= 0
Dn Type= 1
Dn Known WS=332.4
Boundary for River Rch & Prof#=Trinity River,1               , 6
Up Type= 0
Dn Type= 1
Dn Known WS=327.32
Boundary for River Rch & Prof#=Trinity River,1               , 7
Up Type= 0
Dn Type= 1
Dn Known WS=332.47
DSS Import GetInterval= 0
DSS Import GetPeak= 0
DSS Import FillOption= 0

--- TR_FEMA.f09 (steady flow) ---

Flow Title=2020 DAlLID1LID2 Reduced Discharges
Program Version=5.06
BEGIN FILE DESCRIPTION:
Full discharges through Dallas LID1/Dallas LID2 with reduced discharges elsewhere based on With Levee supplemental model that used lateral structures to represent levees
Boundary condition - Known WS based on With Levee supplemental model
END FILE DESCRIPTION:
Number of Profiles= 7
Profile Names=10yr,25yr,50yr,100yr,500yr,1PCT_MINUS,1PCT_PLUS
River Rch & RM=Trinity River,1               ,205777
   50100   75100   95700  120200  185200   87400  193600
River Rch & RM=Trinity River,1               ,200569
   50100   75100   95700  120200  185200   87400  193600
River Rch & RM=Trinity River,1               ,198513
   50100   75100   95700  120200  185200   87400  193600
River Rch & RM=Trinity River,1               ,196991
   50100   75100   95700  120200  185200   87400  193600
River Rch & RM=Trinity River,1               ,195872
   50100   75100   95700  120200  185200   87400  193600
River Rch & RM=Trinity River,1               ,194145
   50100   75100   95700  120200  185200   87400  193600
River Rch & RM=Trinity River,1               ,193094
   50100   75100   95700  120200  185200   87400  193600
River Rch & RM=Trinity River,1               ,191491
   50100   75100   95700  120200  185200   87400  193600
River Rch & RM=Trinity River,1               ,189380
   50100   75100   95700  120200  185200   87400  193600
River Rch & RM=Trinity River,1               ,187750
   50100   75100   95700  120200  185200   87400  193600
River Rch & RM=Trinity River,1               ,186516
   50100   75100   95700  120200  185200   87400  193600
River Rch & RM=Trinity River,1               ,186264
   50100   75100   95700  120200  185200   87400  193600
River Rch & RM=Trinity River,1               ,184503
   50100   75100   95700  120200  185200   87400  193600
River Rch & RM=Trinity River,1               ,181750
   50100   75100   95700  120200  185200   87400  193600
River Rch & RM=Trinity River,1               ,179572
   50100   75100   95700  120200  185200   87400  193600
River Rch & RM=Trinity River,1               ,178698
   50100   75100   95700  120200  185200   87400  193600
River Rch & RM=Trinity River,1               ,176021
   44300   66300   86400  108900  166400   80600  171100
River Rch & RM=Trinity River,1               ,172483
   44300   66300   86400  108900  166400   80600  171100
River Rch & RM=Trinity River,1               ,169025
   44300   66300   86400  108900  166400   80600  171100
River Rch & RM=Trinity River,1               ,167085
   44300   66300   86400  108900  166400   80600  171100
River Rch & RM=Trinity River,1               ,165454
   44300   66300   86400  108900  166400   80600  171100
River Rch & RM=Trinity River,1               ,165204
   44300   66300   86400  108900  166400   80600  171100
River Rch & RM=Trinity River,1               ,164199
   44300   66300   86400  108900  166400   80600  171100
River Rch & RM=Trinity River,1               ,162832
   44300   66300   86400  108900  166400   80600  171100
River Rch & RM=Trinity River,1               ,161707
   44300   66300   86400  108900  166400   80600  171100
River Rch & RM=Trinity River,1               ,159456
   44300   66300   86400  108900  166400   80600  171100
River Rch & RM=Trinity River,1               ,157344
   44300   66300   86400  108900  166400   80600  171100
River Rch & RM=Trinity River,1               ,154267
   44700   67000   87100  109800  167700   81200  172800
River Rch & RM=Trinity River,1               ,151264
   44700   67000   87100  109800  167700   81200  172800
River Rch & RM=Trinity River,1               ,148768
   44700   64260   72094   75646   76784   70858   75808
River Rch & RM=Trinity River,1               ,147333
   44700   66256   84088  101796  139875   79117  142868
River Rch & RM=Trinity River,1               ,145717
   44700   66228   83478  100066  134896   78712  137782
River Rch & RM=Trinity River,1               ,143893
   44700   66210   82907   98353  130099   78365  132907
River Rch & RM=Trinity River,1               ,141890
   44700   66207   82210   96461  125161   77933  127939
River Rch & RM=Trinity River,1               ,139225
   44700   66193   81673   95114  121844   77576  124666
River Rch & RM=Trinity River,1               ,137179
   44700   66182   81303   94221  119519   77320  122422
River Rch & RM=Trinity River,1               ,135104
   44700   66070   80442   92323  114967   76661  118012
River Rch & RM=Trinity River,1               ,133245
   44700   66070   80212   91574  112562   76521  115753
River Rch & RM=Trinity River,1               ,131382
   44700   66070   80113   91110  110670   76464  114010
River Rch & RM=Trinity River,1               ,129561
   44700   66049   79722   89961  107630   76194  111103
River Rch & RM=Trinity River,1               ,127110
   44700   65815   78807   88212  104089   75429  107679
River Rch & RM=Trinity River,1               ,124996
   44700   65743   78512   87518  102003   75176  105712
River Rch & RM=Trinity River,1               ,123554
   44700   65742   78271   86865  100204   74991  104042
River Rch & RM=Trinity River,1               ,122155
   44700   65729   78023   86289   98891   74783  102800
River Rch & RM=Trinity River,1               ,120905
   44700   65695   77673   85471   97034   74485  101039
River Rch & RM=Trinity River,1               ,118211
   44700   65695   77587   85149   95921   74416  100001
River Rch & RM=Trinity River,1               ,116211
   44700   65695   77575   85099   95457   74405   99637
River Rch & RM=Trinity River,1               ,113969
   40000   61295   71398   80343   87595   72241   88631
River Rch & RM=Trinity River,1               ,112556
   40000   61291   71281   79867   85924   72142   87038
River Rch & RM=Trinity River,1               ,110130
   40000   61291   71269   79694   85126   72132   86276
River Rch & RM=Trinity River,1               ,108725
   40000   61291   71269   79650   84751   72132   85924
River Rch & RM=Trinity River,1               ,107532
   40000   61291   71262   79394   83402   72131   84529
River Rch & RM=Trinity River,1               ,104348
   40000   62008   73422   84781  106737   73589  109056
River Rch & RM=Trinity River,1               ,96265
   40000   62005   73273   83325   99225   73526  101078
River Rch & RM=Trinity River,1               ,95077
   40000   62005   73246   82957   97670   73518   99415
River Rch & RM=Trinity River,1               ,91978
   40000   62000   73037   82047   94619   73393   96168
River Rch & RM=Trinity River,1               ,83613
   56100   86267  102499  115869  147207   98335  150100
River Rch & RM=Trinity River,1               ,80593
   56100   86297  103199  118346  156321   98860  159388
River Rch & RM=Trinity River,1               ,76398
   56100   86297  102909  117395  153572   98669  156563
River Rch & RM=Trinity River,1               ,74608
   56100   86900  110479  138421  209309  104114  212555
River Rch & RM=Trinity River,1               ,72672
   56100   86896  109963  137070  205824  103731  208981
River Rch & RM=Trinity River,1               ,71053
   56100   86861  109210  135335  201676  103136  204734
River Rch & RM=Trinity River,1               ,68028
   56100   86838  108124  132522  192141  102287  194934
River Rch & RM=Trinity River,1               ,65984
   56100   86836  107011  129170  182626  101459  185223
River Rch & RM=Trinity River,1               ,64637
   56100   86834  106583  127365  176781  101167  179271
River Rch & RM=Trinity River,1               ,62238
   56100   86831  105966  125051  169878  100728  172248
River Rch & RM=Trinity River,1               ,59702
   56100   86800  104338  120222  156737   99453  158935
River Rch & RM=Trinity River,1               ,56823
   56100   86800  103899  118920  152495   99098  154591
River Rch & RM=Trinity River,1               ,55303
   56100   86800  103899  118888  151146   99098  153198
River Rch & RM=Trinity River,1               ,53117
   56100   86875  109244  131796  181011  103218  183863
River Rch & RM=Trinity River,1               ,51036
   56100   86875  109005  130576  176441  103046  179203
River Rch & RM=Trinity River,1               ,48916
   51600   78575  102701  126168  167459  100774  168767
River Rch & RM=Trinity River,1               ,46568
   51600   78575  102301  123596  159545  100474  160751
River Rch & RM=Trinity River,1               ,45073
   51600   78575  101772  121544  154452  100036  155579
River Rch & RM=Trinity River,1               ,44793
   51600   78575  101772  121544  154452  100036  155579
River Rch & RM=Trinity River,1               ,43746
   51600   78575  101397  120399  151548   99708  152598
River Rch & RM=Trinity River,1               ,42372
   51600   78403   99736  117205  145757   98179  146712
River Rch & RM=Trinity River,1               ,39787
   51600   78400   99218  115868  142484   97711  143359
River Rch & RM=Trinity River,1               ,38724
   51600   78375   98359  113963  138763   96928  139570
River Rch & RM=Trinity River,1               ,37337
   51600   78266   97508  112342  135723   96140  136463
River Rch & RM=Trinity River,1               ,35159
   51600   77976   96109  109477  130089   94854  130684
River Rch & RM=Trinity River,1               ,32786
   51600   77976   96085  109217  128917   94838  129436
River Rch & RM=Trinity River,1               ,30239
   51600   77976   95951  108396  126459   94736  126840
River Rch & RM=Trinity River,1               ,28041
   51600   77976   95899  107960  124932   94696  125230
River Rch & RM=Trinity River,1               ,26191
   51600   77975   95621  106827  121908   94467  122064
River Rch & RM=Trinity River,1               ,24046
   51600   77975   95591  106502  120583   94451  120641
River Rch & RM=Trinity River,1               ,19761
   51600   77975   95591  106502  120357   94451  120374
River Rch & RM=Trinity River,1               ,17358
   51600   77975   95488  105875  118183   94379  118115
River Rch & RM=Trinity River,1               ,15600
   51600   77975   95488  105768  116821   94379  116665
River Rch & RM=Trinity River,1               ,13539
   51600   77975   95488  105742  116296   94379  116118
River Rch & RM=Trinity River,1               ,11371
   51600   78600  104501  133942  196620  102015  198170
River Rch & RM=Trinity River,1               ,9505
   51600   78600  104500  133677  195527  102015  197064
River Rch & RM=Trinity River,1               ,7604
   51600   78600  104500  133585  194701  102015  196225
River Rch & RM=Trinity River,1               ,6288
   51600   78600  104500  133542  194157  102015  195673
Boundary for River Rch & Prof#=Trinity River,1               , 1
Up Type= 0
Dn Type= 1
Dn Known WS=322.4
Boundary for River Rch & Prof#=Trinity River,1               , 2
Up Type= 0
Dn Type= 1
Dn Known WS=325.55
Boundary for River Rch & Prof#=Trinity River,1               , 3
Up Type= 0
Dn Type= 1
Dn Known WS=327.49
Boundary for River Rch & Prof#=Trinity River,1               , 4
Up Type= 0
Dn Type= 1
Dn Known WS=329.3
Boundary for River Rch & Prof#=Trinity River,1               , 5
Up Type= 0
Dn Type= 1
Dn Known WS=332.4
Boundary for River Rch & Prof#=Trinity River,1               , 6
Up Type= 0
Dn Type= 1
Dn Known WS=327.32
Boundary for River Rch & Prof#=Trinity River,1               , 7
Up Type= 0
Dn Type= 1
Dn Known WS=332.47
DSS Import GetInterval= 0
DSS Import GetPeak= 0
DSS Import FillOption= 0

--- TR_FEMA.f10 (steady flow) ---

Flow Title=2020 KaufHendLID1 Reduced Discharges_FW
Program Version=5.06
Number of Profiles= 2
Profile Names=100yr,FW
River Rch & RM=Trinity River,1               ,205777
  120200  120200
River Rch & RM=Trinity River,1               ,200569
  117604  117604
River Rch & RM=Trinity River,1               ,198513
  115435  115435
River Rch & RM=Trinity River,1               ,196991
  113486  113486
River Rch & RM=Trinity River,1               ,195872
  112383  112383
River Rch & RM=Trinity River,1               ,194145
  110743  110743
River Rch & RM=Trinity River,1               ,193094
  110146  110146
River Rch & RM=Trinity River,1               ,191491
  108900  108900
River Rch & RM=Trinity River,1               ,189380
  106968  106968
River Rch & RM=Trinity River,1               ,187750
  104741  104741
River Rch & RM=Trinity River,1               ,186516
  102185  102185
River Rch & RM=Trinity River,1               ,186264
  102185  102185
River Rch & RM=Trinity River,1               ,184503
  100291  100291
River Rch & RM=Trinity River,1               ,181750
   98659   98659
River Rch & RM=Trinity River,1               ,179572
   97745   97745
River Rch & RM=Trinity River,1               ,178698
   97119   97119
River Rch & RM=Trinity River,1               ,176021
   85208   85208
River Rch & RM=Trinity River,1               ,172483
   84264   84264
River Rch & RM=Trinity River,1               ,169025
   83032   83032
River Rch & RM=Trinity River,1               ,167085
   81420   81420
River Rch & RM=Trinity River,1               ,165454
   80056   80056
River Rch & RM=Trinity River,1               ,165204
   80056   80056
River Rch & RM=Trinity River,1               ,164199
   79708   79708
River Rch & RM=Trinity River,1               ,162832
   79382   79382
River Rch & RM=Trinity River,1               ,161707
   78205   78205
River Rch & RM=Trinity River,1               ,159456
   76383   76383
River Rch & RM=Trinity River,1               ,157344
   75613   75613
River Rch & RM=Trinity River,1               ,154267
   75896   75896
River Rch & RM=Trinity River,1               ,151264
   75677   75677
River Rch & RM=Trinity River,1               ,148768
   75646   75646
River Rch & RM=Trinity River,1               ,147333
  101796  101796
River Rch & RM=Trinity River,1               ,145717
  100066  100066
River Rch & RM=Trinity River,1               ,143893
   98353   98353
River Rch & RM=Trinity River,1               ,141890
   96461   96461
River Rch & RM=Trinity River,1               ,139225
   95114   95114
River Rch & RM=Trinity River,1               ,137179
   94221   94221
River Rch & RM=Trinity River,1               ,135104
   92323   92323
River Rch & RM=Trinity River,1               ,133245
   91574   91574
River Rch & RM=Trinity River,1               ,131382
   91110   91110
River Rch & RM=Trinity River,1               ,129561
   89961   89961
River Rch & RM=Trinity River,1               ,127110
   88212   88212
River Rch & RM=Trinity River,1               ,124996
   87518   87518
River Rch & RM=Trinity River,1               ,123554
   86865   86865
River Rch & RM=Trinity River,1               ,122155
   86289   86289
River Rch & RM=Trinity River,1               ,120905
   85471   85471
River Rch & RM=Trinity River,1               ,118211
   85149   85149
River Rch & RM=Trinity River,1               ,116211
   85099   85099
River Rch & RM=Trinity River,1               ,113969
   80343   80343
River Rch & RM=Trinity River,1               ,112556
   79867   79867
River Rch & RM=Trinity River,1               ,110130
   79694   79694
River Rch & RM=Trinity River,1               ,108725
   79650   79650
River Rch & RM=Trinity River,1               ,107532
   79394   79394
River Rch & RM=Trinity River,1               ,104348
   84781   84781
River Rch & RM=Trinity River,1               ,96265
   83325   83325
River Rch & RM=Trinity River,1               ,95077
   82957   82957
River Rch & RM=Trinity River,1               ,91978
   82047   82047
River Rch & RM=Trinity River,1               ,83613
  115869  115869
River Rch & RM=Trinity River,1               ,80593
  118346  118346
River Rch & RM=Trinity River,1               ,76398
  117395  117395
River Rch & RM=Trinity River,1               ,74608
  138421  138421
River Rch & RM=Trinity River,1               ,72672
  137070  137070
River Rch & RM=Trinity River,1               ,71053
  135335  135335
River Rch & RM=Trinity River,1               ,68028
  132522  132522
River Rch & RM=Trinity River,1               ,65984
  129170  129170
River Rch & RM=Trinity River,1               ,64637
  127365  127365
River Rch & RM=Trinity River,1               ,62238
  125051  125051
River Rch & RM=Trinity River,1               ,59702
  120222  120222
River Rch & RM=Trinity River,1               ,56823
  118920  118920
River Rch & RM=Trinity River,1               ,55303
  141000  141000
River Rch & RM=Trinity River,1               ,53117
  141000  141000
River Rch & RM=Trinity River,1               ,51036
  141000  141000
River Rch & RM=Trinity River,1               ,48916
  137400  137400
River Rch & RM=Trinity River,1               ,46568
  137400  137400
River Rch & RM=Trinity River,1               ,45073
  137400  137400
River Rch & RM=Trinity River,1               ,44793
  137400  137400
River Rch & RM=Trinity River,1               ,43746
  137400  137400
River Rch & RM=Trinity River,1               ,42372
  137400  137400
River Rch & RM=Trinity River,1               ,39787
  137400  137400
River Rch & RM=Trinity River,1               ,38724
  137400  137400
River Rch & RM=Trinity River,1               ,37337
  137400  137400
River Rch & RM=Trinity River,1               ,35159
  137400  137400
River Rch & RM=Trinity River,1               ,32786
  137400  137400
River Rch & RM=Trinity River,1               ,30239
  137400  137400
River Rch & RM=Trinity River,1               ,28041
  137400  137400
River Rch & RM=Trinity River,1               ,26191
  137400  137400
River Rch & RM=Trinity River,1               ,24046
  137400  137400
River Rch & RM=Trinity River,1               ,19761
  137400  137400
River Rch & RM=Trinity River,1               ,17358
  137400  137400
River Rch & RM=Trinity River,1               ,15600
  137400  137400
River Rch & RM=Trinity River,1               ,13539
  137400  137400
River Rch & RM=Trinity River,1               ,11371
  137400  137400
River Rch & RM=Trinity River,1               ,9505
  137400  137400
River Rch & RM=Trinity River,1               ,7604
  137400  137400
River Rch & RM=Trinity River,1               ,6288
  137400  137400
Boundary for River Rch & Prof#=Trinity River,1               , 1
Up Type= 0
Dn Type= 1
Dn Known WS=321.15
Boundary for River Rch & Prof#=Trinity River,1               , 2
Up Type= 0
Dn Type= 1
Dn Known WS=321.15
DSS Import GetInterval= 0
DSS Import GetPeak= 0
DSS Import FillOption= 0

--- TR_FEMA.f11 (steady flow) ---

Flow Title=2020 EllisLID2 Reduced Discharges_FW
Program Version=5.06
Number of Profiles= 2
Profile Names=100yr,FW
River Rch & RM=Trinity River,1               ,205777
  120200  120200
River Rch & RM=Trinity River,1               ,200569
  117604  117604
River Rch & RM=Trinity River,1               ,198513
  115435  115435
River Rch & RM=Trinity River,1               ,196991
  113486  113486
River Rch & RM=Trinity River,1               ,195872
  112383  112383
River Rch & RM=Trinity River,1               ,194145
  110743  110743
River Rch & RM=Trinity River,1               ,193094
  110146  110146
River Rch & RM=Trinity River,1               ,191491
  108900  108900
River Rch & RM=Trinity River,1               ,189380
  106968  106968
River Rch & RM=Trinity River,1               ,187750
  104741  104741
River Rch & RM=Trinity River,1               ,186516
  102185  102185
River Rch & RM=Trinity River,1               ,186264
  102185  102185
River Rch & RM=Trinity River,1               ,184503
  100291  100291
River Rch & RM=Trinity River,1               ,181750
   98659   98659
River Rch & RM=Trinity River,1               ,179572
   97745   97745
River Rch & RM=Trinity River,1               ,178698
   97119   97119
River Rch & RM=Trinity River,1               ,176021
   85208   85208
River Rch & RM=Trinity River,1               ,172483
   84264   84264
River Rch & RM=Trinity River,1               ,169025
   83032   83032
River Rch & RM=Trinity River,1               ,167085
   81420   81420
River Rch & RM=Trinity River,1               ,165454
   80056   80056
River Rch & RM=Trinity River,1               ,165204
   80056   80056
River Rch & RM=Trinity River,1               ,164199
   79708   79708
River Rch & RM=Trinity River,1               ,162832
   79382   79382
River Rch & RM=Trinity River,1               ,161707
   78205   78205
River Rch & RM=Trinity River,1               ,159456
   76383   76383
River Rch & RM=Trinity River,1               ,157344
   75613   75613
River Rch & RM=Trinity River,1               ,154267
   75896   75896
River Rch & RM=Trinity River,1               ,151264
   75677   75677
River Rch & RM=Trinity River,1               ,148768
   75646   75646
River Rch & RM=Trinity River,1               ,147333
  101796  101796
River Rch & RM=Trinity River,1               ,145717
  100066  100066
River Rch & RM=Trinity River,1               ,143893
   98353   98353
River Rch & RM=Trinity River,1               ,141890
   96461   96461
River Rch & RM=Trinity River,1               ,139225
   95114   95114
River Rch & RM=Trinity River,1               ,137179
   94221   94221
River Rch & RM=Trinity River,1               ,135104
   92323   92323
River Rch & RM=Trinity River,1               ,133245
   91574   91574
River Rch & RM=Trinity River,1               ,131382
   91110   91110
River Rch & RM=Trinity River,1               ,129561
   89961   89961
River Rch & RM=Trinity River,1               ,127110
   88212   88212
River Rch & RM=Trinity River,1               ,124996
   87518   87518
River Rch & RM=Trinity River,1               ,123554
   86865   86865
River Rch & RM=Trinity River,1               ,122155
   86289   86289
River Rch & RM=Trinity River,1               ,120905
   85471   85471
River Rch & RM=Trinity River,1               ,118211
   85149   85149
River Rch & RM=Trinity River,1               ,116211
   85099   85099
River Rch & RM=Trinity River,1               ,113969
   80343   80343
River Rch & RM=Trinity River,1               ,112556
   79867   79867
River Rch & RM=Trinity River,1               ,110130
   79694   79694
River Rch & RM=Trinity River,1               ,108725
   79650   79650
River Rch & RM=Trinity River,1               ,107532
   79394   79394
River Rch & RM=Trinity River,1               ,104348
   84781   84781
River Rch & RM=Trinity River,1               ,96265
   83325   83325
River Rch & RM=Trinity River,1               ,95077
   82957   82957
River Rch & RM=Trinity River,1               ,91978
   82047   82047
River Rch & RM=Trinity River,1               ,83613
  115869  115869
River Rch & RM=Trinity River,1               ,80593
  118346  118346
River Rch & RM=Trinity River,1               ,76398
  117395  117395
River Rch & RM=Trinity River,1               ,74608
  138421  138421
River Rch & RM=Trinity River,1               ,72672
  137070  137070
River Rch & RM=Trinity River,1               ,71053
  141000  141000
River Rch & RM=Trinity River,1               ,68028
  141000  141000
River Rch & RM=Trinity River,1               ,65984
  141000  141000
River Rch & RM=Trinity River,1               ,64637
  141000  141000
River Rch & RM=Trinity River,1               ,62238
  141000  141000
River Rch & RM=Trinity River,1               ,59702
  141000  141000
River Rch & RM=Trinity River,1               ,56823
  141000  141000
River Rch & RM=Trinity River,1               ,55303
  141000  141000
River Rch & RM=Trinity River,1               ,53117
  141000  141000
River Rch & RM=Trinity River,1               ,51036
  141000  141000
River Rch & RM=Trinity River,1               ,48916
  137400  137400
River Rch & RM=Trinity River,1               ,46568
  137400  137400
River Rch & RM=Trinity River,1               ,45073
  137400  137400
River Rch & RM=Trinity River,1               ,44793
  137400  137400
River Rch & RM=Trinity River,1               ,43746
  137400  137400
River Rch & RM=Trinity River,1               ,42372
  137400  137400
River Rch & RM=Trinity River,1               ,39787
  137400  137400
River Rch & RM=Trinity River,1               ,38724
  137400  137400
River Rch & RM=Trinity River,1               ,37337
  137400  137400
River Rch & RM=Trinity River,1               ,35159
  137400  137400
River Rch & RM=Trinity River,1               ,32786
  137400  137400
River Rch & RM=Trinity River,1               ,30239
  137400  137400
River Rch & RM=Trinity River,1               ,28041
  137400  137400
River Rch & RM=Trinity River,1               ,26191
  137400  137400
River Rch & RM=Trinity River,1               ,24046
  137400  137400
River Rch & RM=Trinity River,1               ,19761
  137400  137400
River Rch & RM=Trinity River,1               ,17358
  137400  137400
River Rch & RM=Trinity River,1               ,15600
  137400  137400
River Rch & RM=Trinity River,1               ,13539
  105742  105742
River Rch & RM=Trinity River,1               ,11371
  133942  133942
River Rch & RM=Trinity River,1               ,9505
  133677  133677
River Rch & RM=Trinity River,1               ,7604
  133585  133585
River Rch & RM=Trinity River,1               ,6288
  133542  133542
Boundary for River Rch & Prof#=Trinity River,1               , 1
Up Type= 0
Dn Type= 1
Dn Known WS=329.3
Boundary for River Rch & Prof#=Trinity River,1               , 2
Up Type= 0
Dn Type= 1
Dn Known WS=329.3
DSS Import GetInterval= 0
DSS Import GetPeak= 0
DSS Import FillOption= 0

--- TR_FEMA.g08 (geometry) ---

Geom Title=Trinity_NV_DallasLID1_DallasLID2
Program Version=5.06
BEGIN GEOM DESCRIPTION:
Scenario F
END GEOM DESCRIPTION:

River Reach=Trinity River   ,1
Reach XY= 30
  2533404.179945 6920900.8502127 2544550.8184133 6917125.2239057
 2544058.6307494 6913752.8280915 2548240.6332122 6910836.1613527
 2555154.6954995 6910570.5362277 2553745.8613749 6908937.1297177
 2557089.5915641 6908812.7237985 2559386.4665635 6898734.5989417
 2562092.1957321 6898567.9322802 2561532.2998703 6895517.7585906
  2565967.195528 6890397.9669929 2575540.6042027 6887227.2781243
 2578748.0695725 6882027.6254659 2582582.2708936 6882601.4100795
 2584509.3543097 6875174.3268366 2580884.3540138 6874960.7852689
 2584936.9207118 6868948.5577921 2582673.4167087 6869854.0143145
 2584566.6458618  6866338.389456 2581993.7290917 6864090.9933602
 2587605.7083533 6858291.5144737  2585876.541536 6853739.4310582
 2590225.5000297 6853187.3475167  2592465.083477 6846952.9725182
 2605918.2084736 6838679.5349969 2604199.4583022 6834713.3893859
 2605967.6873772 6830557.1391682 2601574.2414397 6827710.7852809
 2600158.4427622  6822765.472665 2602560.0652555 6815234.1468484

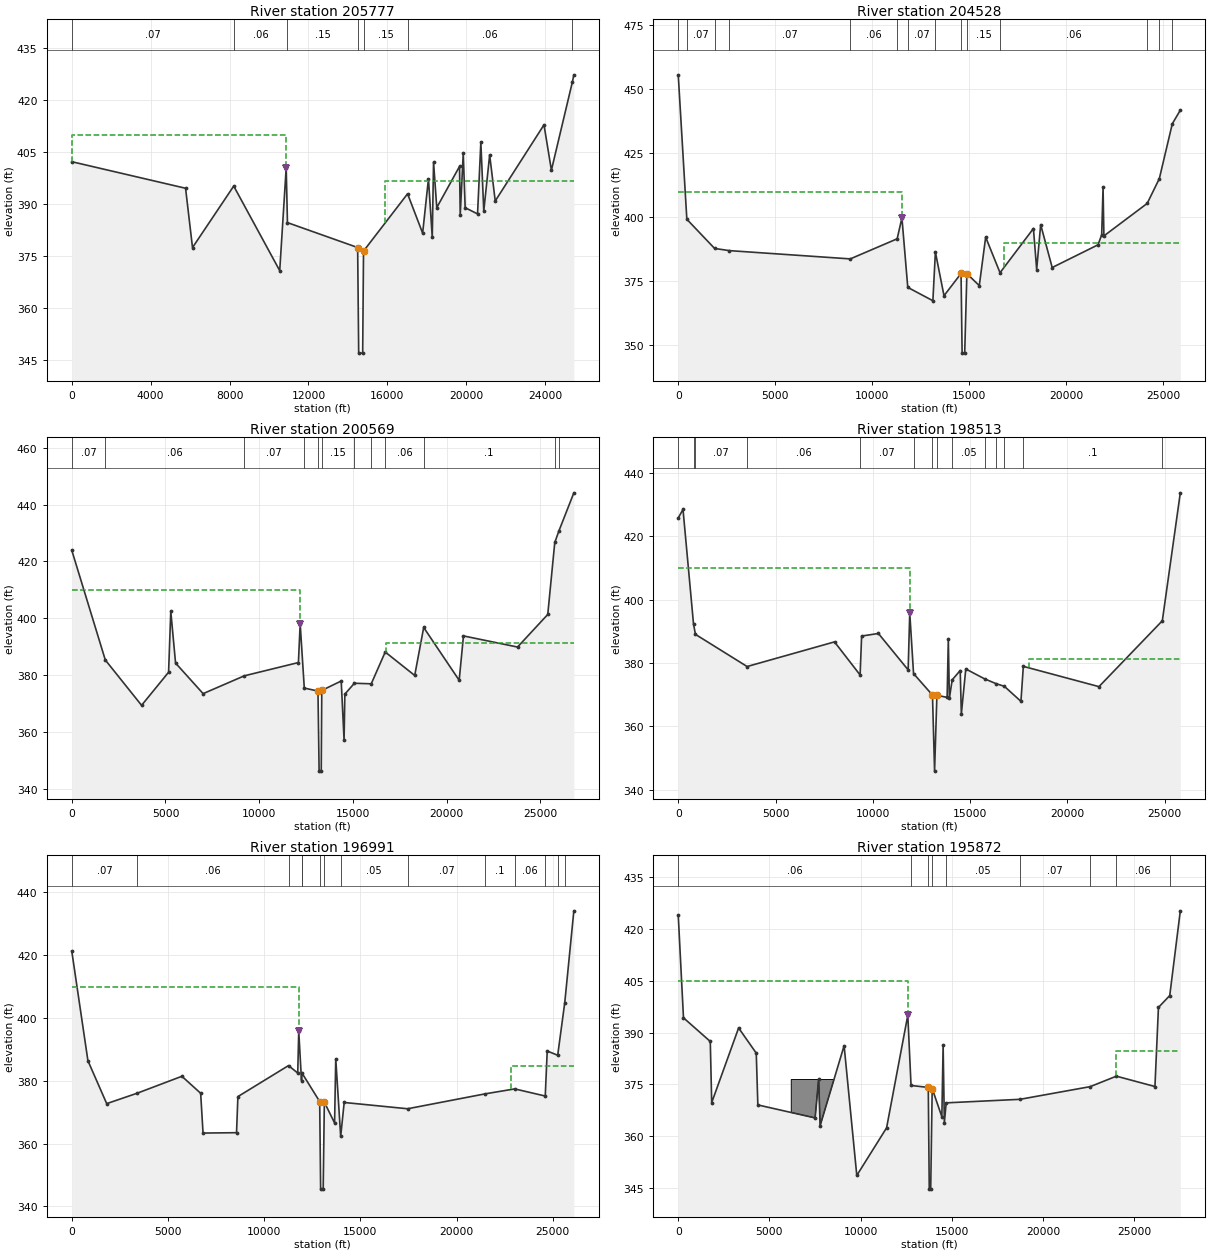
Type RM Length L Ch R = 1 ,205777  ,1262.75,1248.24,1229.51
BEGIN DESCRIPTION:
LOB - Southside WWTP
END DESCRIPTION:
XS GIS Cut Line= 6
2540980.83019298 6933539.73664742535497.477602626924208.30611411
2533614.000070366920921.000024692533600.635923866920903.28221235
 2529903.70565376914444.53364694 2528203.05241526911525.84775851
#Sta/Elev= 30
       0  402.32 5769.27  394.66 6121.02  377.55 8210.64  395.2910542.62  370.89
10870.96  400.54 10934.7  384.7514493.46  377.5614546.29   347.114748.07   347.1
14791.42  376.5417024.34  393.0617788.14  381.7118082.62  397.3718276.12  380.47
18341.35  402.1718504.74  389.0819659.18  400.9719693.92  387.0319847.13  404.74
19944.42  389.0520572.06  387.2620739.04  407.9220887.76  388.0721186.02  404.29
21468.32  390.9923940.48  412.9624316.52  399.8725381.49  425.37 25454.1  427.38
#Mann= 7 ,-1 , 0
       0     .07       0 8210.64     .06       0 10934.7     .15       0
14493.46    .055       014791.42     .15       017024.34     .06       0
25381.49     .08       0
Levee=-1,10870.96,400.54,0,,,,
#XS Ineff= 2 ,-1
       010870.96     41015871.74 25884.1  396.63
Permanent Ineff=
       F       F
Bank Sta=14493.46,14791.42
XS Rating Curve= 0 ,0
Exp/Cntr=0.3,0.1

Type RM Length L Ch R = 1 ,204528  ,2887.05,3959.05,2930.12
BEGIN DESCRIPTION:
LOB - Southside WWTP, ROB - Dallas LID1/2
END DESCRIPTION:
XS GIS Cut Line= 2
2542141.897480176933195.790666072529164.466924626910799.95733273
#Sta/Elev= 30
       0  455.63  443.94  399.25 1874.77  387.86 2636.03  387.01 8868.79  383.78
 11286.5  391.6211531.94  399.8111833.59  372.66   13128  367.4513257.32  386.45
13701.35  369.4114580.29  378.0914635.11     34714768.51     34714880.75  378.02
 15520.2  373.3515849.58  392.2716589.78  378.3818311.86  395.6418478.88  379.64
18685.27  397.1519279.01  380.4121641.73  389.2821830.52  393.1621901.42  411.66
21944.71  392.7524176.62  405.4324802.88  415.12 25470.9  436.52 25884.1  441.84
#Mann= 14 ,-1 , 0
       0     .06       0  443.94     .07       0 1874.77     .06       0
 2636.03     .07       0 8868.79     .06       0 11286.5     .07       0
11833.59     .07       013257.32     .15       014580.29    .055       0
14880.75     .15       016589.78     .06       024176.62      .1       0
24802.88     .08       0 25470.9     .06       0
Levee=-1,11531.94,399.81,0,,,,
#XS Ineff= 2 ,-1
       011531.94     41016781.26 25884.1  389.93
Permanent Ineff=
       F       F
Bank Sta=14580.29,14880.75
XS Rating Curve= 0 ,0
Exp/Cntr=0.3,0.1

Type RM Length L Ch R = 1 ,200569  ,2068.54,2056.32,2002.94
BEGIN DESCRIPTION:
LOB - Southside WWTP
END DESCRIPTION:
XS GIS Cut Line= 2
2544594.042023046931842.514654862531312.792023046908578.62576596
#Sta/Elev= 30
       0  423.94 1788.99  385.37 3724.12  369.43 5165.31  381.06  5282.7  402.49
 5537.92  384.29 7008.09  373.54 9204.36   379.8 12092.6  384.4712186.52  398.09
12405.92   375.513135.77  374.4413197.04   346.313309.94   346.313339.14  374.67
14376.03  377.98 14528.7  357.2114570.62  373.3715078.25  377.1915978.95     377
16723.98  388.1718297.74  379.9318776.03   396.820669.98  378.2320898.87  393.83
23784.09  389.9225396.01  401.3725770.55  426.6825998.04  430.8526788.13  444.13
#Mann= 12 ,-1 , 0
       0     .07       0 1788.99     .06       0 9204.36     .07       0
12405.92     .15       013135.77    .055       013339.14     .15       0
15078.25     .05       015978.95     .15       016723.98     .06       0
18776.03      .1       025770.55     .06       025998.04      .1       0
Levee=-1,12186.52,398.09,0,,,,
#XS Ineff= 2 , 0
       012186.52     41016773.27       0  391.17
Permanent Ineff=
       F       F
Bank Sta=13135.77,13339.14
XS Rating Curve= 0 ,0
Exp/Cntr=0.3,0.1

Type RM Length L Ch R = 1 ,198513  ,1460.65,1522.21,1546.82
BEGIN DESCRIPTION:
LOB - Southside WWTP
END DESCRIPTION:
XS GIS Cut Line= 2
2546593.000356376930554.320210412533259.667023046908470.98687708
#Sta/Elev= 30
       0  425.75  245.08  428.46  785.82  392.24  884.58  389.01 3538.59  378.86
  8028.9  386.64 9344.62  376.19 9422.44  388.4810284.69  389.2911812.69   377.8
11895.24  395.8312090.23  376.6313062.88  369.8413170.69  345.8413290.24  369.79
13815.75  369.1113876.77  387.6313931.21  368.8614077.49  374.6714487.86   377.6
14545.98  363.8614774.24  378.0915737.73  374.9816333.56  373.4416753.99  372.62
17607.92  367.8717730.47  378.9121616.22  372.5124872.14   393.325796.39  433.69
#Mann= 14 ,-1 , 0
       0     .07       0  785.82     .06       0  884.58     .07       0
 3538.59     .06       0 9344.62     .07       012090.23     .15       0
13062.88    .055       013290.24     .15       014077.49     .05       0
15737.73     .15       016333.56     .05       016753.99      .1       0
17730.47      .1       024872.14     .06       0
Levee=-1,11895.24,395.83,0,,,,
#XS Ineff= 2 , 0
       011895.24     410 18035.9       0  381.17
Permanent Ineff=
       F       F
Bank Sta=13062.88,13290.24
XS Rating Curve= 0 ,0
Exp/Cntr=0.3,0.1

Type RM Length L Ch R = 1 ,196991  ,1114.91,1119.14,1044.18
BEGIN DESCRIPTION:
LOB - Southside WWTP
END DESCRIPTION:
XS GIS Cut Line= 4
2547677.578059796929952.10407455 2541957.4391709 6920324.0658801
2540764.383615346917785.437407882533997.022504236907764.60407454
#Sta/Elev= 30
       0  421.27  839.66  386.38 1815.93  372.72 3409.48  376.06 5723.11  381.43
 6699.35  376.02 6823.04  363.35 8563.77  363.47  8634.5  374.9611265.75  384.84
11744.94  382.4611797.07   395.811940.64  380.0711963.21  382.48 12885.5  373.39
12935.15   345.513068.07   345.513127.74   373.213659.69  366.5713720.65  387.01
13977.28  362.2714158.97  373.0917457.43  371.09 21480.1  375.8323024.23  377.41
24609.89  375.1424711.78  389.4725256.73  388.1325623.98  404.8926096.06  434.11
#Mann= 14 ,-1 , 0
       0     .07       0 3409.48     .06       011265.75     .07       0
11940.64     .06       011963.21     .15       0 12885.5    .055       0
13127.74     .15       013977.28     .05       017457.43     .07       0
 21480.1      .1       023024.23     .06       024609.89      .1       0
25256.73     .06       025623.98     .08       0
Levee=-1,11797.07,395.8,0,,,,
#XS Ineff= 2 , 0
       011797.07     41022847.01       0   384.8
Permanent Ineff=
       F       F
Bank Sta=12885.5,13127.74
XS Rating Curve= 0 ,0
Exp/Cntr=0.3,0.1

Type RM Length L Ch R = 1 ,195872  ,1736.76,1726.95,2123
BEGIN DESCRIPTION:
LOB - Southside WWTP
END DESCRIPTION:
XS GIS Cut Line= 4
2550259.667023046929359.875765962543024.453059796920010.14805602
2541811.258615346917361.536944912534173.275757926907095.38516339
#Sta/Elev= 30
       0  423.88  287.75  394.24 1757.09  387.42    1835  369.77 3310.85  391.32
 4278.01  384.05 4365.39   369.1 7505.83  365.35 7698.96  376.54    7781  363.13
 9095.51  386.19 9791.23  348.7511425.27  362.49   12588  394.9912765.73  374.72
13710.48  374.1513764.86   344.813843.92   344.813925.96  373.8214455.32  365.69
14525.15  386.3414592.48  363.9514693.44   369.718740.62  370.7222588.93  374.38
24027.44   377.426140.25  374.4126332.27  397.2426951.71  400.66 27531.3  425.12
#Mann= 9 ,-1 , 0
       0     .06       012765.73     .15       013710.48    .055       0
13925.96     .15       014693.44     .05       018740.62     .07       0
22588.93      .1       024027.44     .06       026951.71     .08       0
Levee=-1,12588,394.99,0,,,,
#XS Ineff= 2 , 0
       0   12588     40524005.96       0  384.75
Permanent Ineff=
       F       F
#Block Obstruct= 1 ,-1
 6197.83 8582.22  376.44
Bank Sta=13710.48,13925.96
XS Rating Curve= 0 ,0
Exp/Cntr=0.3,0.1

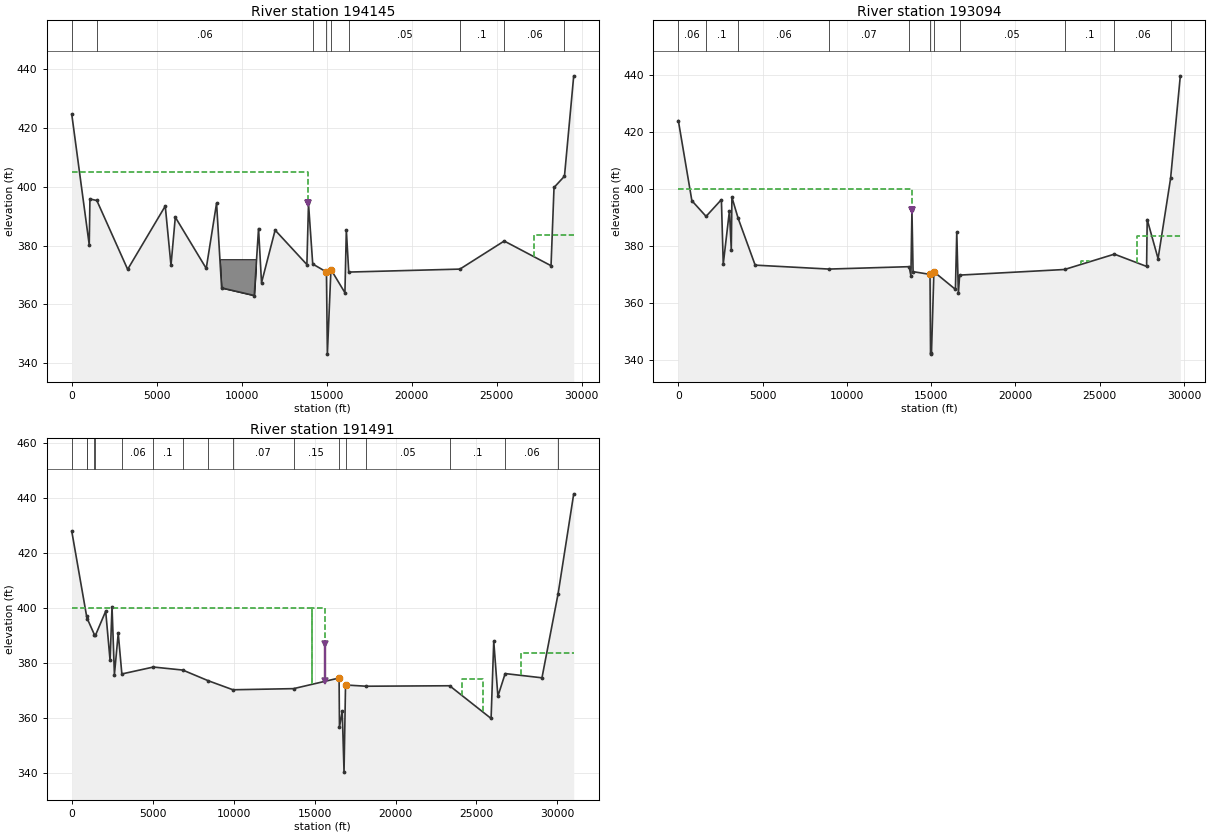
Type RM Length L Ch R = 1 ,194145  ,1483.79,1050.49,556.86
BEGIN DESCRIPTION:
LOB - Southside WWTP
END DESCRIPTION:
XS GIS Cut Line= 5
2552414.114273316929855.474110522544790.00861534 6919633.0184264
2543243.394032016916393.348287512539391.885627386911180.48068715
2534234.039646816906904.41294117
#Sta/Elev= 30
       0  424.67 1028.49  380.19 1068.58  395.85 1474.56  395.33 3287.19  371.88
 5499.11  393.44 5836.23  373.24 6089.75  389.65 7909.14   372.2 8517.13  394.42
 8812.55  365.5710733.65  362.9810985.54  385.7711161.06  367.3211960.74  385.24
13829.32  373.5213923.92  394.3114172.83   373.714979.29     37115034.01  343.02
 15243.9  371.8316066.48  363.9316149.17  385.3316290.69  370.9622830.01  371.97
 25434.8  381.53 28189.1  373.1328364.93  399.7628979.39  403.6129523.59  437.78
#Mann= 9 ,-1 , 0
       0     .07       0 1474.56     .06       014172.83     .15       0
14979.29    .055       0 15243.9     .15       016290.69     .05       0
22830.01      .1       0 25434.8     .06       028979.39     .08       0
Levee=-1,13923.92,394.31,0,,,,
#XS Ineff= 2 ,-1
       013923.92     405   2718029523.59   383.5
Permanent Ineff=
       F       F
#Block Obstruct= 1 ,-1
 8647.3510836.41  375.33
Bank Sta=14979.29,15243.9
XS Rating Curve= 0 ,0
Exp/Cntr=0.3,0.1

Type RM Length L Ch R = 1 ,193094  ,1345.47,1602.93,571.88
BEGIN DESCRIPTION:
LOB - Bois D'Arc
END DESCRIPTION:
XS GIS Cut Line= 6
2554287.822272766928551.859861582547075.160235726919489.91541714
2544537.150976466916846.084398622543603.168337566916029.93509307
2539605.679296536910746.672576352534260.081313476906748.16294117
#Sta/Elev= 30
       0  423.87  802.13  395.77 1644.45  390.26 2553.75  396.14  2664.1  373.49
 3030.79  392.22 3140.18  378.62 3179.36  396.96 3542.33  389.68  4557.8  373.14
 8938.06  371.7613693.36   372.613800.43  369.4313862.06  392.4913928.82  370.85
14934.28  369.8914965.13  342.1215019.17  341.8915165.17  370.8216441.82  364.63
16521.31  384.7516617.88  363.1916691.96  369.6422916.42  371.6125874.64     377
27787.39  372.6927822.69  389.1528468.09  375.4129211.55  403.6529787.92  439.62
#Mann= 11 ,-1 , 0
       0     .06       0 1644.45      .1       0 3542.33     .06       0
 8938.06     .07       013693.36     .15       014934.28    .055       0
15165.17     .15       016691.96     .05       022916.42      .1       0
25874.64     .06       029211.55     .08       0
Levee=-1,13862.06,392.49,0,,,,
#XS Ineff= 3 ,-1
       013862.06     400   23892   24354   374.627226.1529787.92   383.5
Permanent Ineff=
       F       F       F
Bank Sta=14934.28,15165.17
XS Rating Curve= 0 ,0
Exp/Cntr=0.3,0.1

Type RM Length L Ch R = 1 ,191491  ,988.29,2111.36,567.8
BEGIN DESCRIPTION:
LOB - Bois D'Arc
END DESCRIPTION:
XS GIS Cut Line= 5
2555578.266717196928321.341343082545553.422500736916302.54581884
2543740.689258426915107.066156172539778.685944756910550.30158257
 2534060.42853576906262.05183006
#Sta/Elev= 30
       0  427.89   914.4  397.07     958  396.09 1394.34  390.33 1462.77  390.03
 2095.76  398.81 2366.84  380.92 2487.11  400.45 2634.68  375.75  2870.8   390.8
 3094.27  375.98 5041.25   378.5 6856.41   377.4 8429.85  373.52 9956.04  370.23
13701.74  370.6416513.88  374.5116536.92  356.6116709.25  362.4516819.04  340.27
16912.14  371.9718190.28  371.5223342.01  371.6925903.58  359.7926067.98  387.88
26323.71  367.8826773.42  376.1229046.65  374.58 30044.5  405.21 31008.1  441.51
#Mann= 17 ,-1 , 0
       0     .08       0   914.4     .06       0     958     .08       0
 1394.34     .06       0 1462.77      .1       0 3094.27     .06       0
 5041.25      .1       0 6856.41     .06       0 8429.85      .1       0
 9956.04     .07       013701.74     .15       016513.88    .055       0
16912.14     .15       018190.28     .05       023342.01      .1       0
26773.42     .06       0 30044.5     .08       0
Levee=-1,15621.35,387.06,0,,,,
#XS Ineff= 4 ,-1
       0 14856.5     400 14856.515621.35     400   24113   25429   374.3
27766.49 31008.1   383.5
Permanent Ineff=
       F       F       F       F
Bank Sta=16513.88,16912.14
XS Rating Curve= 0 ,0
Exp/Cntr=0.3,0.1