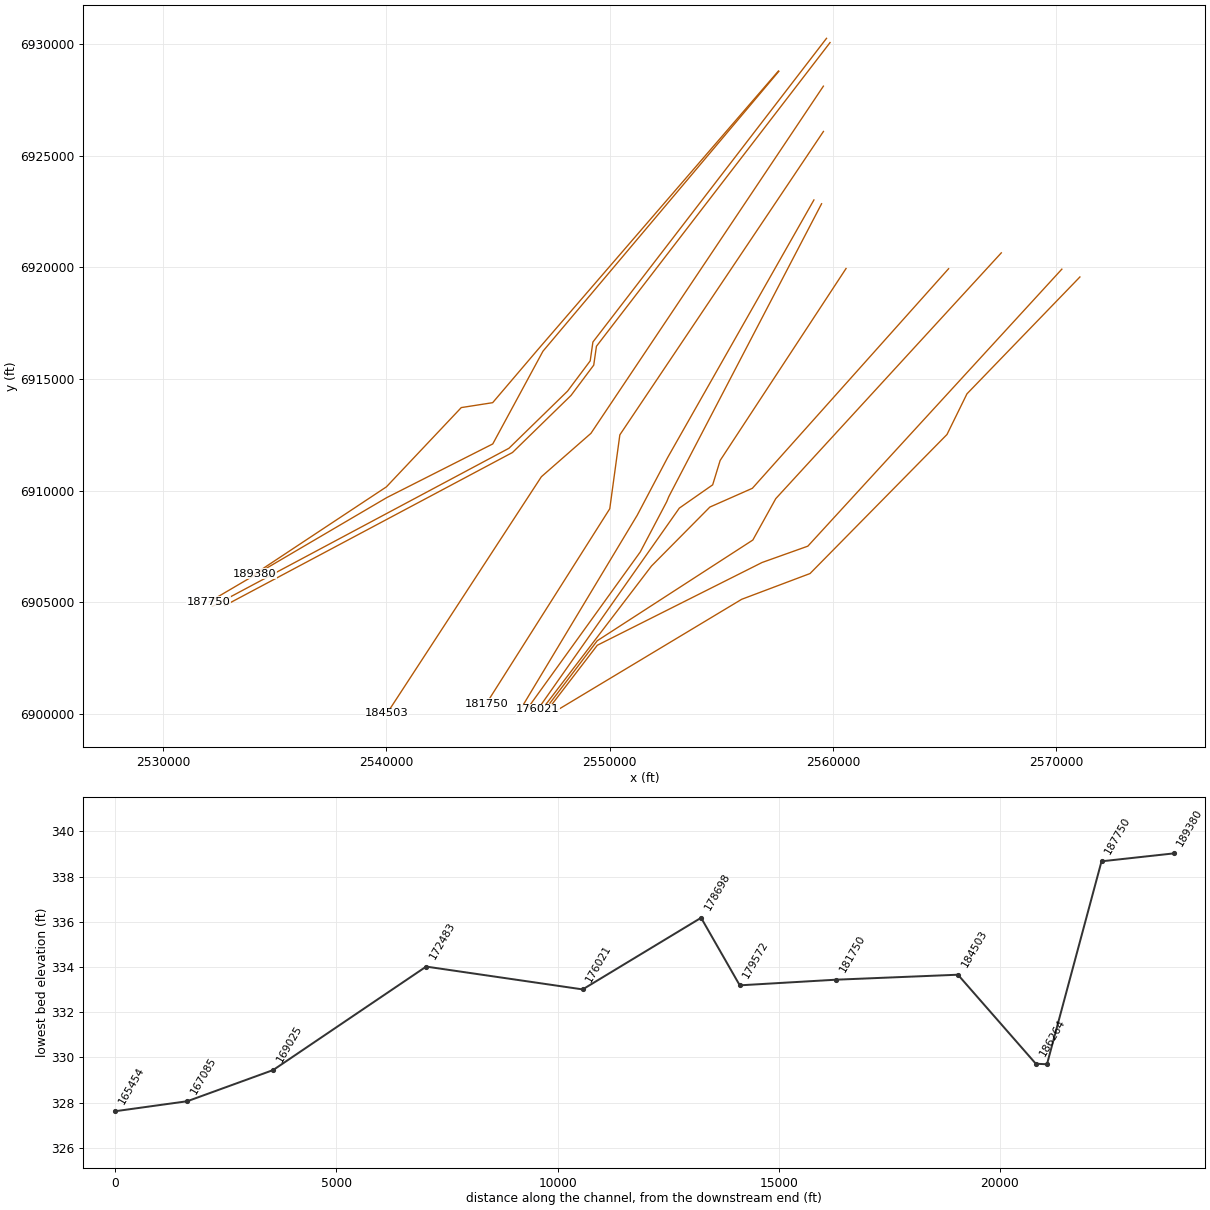
HEC-RAS study TR_FEMA.prj: Trinity_River_FEMA

--- TR_FEMA.g08 (geometry) --- (continued)

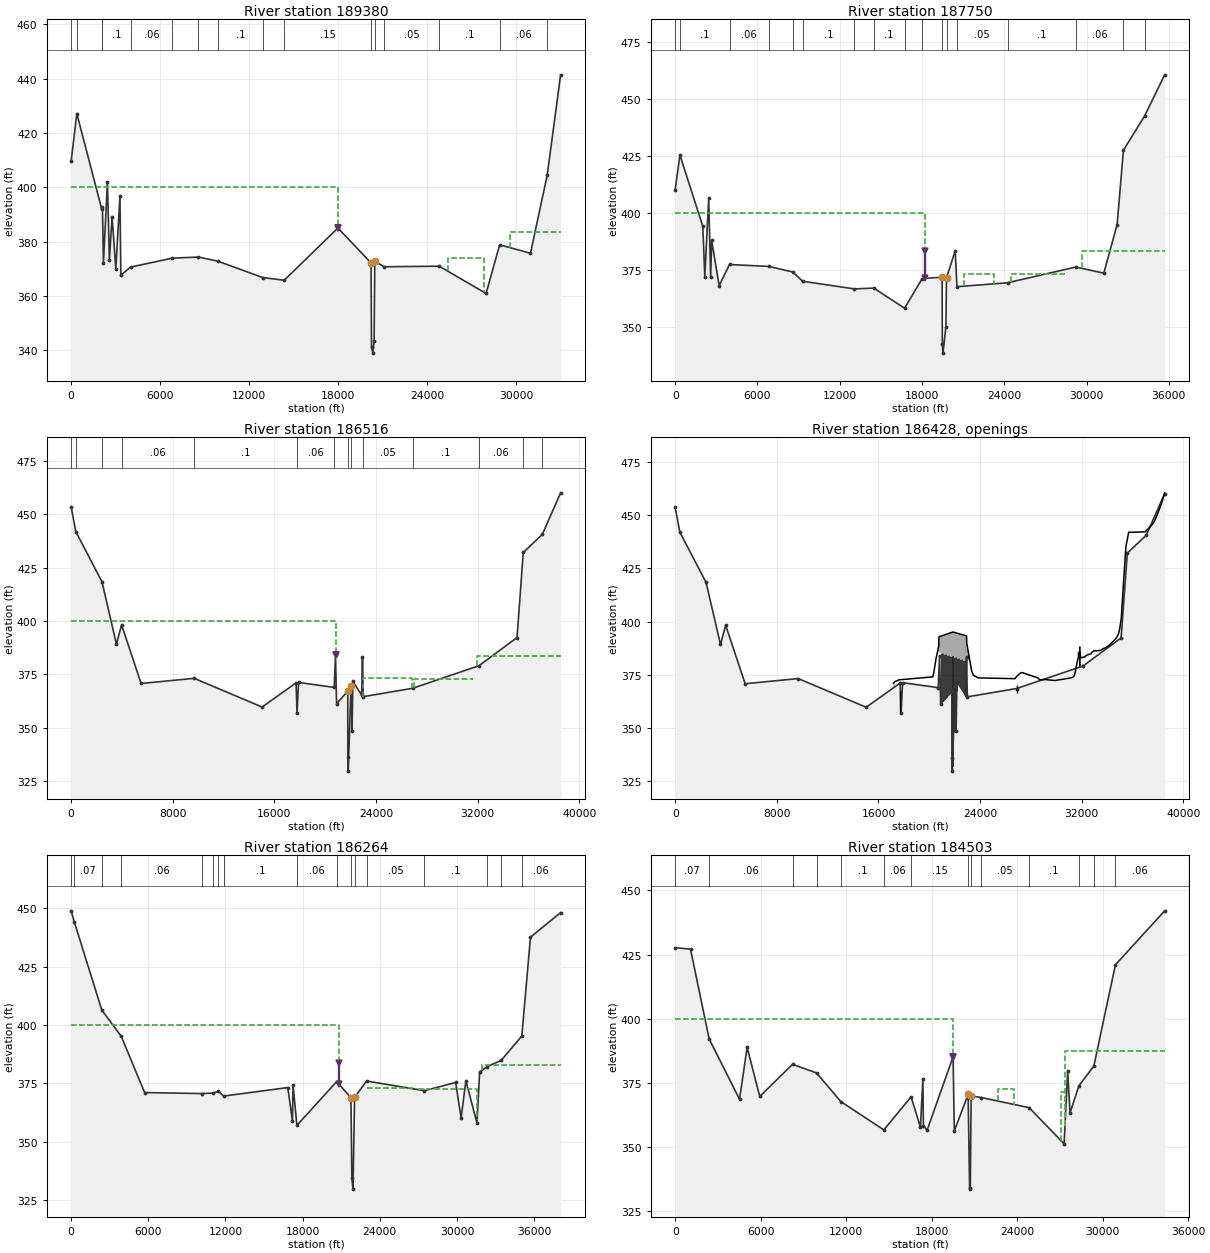
Type RM Length L Ch R = 1 ,189380  ,205.4,1630.38,1758.4
BEGIN DESCRIPTION:
LOB - Bois D'Arc
END DESCRIPTION:
XS GIS Cut Line= 6
  2557557.278625 6928809.5192494 2546769.9681061 6916304.8598616
  2544756.513245 6913938.4536116 2543350.9576894 6913718.6098616
 2539995.6050314 6910162.3039914 2534109.9081669 6906263.9017463
#Sta/Elev= 30
       0  409.66  382.37  427.22 2066.09  391.96 2111.19  392.75 2177.07  372.26
 2445.48  401.93 2579.32  373.42 2759.69   389.3 3011.42  370.03 3290.06  396.77
 3350.78  367.69 4004.94   370.7 6821.75  373.99 8574.54   374.4 9904.93  372.86
12916.52  366.8414364.36  365.8617978.65  385.0920215.37  372.2420245.75  341.42
20332.55  339.0320420.69  343.5120468.97   372.921083.89  370.8224809.52  371.03
27970.71  360.9928882.99   378.9   30962   375.832088.22  404.51 32993.3  441.47
#Mann= 16 ,-1 , 0
       0     .07       0  382.37      .1       0 2066.09     .08       0
 2111.19      .1       0 4004.94     .06       0 6821.75      .1       0
 8574.54     .06       0 9904.93      .1       012916.52     .07       0
14364.36     .15       020215.37    .055       020468.97     .15       0
21083.89     .05       024809.52      .1       028882.99     .06       0
32088.22     .08       0
Levee=-1,17978.65,385.09,0,,,,
#XS Ineff= 3 ,-1
       017978.65     400   25389   27830   373.929593.12 32993.3   383.5
Permanent Ineff=
       F       F       F
Bank Sta=20215.37,20468.97
XS Rating Curve= 0 ,0
Exp/Cntr=0.3,0.1

Type RM Length L Ch R = 1 ,187750  ,1654.61,1233.35,710.34
BEGIN DESCRIPTION:
LOB - Bois D'Arc
END DESCRIPTION:
XS GIS Cut Line= 5
2557577.386206416928797.378293492547009.279724936916245.27181201
2544761.617613766912088.929152132540023.244450286909687.41087415
2532045.813894736904999.91087415
#Sta/Elev= 30
       0  410.26  342.82  425.39 2013.52  394.14 2158.93  372.18 2443.22  406.42
 2586.02  371.87 2660.15  387.99    3205  368.22  3962.1  377.46 6839.49  376.61
 8585.85  374.15  9293.2  370.1413071.24  366.7814477.86  367.14 16729.9  358.34
18015.08  371.3319466.71   371.919483.08  342.7219528.79  338.6819742.26  350.26
19786.89  371.6320423.79  383.5520548.26  367.7424238.57  369.4729214.57  376.34
31259.22  373.6932231.63  394.9232689.61  427.4734227.79  442.3835698.68  460.45
#Mann= 17 ,-1 , 0
       0     .07       0  342.82      .1       0  3962.1     .06       0
 6839.49      .1       0 8585.85     .06       0  9293.2      .1       0
13071.24     .07       014477.86      .1       0 16729.9     .06       0
18015.08     .15       019466.71    .055       019786.89     .15       0
20548.26     .05       024238.57      .1       029214.57     .06       0
32689.61     .08       034227.79     .06       0
Levee=-1,18193.79,383.19,0,,,,
#XS Ineff= 4 ,-1
       018193.79     400   21067   23270  373.15   24481   28421   373.1
   2966235698.68   383.5
Permanent Ineff=
       F       F       F       F
Bank Sta=19466.71,19786.89
XS Rating Curve= 0 ,0
Exp/Cntr=0.5,0.3

Type RM Length L Ch R = 1 ,186516  ,201.27,252.24,272.65
BEGIN DESCRIPTION:
US Bridge
LOB - Bois D'Arc, ROB - Dallas LID1/2
END DESCRIPTION:
XS GIS Cut Line= 6
2559712.908234356930276.007165022549247.630456586916657.95160946
2549126.428199636915812.501667332548110.369171856914455.29680621
2545486.671255186911894.532917332532205.312748246904802.37435251
#Sta/Elev= 30
       0  453.62  365.68  442.01 2431.77   418.4 3564.01  389.22 3972.03  398.26
 5505.96  370.77 9682.73   373.215027.22  359.7417703.92  371.05 17779.5  357.05
17897.26  371.2820703.97  368.9420807.66  383.9220893.23  361.3121773.35  367.22
21778.85 336.09421812.34 329.69622024.35  369.6822072.81  370.4222108.38  348.51
22174.81  371.7922863.36  365.3422930.59  383.1422993.09  364.61   26878  368.53
32104.46  379.1235096.33  392.3235586.17  432.1837082.52  440.6438526.05  460.14
#Mann= 14 ,-1 , 0
       0     .08       0  365.68     .07       0 2431.77      .1       0
 3972.03     .06       0 9682.73      .1       0 17779.5     .06       0
20703.97     .15       021773.35    .055       022024.35     .15       0
22993.09     .05       0   26878      .1       032104.46     .06       0
35586.17     .08       037082.52     .06       0
Levee=-1,20807.66,383.92,0,,,,
#XS Ineff= 4 ,-1
       020807.66     400   22994   26792  373.15   26974   31669   373.1
   3196238526.05   383.5
Permanent Ineff=
       F       F       F       F
Bank Sta=21773.35,22024.35
XS Rating Curve= 0 ,0
Exp/Cntr=0.5,0.3

Type RM Length L Ch R = 4 ,186428  ,,,
BEGIN DESCRIPTION:
South Beltline Road - Bridge geometry per Compass survey dated July 2018.  Road deck supplemented with Lidar data outside of the surveyed bridge/culvert openings.
END DESCRIPTION:
Node Name=South Beltline R
Bridge Culvert--1,0,-1,-1, 0
Deck Dist Width WeirC Skew NumUp NumDn MinLoCord MaxHiCord MaxSubmerge Is_Ogee
70,85,2.6,0, 77, 118, , , 0.98, 0, 0,0,,
17176.3617299.0517614.9820281.5720375.7120529.3220742.6620746.44   2074720772.53
20784.06 20812.721851.3621856.9822922.0222935.2322946.8123337.2823466.4423844.39
26743.4726868.1827112.9527282.9528562.21 28681.629139.4629882.7130596.5831261.06
31405.9531490.8831670.7431715.7131739.4331749.4131754.1331804.3331864.8531867.12
31875.7531934.7632261.1232330.1532575.1532715.1532770.1132949.78 33174.633403.91
 33533.333737.3433847.2234057.0534196.9534366.8134546.6734791.4834906.3934976.34
35106.2335331.0635480.9435595.8535690.7835730.7535835.6635895.6236015.5237019.74
37099.6837154.6337524.3437734.1837953.6538246.8138525.06
  371.09  371.75  372.62  373.99  376.73  382.54  388.61 389.391 391.454 392.793
 392.951 392.956 395.075 395.087 393.298 393.155 389.885  376.64  374.76  373.52
  373.15  374.16  375.51  376.07  373.47  372.63  372.72  372.29  372.96  373.66
  374.48  376.43  381.83  382.81 383.492 385.541 385.535 385.469 385.391 385.388
 384.175  382.95  383.46     384  384.63  384.77   385.4   386.2  386.27  386.37
  386.62  387.43  387.61  388.37  389.06  390.15  391.03   392.9  394.55  396.31
  401.32  422.38  435.48  438.88  441.98  441.98  441.98  441.98  441.98  442.15
  443.01  443.15  445.41  447.38  450.43  455.02   460.5
         385.907  388.33 388.319 386.254
                                                 381.552  381.74 381.371
17176.3617299.0517456.6617614.9817793.08 17927.618305.3318469.2318692.7418950.96
19084.9519387.5519560.9819729.4519827.2620063.8820143.0420217.2520281.5720375.71
20529.3220643.3720742.6620746.44   2074720772.5320784.06 20793.521832.1621837.78
22858.7522859.3822871.9622883.5222883.5423063.0423182.7123337.2823466.4423600.35
23844.3923899.1824212.9524397.23 24710.824934.3125187.6225316.7525589.93 25773.7
26046.6726170.6926504.0326598.8126743.4726868.1827112.9527282.9527502.9527707.25
27846.6627995.6728099.9728333.4128562.21 28681.628786.0728875.6129284.1229518.57
29882.7130261.8430881.36 31091.231261.0631350.9931405.9531490.8831670.7431700.93
31709.93 31714.131771.0331825.7831827.2331837.1131875.2531934.7632261.1232330.15
32715.1532770.1133039.71 33174.633403.91 33533.333737.3433847.2234057.0534196.95
34366.8134546.6734791.4834906.3934976.3435106.2335331.0635595.8535690.7835835.66
36125.4436325.2837154.6337524.3437734.1837953.6538246.8138525.06
  371.09  371.75  371.94  372.62  372.42  371.54  371.64  371.35   371.4  371.68
  371.45  371.11  371.06  371.37  371.12  371.18  371.65   372.6  373.99  376.73
  382.54  386.22  388.61 389.391 391.454 392.793 392.951  392.97 395.075 395.087
 393.298 393.297 393.155 392.379 389.885  385.68  381.87  376.64  374.76  374.03
  373.52  373.82   373.5  373.48  373.94  373.24   373.2  373.69  373.45   373.9
  373.86  373.49   373.3  373.01  373.15  374.16  375.51  376.07  375.87  377.16
  377.34  376.86  376.99  376.02  373.47  372.63  372.33  372.49  372.72  372.39
  372.29  372.33   372.9  373.22  373.66  373.63  374.48  376.43  381.83 384.499
 385.556 385.556 385.553 385.551 385.551 384.391  382.58  382.95  383.46     384
  384.77   385.4  385.98  386.27  386.37  386.62  387.43  387.61  388.37  389.06
  390.15  391.03   392.9  394.55  396.31  401.32  413.53  435.48  438.88  441.98
  442.49  442.24  443.15  445.41  447.38  450.43  455.02  459.92
                                                         385.907  388.33 388.319
 386.254
          381.59 381.805 381.415
Pier Skew, UpSta & Num, DnSta & Num=  ,20897.1, 3 ,20876.1, 3 , 0 , 0 , 0 ,,
       9       3       3
   379.5     380     389
       9       3       3
   379.5     380     389
Pier Skew, UpSta & Num, DnSta & Num=  ,20981.4, 3 ,20960.5, 3 , 0 , 0 , 0 ,,
       9       3       3
   379.5     380     389
       9       3       3
   379.5     380     389
Pier Skew, UpSta & Num, DnSta & Num=  ,21065.8, 3 ,21044.9, 3 , 0 , 0 , 0 ,,
       9       3       3
   379.5     380     389
       9       3       3
   379.5     380     389
Pier Skew, UpSta & Num, DnSta & Num=  ,21150.2, 3 ,21129.2, 3 , 0 , 0 , 0 ,,
       9       3       3
   379.5     380     389
       9       3       3
   379.5     380     389
Pier Skew, UpSta & Num, DnSta & Num=  ,21234.6, 3 ,21213.6, 3 , 0 , 0 , 0 ,,
       9       3       3
   379.5     380     389
       9       3       3
   379.5     380     389
Pier Skew, UpSta & Num, DnSta & Num=  ,21318.9, 3 ,21298, 3 , 0 , 0 , 0 ,,
       9       3       3
   379.5     380     389
       9       3       3
   379.5     380     389
Pier Skew, UpSta & Num, DnSta & Num=  ,21403.3, 3 ,21382.3, 3 , 0 , 0 , 0 ,,
       9       3       3
   379.5     380     389
       9       3       3
   379.5     380     389
Pier Skew, UpSta & Num, DnSta & Num=  ,21487.7, 3 ,21466.7, 3 , 0 , 0 , 0 ,,
       9       3       3
   379.5     380     389
       9       3       3
   379.5     380     389
Pier Skew, UpSta & Num, DnSta & Num=  ,21572.1, 3 ,21551.1, 3 , 0 , 0 , 0 ,,
       9       3       3
   379.5     380     389
       9       3       3
   379.5     380     389
Pier Skew, UpSta & Num, DnSta & Num=  ,21656.4, 3 ,21635.5, 3 , 0 , 0 , 0 ,,
       9       3       3
   379.5     380     389
       9       3       3
   379.5     380     389
Pier Skew, UpSta & Num, DnSta & Num=  ,21740.8, 3 ,21719.8, 3 , 0 , 0 , 0 ,,
       9       3       3
   379.5     380     389
       9       3       3
   379.5     380     389
Pier Skew, UpSta & Num, DnSta & Num=  ,21825.2, 3 ,21804.2, 3 , 0 , 0 , 0 ,,
       9       3       3
   379.5     380     389
       9       3       3
   379.5     380     389
Pier Skew, UpSta & Num, DnSta & Num=  ,21909.5, 3 ,21888.6, 3 , 0 , 0 , 0 ,,
       9       3       3
   379.5     380     389
       9       3       3
   379.5     380     389
Pier Skew, UpSta & Num, DnSta & Num=  ,21993.9, 3 ,21973, 3 , 0 , 0 , 0 ,,
       9       3       3
   379.5     380     389
       9       3       3
   379.5     380     389
Pier Skew, UpSta & Num, DnSta & Num=  ,22078.3, 3 ,22057.3, 3 , 0 , 0 , 0 ,,
       9       3       3
   379.5     380     389
       9       3       3
   379.5     380     389
Pier Skew, UpSta & Num, DnSta & Num=  ,22162.7, 3 ,22141.7, 3 , 0 , 0 , 0 ,,
       9       3       3
   379.5     380     389
       9       3       3
   379.5     380     389
Pier Skew, UpSta & Num, DnSta & Num=  ,22247, 3 ,22226.1, 3 , 0 , 0 , 0 ,,
       9       3       3
   379.5     380     389
       9       3       3
   379.5     380     389
Pier Skew, UpSta & Num, DnSta & Num=  ,22331.4, 3 ,22310.4, 3 , 0 , 0 , 0 ,,
       9       3       3
   379.5     380     389
       9       3       3
   379.5     380     389
Pier Skew, UpSta & Num, DnSta & Num=  ,22415.8, 3 ,22394.8, 3 , 0 , 0 , 0 ,,
       9       3       3
   379.5     380     389
       9       3       3
   379.5     380     389
Pier Skew, UpSta & Num, DnSta & Num=  ,22500.2, 3 ,22479.2, 3 , 0 , 0 , 0 ,,
       9       3       3
   379.5     380     389
       9       3       3
   379.5     380     389
Pier Skew, UpSta & Num, DnSta & Num=  ,22584.5, 3 ,22563.6, 3 , 0 , 0 , 0 ,,
       9       3       3
   379.5     380     389
       9       3       3
   379.5     380     389
Pier Skew, UpSta & Num, DnSta & Num=  ,22668.9, 3 ,22647.9, 3 , 0 , 0 , 0 ,,
       9       3       3
   379.5     380     389
       9       3       3
   379.5     380     389
Pier Skew, UpSta & Num, DnSta & Num=  ,22753.3, 3 ,22732.3, 3 , 0 , 0 , 0 ,,
       9       3       3
   379.5     380     389
       9       3       3
   379.5     380     389
Pier Skew, UpSta & Num, DnSta & Num=  ,22837.6, 3 ,22816.7, 3 , 0 , 0 , 0 ,,
       9       3       3
   379.5     380     389
       9       3       3
   379.5     380     389
Pier Skew, UpSta & Num, DnSta & Num=  ,31779.08, 2 ,31736.64, 2 , 0 , 0 , 0 ,,
       1       1
     372  388.33
       1       1
     372  388.33
Pier Skew, UpSta & Num, DnSta & Num=  ,31809.23, 2 ,31766.94, 2 , 0 , 0 , 0 ,,
       1       1
     372  388.33
       1       1
     372  388.33
Pier Skew, UpSta & Num, DnSta & Num=  ,31839.11, 2 ,31796.63, 2 , 0 , 0 , 0 ,,
       1       1
     372  388.33
       1       1
     372  388.33
Abutment Skew #Up #Dn= , 2 , 2
20811.37 20835.3
 384.608 374.681
20792.17 20816.1
 384.608 374.681
Abutment Skew #Up #Dn= , 2 , 2
22885.3222922.99
 370.917  385.16
22822.0522859.72
 370.917  385.16
BR Coef= 1 , 1 , 1 ,0.9, 0 ,,,0.8,-1,1.33,0,
WSPro=,,,, 1 ,,,, 0 ,,,, 0 ,,,,-1 ,-1 ,-1 , 0 , 0 , 0 , 0 , 0
BR Coef=-1 , 1 , 1 ,0.9, 0 ,,,0.8,0,1.33,0,
WSPro=,,,, 1 ,,,, 0 ,,,, 0 ,,,,-1 ,-1 ,-1 , 0 , 0 , 0 , 0 , 0
Culvert=2,10,10,116.9,0.12,0.4,1,8,1,357.54,17714.62,356.85,17714.62,Culvert #1  , 0 ,53
17714.6217714.62
BC Culvert Barrel=1,Barrel #1,0
Culvert Bottom n=0.12
Culvert=2,4,8,37.9,0.12,0.4,1,8,1,366.32,26883.44,365.5,26883.44,Culvert #2  , 0 ,87.3
26883.4426883.44
BC Culvert Barrel=1,Barrel #1,0
Culvert Bottom n=0.12
BC Mult= 1 ,0,16967.1,0,16967.1
BC Mult= 2 ,16967.1,20700,16967.1,20700
BC Mult= 3 ,18000,26250,18000,26250
BC Mult= 2 ,23100,31600,23100,31550
BC Mult= 3 ,27500,33300,27500,33300
BC Mult= 1 ,33300,38526.05,33300,38526.05
BR U #Sta/Elev= 331
       0  453.62   64.55  450.66  160.83  449.12  248.18  447.05  365.68  442.01
  447.37  438.45  577.42  435.53  676.95  439.44  828.84  442.47  953.54  442.08
 1097.88  440.43 1163.59  439.25 1334.27  431.86 1499.33  428.88 1559.84  424.64
 1660.95  421.11  1753.8  421.53  1813.9  422.64 1896.37  424.54 2159.15  423.49
 2279.89  419.94 2431.77   418.4 2688.34  413.11 2748.07  410.24 2875.18   406.9
  3158.9  402.33 3403.53  399.34 3526.56  399.75 3728.31  398.79 3876.97   398.5
 3911.09  399.32 4147.93  397.52 4235.61  395.38 4413.55  394.27 4628.14  391.14
 4815.81   389.2 5030.85  389.21 5136.52   388.1 5269.45  385.48 5467.16  382.94
 5720.62  377.04 6164.93  375.72 6979.01  369.64 7530.59  367.75  7667.6  368.74
 7757.38  369.41 7879.55  369.99 8035.15     372 8601.39  370.13 8730.08  370.84
 9117.16  370.59 9223.15  371.81 9392.71  372.03 9448.66  369.83 9634.26   368.9
 9919.34  367.6110337.18  367.8810468.35  368.42 10583.3  368.76 10818.6  369.17
11060.87  369.5311184.64  370.4311444.65  369.2311562.58   369.211791.21  368.75
11920.76  367.0711974.63  366.9912068.36  366.51 12163.7  366.5912293.25  366.91
 12369.9  367.34 12556.2  366.4712695.61  366.6412905.99  367.5513109.94  367.19
13249.16  366.9113425.13  366.8613497.55   367.113597.07  366.9313752.17  367.52
13901.48  367.3614140.74  367.2214232.28  367.7814278.19  367.9914423.34  365.41
14510.84  364.5714609.23  363.5914902.19  360.6515027.22  359.7415143.99  360.88
15280.15  361.1115385.76  361.4415739.36  362.1816260.06  362.83   16299  362.72
16389.96  361.6716493.95  360.8616648.16  361.4816719.16  363.0716751.25  364.93
16814.31  364.6616930.85  364.48 16967.1  371.0917102.18   371.117188.86  370.95
17250.11  369.8217349.79   369.117485.62  369.6117563.63  370.6217609.26 371.937
17629.03 361.27517650.27 358.21417658.06 358.03817709.52  357.5417714.52  357.54
17719.52  357.5417725.74 359.53317735.33 362.56817750.23  368.9117776.93 370.471
17840.08  369.9717897.26  371.2818127.61  369.6618376.45  368.3418608.66   367.8
18714.84  368.2718976.24  368.5519121.04  369.0919429.69  369.1419715.66  369.04
19905.13  368.8720143.17  369.7520373.86  369.6120561.12  368.5520703.97  368.94
20751.97  370.7820781.42  374.52 20798.8  382.21 20812.7  383.8420832.02  373.95
20874.65  371.0320893.23  361.3120933.64  361.2520968.12  373.5121039.34  371.81
21205.05  370.79 21354.2  370.6121406.73  371.2221583.42  370.0121652.75  370.91
21758.14  371.6821773.35  367.2221774.76  348.1621778.22  337.5421778.85 336.094
21791.77 335.14521795.42 334.75121801.77 333.55221805.17 331.33521808.69 330.437
21812.34 329.69621816.06 330.29521819.89 331.54921823.68 332.46821831.33 333.796
21835.05 334.77221838.68 335.41421842.17 336.39421848.98 337.73421852.27 338.094
21858.94 339.20621868.44 340.94721872.12  341.5921892.63   341.621951.65  348.47
21984.61  357.8722013.55  358.6622024.35  369.6822029.45  372.3122072.81  370.42
22174.81  371.7922418.75  368.8922558.69  369.5222638.76  370.3522781.65  369.94
22842.46  369.0522863.36  365.3422925.66     38322930.59  383.1422945.69  380.94
22969.32  370.3222993.09  364.6123015.38  363.4223044.61  371.9223159.08  369.09
23326.21  368.5423507.39  369.4123712.23   369.423779.38  370.0323876.33  369.44
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BR U #Mann= 14
       0     .08  365.68     .07 2431.77      .1 4147.93     .06 9634.26      .1
17840.08     .0620703.97      .121773.35    .05522024.35      .122993.09     .05
26879.44      .132104.46     .0635586.17     .0837082.52     .06
BR D #Sta/Elev= 290
       0  448.92    58.2  450.14  256.68     444   448.5  436.02  605.26  431.64
  715.63   434.1  842.01  435.68  977.45  435.06 1123.33  432.75 1202.98  432.22
 1364.91  428.85 1566.53   423.7 1715.45  418.61 1806.63   416.2 1856.47  414.17
 1999.27  411.63 2245.45  407.84  2341.8  407.11 2382.59  406.47 2722.27  403.33
 2875.66  401.21 2918.45  401.07 2972.17  400.42 3042.51  400.33 3089.38  401.36
 3449.92  399.66 3629.24  398.16  3802.1  396.43 3900.85  395.11  4018.4  393.68
 4207.22  393.26  4280.1  392.07    4524  391.37 4690.87  389.07 4942.93  387.34
 5310.37   384.2 5434.24  382.57 5680.67  374.68 5708.28  374.68 5796.94  373.46
 5854.96  372.88 5944.17  370.51 6030.98  369.91 6162.02  371.21 6422.37  371.25
  6603.8  369.89 6685.55  369.19 6801.02  368.88 6860.41  370.19 6968.75  370.43
 7171.36  369.45 7260.25  369.94 7389.35  369.31 7536.71  370.36 7702.15  369.13
 8017.74  368.37 8307.39  367.99 8437.04  368.66 8719.91  369.77 8956.64  369.62
 9021.46  370.36 9296.75  370.43 9352.86   369.4 9485.07  368.76  9622.6  367.19
 9705.32  367.69 9812.65  369.84  9994.4     36910091.49  368.5510192.43  367.39
10362.56  368.3510452.15   367.810542.24  368.3710596.46  370.8910712.99  371.03
 10814.7  370.2411031.58  370.8411086.11  372.02 11248.5  371.0611393.47   370.9
11457.67  371.5511654.92  371.85 11809.1  370.1311898.59  367.5512011.54  366.53
12131.34  367.1812331.01  367.2112536.96  367.9112653.59  367.4912765.34  366.47
 12875.6  367.1912983.38  368.9413126.48  369.06 13290.8  368.42 13427.1  368.05
13602.54  368.21 13698.2  366.3713733.84  366.3313866.87  366.55 13982.7  367.33
14051.34  367.2714179.11  366.8414282.76  365.2314427.82   366.114491.96  365.69
14610.83  365.7114726.91  360.6814914.23  360.9915134.87   364.415174.05  366.12
15426.26   367.815642.38  365.9415768.45  367.4215970.26  368.7616051.54  368.58
16161.63  368.5616213.67  367.1316297.39  367.2816363.28  366.5916587.29  368.78
16648.37  369.5616707.15  369.2316824.21   369.816934.58  368.6417085.91  370.01
17222.82   371.117268.49  370.1917385.75  368.81 17508.9  369.5117598.37   370.1
17605.19 370.14117612.21 369.39417643.71 356.88917662.75 356.31617706.55 356.848
17709.62 356.84817719.62 356.84817722.57 364.97317727.78 367.25317734.13 369.575
 17743.5 370.868 17761.5 371.34517777.33 371.11817789.84  369.56 18045.1  368.63
18735.09  367.6318909.54  367.5719182.61  368.31 19506.3  367.9819853.68  368.43
19917.22  368.0820201.34   368.520456.88  367.2120518.15  369.4820550.89  373.17
 20697.1  373.8720768.04  374.6420793.49  383.8220809.73  375.1420902.03   370.6
20950.47  364.6921054.55  366.6221115.25   371.921361.54  371.2721441.68  371.28
21625.58  370.9121662.74  372.2421758.35  370.8321761.57  368.8721789.42     353
21797.69  337.1521875.63 334.83521888.23 333.10221908.88  331.6821912.42 331.225
21915.96  330.7621919.58  329.7221923.28  330.5121926.95   331.721930.63  331.99
21934.15  332.3321940.94 333.451 22010.3 335.56722027.26  358.9922043.92  368.98
22049.54  371.5522197.81  372.1522215.16  370.9722692.79  369.6722715.05  364.96
22833.78  372.4622860.91  383.2722865.83  383.3222934.46  378.0422975.62  376.02
23109.77  370.1323161.06  369.2723230.58  369.4723401.46  369.1823705.36  369.78
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BR D #Mann= 17
       0     .08  256.68     .07 2382.59      .1 3900.85     .0610192.43      .1
11031.58     .0611457.67     .0611898.59      .117598.37     .06 20697.1      .1
21761.57    .05522043.92      .122975.62     .0527475.03      .132307.07     .06
33389.85     .05 35061.6     .06
BC Design=,, 0 ,, 0 ,,,,,,
BC Use User HTab Curves=0
BC User HTab FreeFlow(D)= 0

Type RM Length L Ch R = 1 ,186264  ,1855.44,1760.58,2233.35
BEGIN DESCRIPTION:
DS Bridge
LOB - Bois D'Arc, ROB - Dallas LID1/2
END DESCRIPTION:
XS GIS Cut Line= 6
2559871.226754126930085.983048982549405.948976346916467.92749342
2549284.746719396915622.477551292548268.687691616914265.27269018
2545644.989774956911704.508801292532761.29377277 6904841.7347546
#Sta/Elev= 30
       0  448.92  256.68     444 2382.59  406.47 3900.85  395.11  5715.6  371.09
10141.44  370.6511031.58  370.8411457.67  371.5511859.16  369.5816849.34  373.23
17208.86  358.9817256.36  374.3717558.05  357.03 20653.4   375.821761.57  368.87
21831.52 334.34321919.58  329.7222043.92  368.9822975.62  376.0227475.03  371.89
29902.81  375.4130329.89  360.2330698.82  376.1531561.26  358.0231766.54  379.73
32307.07  382.0733443.98  384.8735049.96  395.3135720.62  437.6238066.94  448.16
#Mann= 17 ,-1 , 0
       0     .08       0  256.68     .07       0 2382.59      .1       0
 3900.85     .06       010141.44      .1       011031.58     .06       0
11457.67     .06       011859.16      .1       017558.05     .06       0
 20653.4     .15       021761.57    .055       022043.92     .15       0
22975.62     .05       027475.03      .1       032307.07     .06       0
33443.98     .05       035049.96     .06       0
Levee=-1,20792.77,383.68,0,,,,
#XS Ineff= 4 ,-1
       020792.77     400   22987   26714     373   27052   31574   372.5
   3196738066.94     383
Permanent Ineff=
       F       F       F       F
Bank Sta=21761.57,22043.92
XS Rating Curve= 0 ,0
Exp/Cntr=0.5,0.3

Type RM Length L Ch R = 1 ,184503  ,1141.76,2752.93,3502.22
BEGIN DESCRIPTION:
LOB - Bois D'Arc
ROB IFA station 27353.15: flow contraction due to natural high ground downstream
END DESCRIPTION:
XS GIS Cut Line= 4
2559572.852699236928131.371101242549158.807805166912562.74643566
2546939.363360716910618.301991212540024.241588126900006.37110124
#Sta/Elev= 30
       0  427.72 1075.28  427.13 2384.82  392.14 4513.55   368.7 5048.05  388.89
 5933.32  369.75 8231.53  382.28 9920.58  378.9311625.88  367.7514641.38  356.74
16553.76   369.617207.45   357.8 17381.7  376.6117415.02  358.4217676.22  356.63
19500.41  385.2519585.37  356.3320555.35  370.5920659.95  333.6620707.16  334.17
20767.44  369.9621487.21  369.3324838.63  365.3927289.81  351.3227541.37  379.56
27706.21  363.3828329.32  373.9129377.92  381.64 30890.8  421.0634347.37  442.07
#Mann= 14 ,-1 , 0
       0     .07       0 2384.82     .06       0 8231.53     .06       0
 9920.58     .06       011625.88      .1       014641.38     .06       0
16553.76     .15       020555.35    .055       020767.44     .15       0
21487.21     .05       024838.63      .1       028329.32     .06       0
29377.92     .05       0 30890.8     .06       0
Levee=-1,19500.41,385.25,0,,,,
#XS Ineff= 4 ,-1
       019500.41     400   22618   23802   372.6   2708327353.15   371.4
27353.1534347.37  387.54
Permanent Ineff=
       F       F       F       F
Bank Sta=20555.35,20767.44
XS Rating Curve= 0 ,0
Exp/Cntr=0.3,0.1

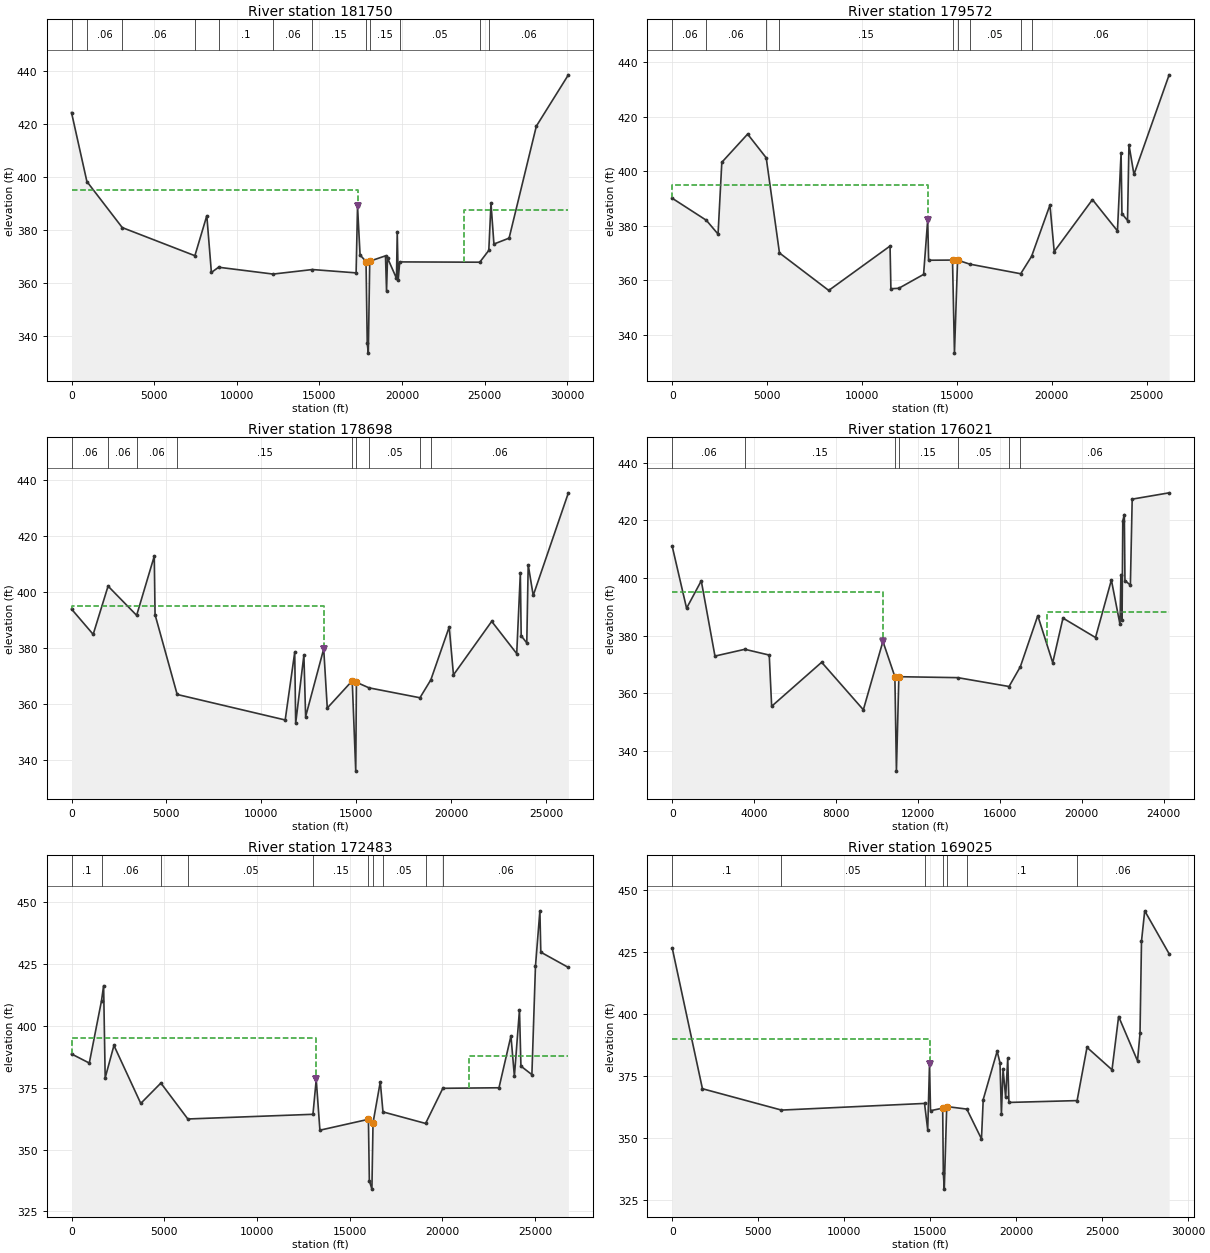
Type RM Length L Ch R = 1 ,181750  ,2178.07,2178.36,1237.92
BEGIN DESCRIPTION:
LOB - Bois D'Arc
ROB IFA station 23778.12: flow contraction due to natural high ground downstream
END DESCRIPTION:
XS GIS Cut Line= 4
2559575.33418071 6926100.72295312550454.46752738 6912496.2533801
2550002.664865346909181.624907882544471.167514056900441.00073088
#Sta/Elev= 30
       0  424.22  930.84  398.19 3070.86  380.81 7466.12   370.2 8187.52   385.3
 8464.59  363.87 8900.14  365.8512198.84  363.2714578.21  364.9817222.38  363.72
 17308.4  388.8417461.85  370.4717822.88  368.0117896.15  337.1317960.37  333.44
18047.38  368.1219001.08  370.1519063.98   356.819122.93  369.3519665.02  361.68
19711.52  379.2819771.51  361.0919861.27  367.8624706.16  367.7525251.92  372.21
25384.35  389.9225562.23   374.626480.27  376.8328128.73  419.0830068.09  438.45
#Mann= 12 ,-1 , 0
       0     .07       0  930.84     .06       0 3070.86     .06       0
 7466.12     .06       0 8900.14      .1       012198.84     .06       0
14578.21     .15       017822.88    .055       018047.38     .15       0
19861.27     .05       024706.16      .1       025251.92     .06       0
Levee=-1,17308.4,388.84,0,,,,
#XS Ineff= 2 ,-1
       0 17308.4     39523778.1230068.09  387.54
Permanent Ineff=
       F       F
Bank Sta=17822.88,18047.38
XS Rating Curve= 0 ,0
Exp/Cntr=0.3,0.1

Type RM Length L Ch R = 1 ,179572  ,766.97,874.08,934.72
BEGIN DESCRIPTION:
LOB - Bois D'Arc
ROB IFA station 19901.66: flow contraction due to natural high ground
END DESCRIPTION:
XS GIS Cut Line= 4
2559148.762421456923029.18128644 2552593.20686596911473.62573088
2551232.095754796908890.29239755 2546093.20686596900334.73684199
#Sta/Elev= 30
       0  390.02 1798.58  381.93 2413.01  376.87 2611.82  403.22  3971.5  413.57
 4951.44  404.86 5649.14  369.95 8245.78   356.211476.02  372.4911520.72  356.82
 11935.7  356.9813243.16  362.0813460.08  382.12 13508.2  367.2814767.13  367.34
14869.71  333.1915033.64  367.3215676.41  365.8518360.13  362.3218932.91  368.69
19901.66  387.5420125.82  370.4622140.59  389.5323458.89  378.0423649.71  406.69
23694.22  384.41   23989  381.8524063.88   409.724327.84  398.75 26181.2  435.32
#Mann= 9 ,-1 , 0
       0     .06       0 1798.58     .06       0 4951.44     .06       0
 5649.14     .15       014767.13    .055       015033.64     .15       0
15676.41     .05       018360.13      .1       018932.91     .06       0
Levee=-1,13460.08,382.12,0,,,,
#XS Ineff= 2 ,-1
       013460.08     39519901.66 26181.2  387.54
Permanent Ineff=
       F       F
Bank Sta=14767.13,15033.64
XS Rating Curve= 0 ,0
Exp/Cntr=0.3,0.1

Type RM Length L Ch R = 1 ,178698  ,1580.48,2677.02,409.08
BEGIN DESCRIPTION:
LOB - Bois D'Arc
ROB IFA station 19901.66: flow blocked due to natural high ground
END DESCRIPTION:
XS GIS Cut Line= 5
2559490.928754236922857.666574542552647.425477186909725.03967755
2552552.475919656909494.523410582551369.969250626907246.30085465
2546356.22769924  6900280.049342
#Sta/Elev= 30
       0  393.92 1141.95   384.9 1926.79  402.09 3431.82  391.67 4360.95  412.76
 4402.37  391.92 5567.51  363.4911258.94   354.411761.14   378.511812.03  353.22
12245.06  377.5412336.06   355.613289.19  379.7313476.76  358.6514791.64  368.36
 14976.7  336.1815012.84  367.8315676.41  365.8518360.13  362.3218932.91  368.69
19901.66  387.5420125.82  370.4622140.59  389.5323458.89  378.0423649.71  406.69
23694.22  384.41   23989  381.8524063.88   409.724327.84  398.75 26181.2  435.32
#Mann= 9 ,-1 , 0
       0     .06       0 1926.79     .06       0 3431.82     .06       0
 5567.51     .15       014791.64    .055       015012.84     .15       0
15676.41     .05       018360.13      .1       018932.91     .06       0
Levee=-1,13289.19,379.73,0,,,,
#XS Ineff= 2 ,-1
       013289.19     39519901.66 26181.2  387.54
Permanent Ineff=
       F       F
Bank Sta=14791.64,15012.84
XS Rating Curve= 0 ,0
Exp/Cntr=0.3,0.1

Type RM Length L Ch R = 1 ,176021  ,2531.23,3537.5,700.82
BEGIN DESCRIPTION:
LOB - Bois D'Arc
ROB IFA station 18302.14: flow expansion due to natural high ground
END DESCRIPTION:
XS GIS Cut Line= 5
2560588.416356656919955.471795722554947.803754236911347.82861158
2554613.081532016910254.773056032553119.24968998 6909210.7495735
2546787.65131034 6900195.8479531
#Sta/Elev= 30
       0   410.9   699.4  389.49 1417.12     399 2086.31   372.9 3545.85  375.25
 4738.33  373.25 4855.57  355.49 7298.32  370.75 9335.43  354.28 10291.1     378
10875.75  365.7410950.68  333.0111069.77  365.7513947.64  365.4216453.32  362.35
17004.74  369.21 17856.7  386.9118586.62   370.619087.61  386.0720677.71  379.33
21452.25  399.2821873.21  383.8621917.79  401.1421974.12  385.3622008.61  419.78
22084.37  421.9722114.88  399.0922380.36   397.522468.47  427.3124273.08   429.5
#Mann= 7 ,-1 , 0
       0     .06       0 3545.85     .15       010875.75    .055       0
11069.77     .15       013947.64     .05       016453.32      .1       0
17004.74     .06       0
Levee=-1,10296.09,378,0,,,,
#XS Ineff= 2 ,-1
       010296.09     39518302.1424273.08  388.02
Permanent Ineff=
       F       F
Bank Sta=10875.75,11069.77
XS Rating Curve= 0 ,0
Exp/Cntr=0.3,0.1

Type RM Length L Ch R = 1 ,172483  ,1181.15,3458.81,1936.55
BEGIN DESCRIPTION:
LOB - Bois D'Arc
ROB IFA station 21413.04: flow expansion due to natural high ground
END DESCRIPTION:
XS GIS Cut Line= 5
2565182.616588126919946.716008662556391.389458526910099.22201427
2554487.454273346909257.208125382551870.984643686906612.51461977
2547148.762421456900418.07017533
#Sta/Elev= 30
       0  388.58  959.04   384.9 1619.23  410.13  1731.1  416.16 1815.83  378.93
 2287.92  392.01 3734.32  368.61 4818.85  376.83 6272.44  362.33 13018.8  364.22
13195.63  378.2713393.67   357.8 16009.4   362.216059.69  337.3716197.71  334.02
16257.81  360.7516649.41  377.3216794.36  365.1919091.59  360.5320022.87  374.71
23050.08  374.9323695.19  395.8623880.43  379.5724155.03  406.4524233.05  383.67
24823.93  380.2325016.31  423.9125255.74  446.3425304.65  429.6626791.89  423.49
#Mann= 10 ,-1 , 0
       0      .1       0 1619.23     .06       0 4818.85      .1       0
 6272.44     .05       0 13018.8     .15       0 16009.4    .055       0
16257.81     .15       016794.36     .05       019091.59      .1       0
20022.87     .06       0
Levee=-1,13195.63,378.27,0,,,,
#XS Ineff= 2 ,-1
       013195.63     39521413.0426791.89  387.75
Permanent Ineff=
       F       F
Bank Sta=16009.4,16257.81
XS Rating Curve= 0 ,0
Exp/Cntr=0.3,0.1

Type RM Length L Ch R = 1 ,169025  ,2540.16,1939.9,813.21
BEGIN DESCRIPTION:
LOB - Bois D'Arc
ROB IFA station 24114.59: flow expansion due to natural high ground
END DESCRIPTION:
XS GIS Cut Line= 5
2567543.277467766920656.860684622557438.775976456909634.40268566
2556412.387087566907779.541574552549440.672143686903262.27156422
2547322.616588126900463.66045311
#Sta/Elev= 30
       0  426.44 1754.32  369.86 6351.27  361.2614668.24  363.9414853.24  353.36
14957.67  379.6315017.11  361.02 15723.6  362.0415760.87  336.0915816.71  329.44
 15958.5  362.68 17127.3  361.6617979.41  349.6518080.67  365.5218889.65  384.95
19055.78  380.2919138.18  359.6719233.91  377.7519385.28  366.4119506.69  382.12
19574.07  364.3423539.21  365.0824114.59  386.5125569.27  377.4925952.78  398.93
27051.51  381.0927197.13  392.1327283.32  429.2327470.32  441.4828889.98  424.18
#Mann= 7 ,-1 , 0
       0      .1       0 6351.27     .05       014668.24     .15       0
 15723.6    .055       0 15958.5     .15       0 17127.3      .1       0
23539.21     .06       0
Levee=-1,14957.67,379.63,0,,,,
#XS Ineff= 2 ,-1
       014957.67     39024114.5928889.98  386.51
Permanent Ineff=
       F       F
Bank Sta=15723.6,15958.5
XS Rating Curve= 0 ,0
Exp/Cntr=0.3,0.1

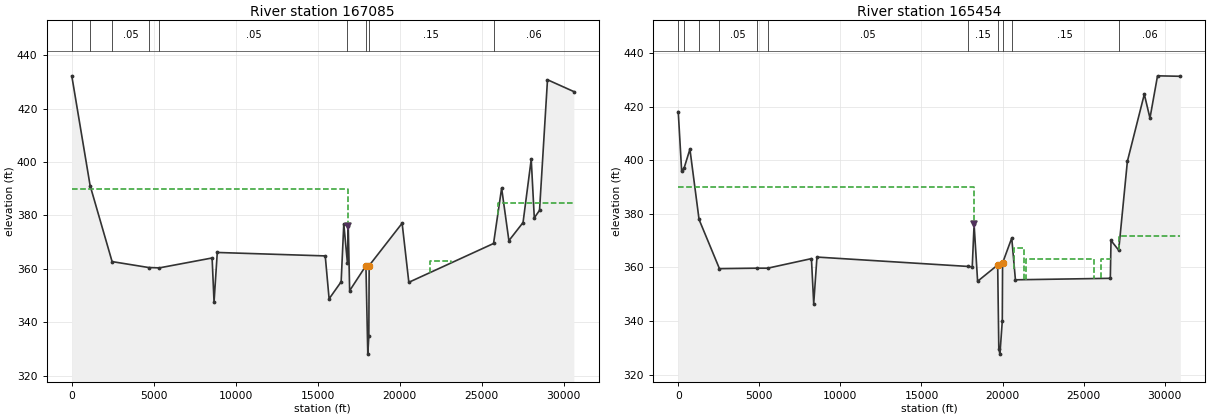
Type RM Length L Ch R = 1 ,167085  ,1087.43,1630.75,1236.82
BEGIN DESCRIPTION:
LOB - Bois D'Arc
ROB IFA station 25988.24: flow expansion due to natural high ground
END DESCRIPTION:
XS GIS Cut Line= 5
2570255.574362936919925.554734122558876.389719376907504.55343791
2556828.766274576906773.46139785 2549444.14436596903060.88267533
 2547409.58254826900405.39565756
#Sta/Elev= 30
       0  432.25 1118.92  391.17 2460.13   362.7 4683.68  360.49 5344.28  360.35
 8561.69  364.06 8679.91  347.56 8876.83  366.1215463.17  364.8315699.37  348.77
16434.24  355.1416595.36  376.8116816.95  362.1816867.19  375.9816952.58  351.81
17946.58  361.1718059.61  328.0618122.12  334.7618143.76  361.2220154.42  377.07
20563.17  354.9525732.03  369.4826224.28  390.22 26668.4  370.5427530.81  377.32
28030.26  400.9828217.71  379.07 28536.5  381.8929022.37  430.7830630.34  426.35
#Mann= 9 ,-1 , 0
       0     .07       0 1118.92      .1       0 2460.13     .05       0
 4683.68      .1       0 5344.28     .05       016816.95     .15       0
17946.58    .055       018143.76     .15       025732.03     .06       0
Levee=-1,16867.19,375.98,0,,,,
#XS Ineff= 3 ,-1
       016867.19     390   21863   23129     36325988.2430630.34   384.6
Permanent Ineff=
       F       F       F
Bank Sta=17946.58,18143.76
XS Rating Curve= 0 ,0
Exp/Cntr=0.5,0.3

Type RM Length L Ch R = 1 ,165454  ,224.76,250.22,261.43
BEGIN DESCRIPTION:
US Bridge
LOB - Bois D'Arc
END DESCRIPTION:
XS GIS Cut Line= 6
2571064.517439086919575.161277432566003.753550186914334.01544409
2565110.003550176912511.793221862558975.281327946906277.24461073
2555912.086883486905121.68905517 2547692.46882796900176.72377738
#Sta/Elev= 30
       0  418.17  211.42  395.93  370.27  397.26  720.46  404.15 1284.49  377.89
 2541.58  359.53 4832.33  359.715517.479  359.718214.539  363.28 8355.23  346.47
 8555.71  363.8617874.37  360.36 18132.3  360.19 18246.3  376.0918463.09  354.82
19701.56   360.9 19770.9 329.645 19839.7 327.61719985.68  340.0420003.09  361.65
20568.99  370.9820795.05  355.3726647.99  355.9326690.77  370.0627164.25  366.42
   27700  399.6128744.54  424.6729092.81  415.7529559.32  431.5430964.49  431.37
#Mann= 11 ,-1 , 0
       0      .1       0  370.27     .07       0 1284.49      .1       0
 2541.58     .05       0 4832.33      .1       05517.479     .05       0
17874.37     .15       019701.56    .055       020003.09     .15       0
20568.99     .15       027164.25     .06       0
Levee=-1,18246.3,376.09,0,,,,
#XS Ineff= 5 ,-1
       0 18246.3     390   20738   21301  367.09   21423   25662  363.03
   2607126690.77   363.3   2716530964.49  371.69
Permanent Ineff=
       F       F       F       F       F
Bank Sta=19701.56,20003.09
XS Rating Curve= 0 ,0
Exp/Cntr=0.5,0.3