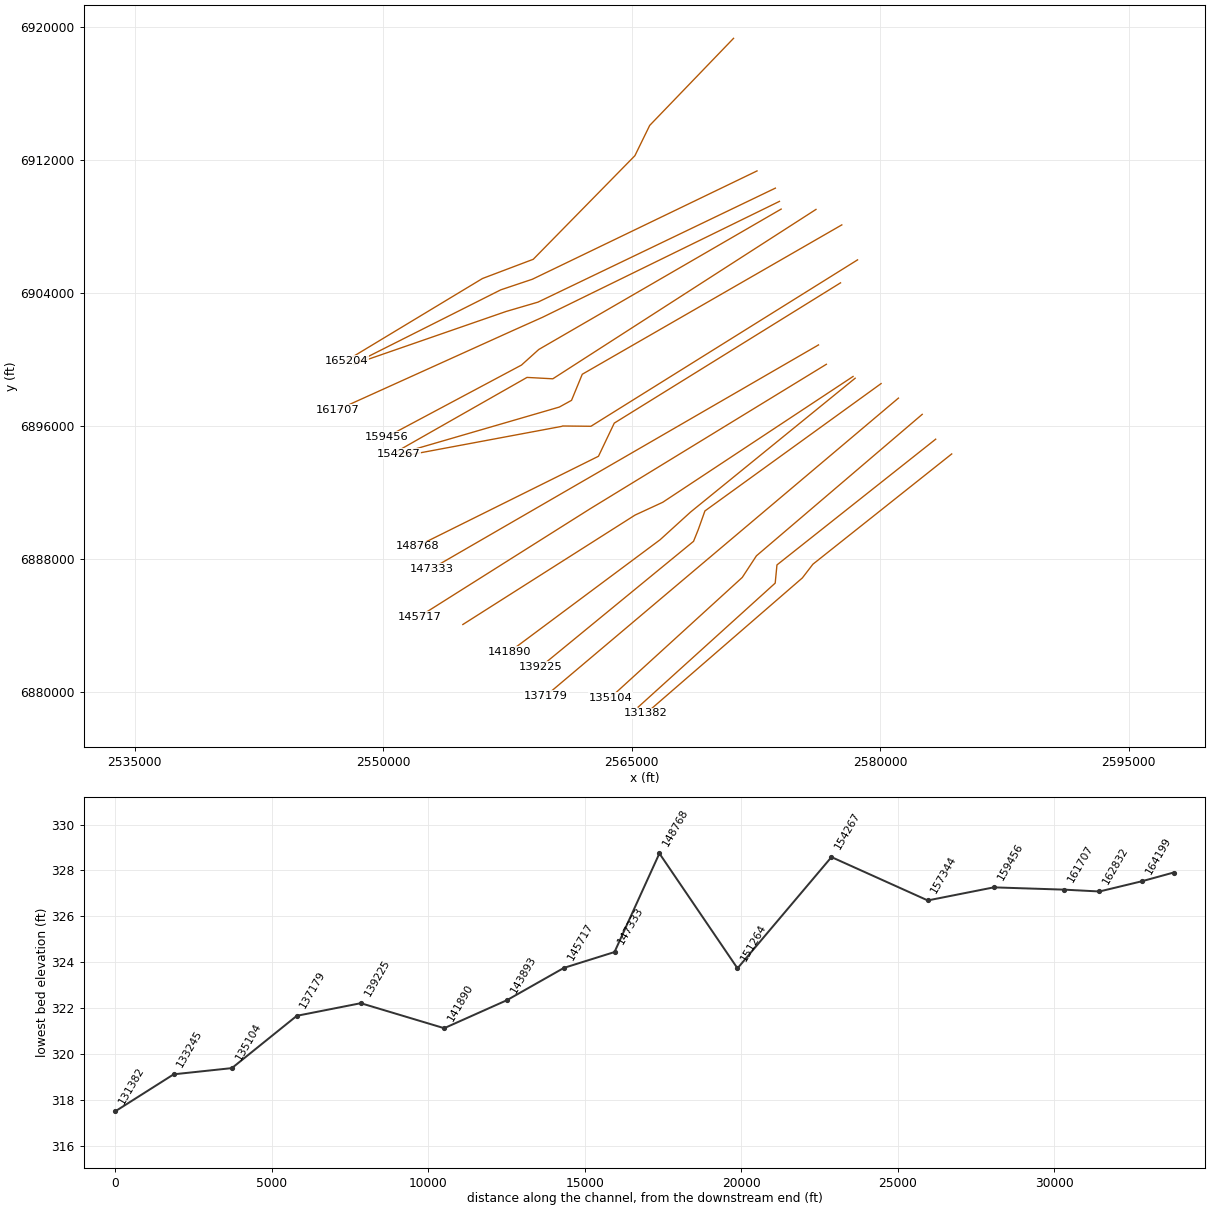
HEC-RAS study TR_FEMA.prj: Trinity_River_FEMA

--- TR_FEMA.g08 (geometry) --- (continued)

Type RM Length L Ch R = 4 ,165325  ,,,
BEGIN DESCRIPTION:
East Malloy Bridge Road - Bridge geometry per Compass survey dated July 2018.  Road deck supplemented with Lidar data outside of the surveyed bridge/culvert openings.
END DESCRIPTION:
Node Name=East Malloy Brid
Bridge Culvert--1,0,-1,-1, 0
Deck Dist Width WeirC Skew NumUp NumDn MinLoCord MaxHiCord MaxSubmerge Is_Ogee
105,45,2.6,0, 314, 471, , , 0.98, 0, 0,0,,
       0   19.93   84.68  179.33   214.2  268.99  283.93  303.86  353.67  403.48
  428.39  438.35   453.3  468.24  483.18  547.94  582.81  622.66  697.38  732.23
  772.03  886.48  896.43 1055.66 1165.12 1259.66 1289.52 1349.23 1394.01 1423.87
 1473.62 1513.43 1578.12 1632.85 1677.76 1727.72 1807.66 1852.62 1927.57 2002.51
 2062.46 2102.43 2167.38 2237.33 2312.27 2467.15 2512.11 2612.03 2681.98 2746.93
 3416.41 3641.23 3766.13 3975.97 4310.71 4400.64 4720.39 4760.36 4885.26 5130.07
 5779.56 5824.52 6219.21 6349.11  6623.9 6698.84 6738.81 7123.37 7207.09 7276.03
 7370.46 7455.04 7484.88 7544.56 7683.81 7827.93 7986.65 8045.89 8110.07 8137.37
 8170.47 8215.72 8218.37 8253.25 8291.31 8314.59 8397.46 8462.36 8512.28 8567.19
 8672.03 8761.73 8846.33 9109.41 9257.91 9432.15  9527.1 9637.03 9781.95 9841.91
 9986.8310086.7710131.7410171.7210291.6510571.4810796.3511036.2111750.7911960.67
 12255.512515.3412550.3212960.0813045.03 13093.713126.2213167.3813354.8513434.81
13509.7613599.7113999.4714059.4414274.3114389.2514434.2214504.1814734.0415083.84
15183.7815288.7215468.6115708.4715758.4415863.3815923.35 15998.316133.2216702.95
16747.9317182.7617257.7317582.6117642.5817672.5717747.5417827.0917915.9617985.09
18024.5918088.7518162.6618241.5118354.8418384.4318386.61 18386.718396.1918416.78
18418.9419858.1319876.1820587.5520588.9520602.8520613.2620613.8120679.7420804.54
20839.3320948.4720993.1221037.7721092.3421172.1521242.0421301.9521337.2821364.61
21371.8421436.3121624.7621763.8821883.1322042.1322355.5922639.4722978.1523092.57
23157.0423350.4423683.3823718.3123778.19 23823.123887.9723987.7824052.6524142.48
24192.3824322.1224391.9924431.9124466.8424511.75 24541.724601.58 24641.524666.45
24836.1224980.8425025.7525070.6625270.2725355.0425409.7625514.2325563.9725628.64
25653.5225723.1625738.0925782.8625790.8925800.1525809.1725871.4525963.4725981.65
26000.1926026.6126081.3326126.1126155.9526280.3226434.7126519.3826609.0226673.77
26713.61 26743.526803.3726853.33 26893.326899.8926920.6526983.3226984.5127059.57
27084.1727113.1327158.0927188.0727233.04   2727327312.9727377.9227392.9127437.88
27487.8427592.7527622.7327677.6927707.66 27787.627807.5927842.5627867.5427892.52
 27922.527967.4628002.4328052.3928112.3528147.3228192.2928247.2428277.2228357.16
28397.1228482.06   2855728621.9528721.8728756.8428796.8128851.7728921.7128991.66
29056.6129181.5129256.4529316.4129356.3829426.3229501.26 29586.229686.1229771.05
29796.0329905.9529940.9230005.8730100.7930285.6530375.5830420.5430660.3630715.31
 30730.330810.2430880.1830965.12
  415.25  414.33  410.95  405.91  403.99  402.14  401.43  400.94   399.4  398.19
  397.27  397.29  396.62  396.98  396.91  395.57  395.12  394.26  392.44  391.49
  390.58  388.39   388.1  385.69  384.06  382.26  381.55  380.56  379.54  378.62
  376.65   375.3  372.92  371.14  369.93  368.89  367.25  366.45   365.6  365.01
  364.33  364.04  363.76  363.18  362.82  362.56  362.31  361.88  361.71  361.75
  362.01  362.07  362.08  362.12  362.18  362.19  362.33  362.43  362.44  362.49
   362.5  362.66  362.74   362.8  362.82  362.84  362.93  363.23  363.46  363.84
  363.99  364.38  364.39  364.68  365.65  366.42  366.45  366.46  366.36 366.684
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 362.913 362.822 362.839 362.744  362.64
  381.89 389.471 389.241  380.15
                                                  364.31 364.519 364.472
                                                 372.393 372.846 372.835 372.264
       0   19.93   84.68  179.33   214.2  283.93  303.86  353.67  403.48  438.35
  468.24  483.18  547.94  582.81  622.66  697.38  732.23  772.03  886.48  896.43
 1055.66 1160.15 1165.12 1259.66 1289.52 1349.23 1394.01 1423.87 1473.62 1513.43
 1578.12 1632.85 1677.76 1727.72 1787.67 1807.66 1852.62 1927.57 2002.51 2062.46
 2102.43 2167.38 2237.33 2312.27 2467.15 2612.03 2681.98 2746.93 2821.87 3016.72
 3071.68 3126.63  3291.5 3416.41 3486.35 3521.32 3641.23 3766.13 3921.01 3975.97
 4030.93 4125.85 4175.81 4220.78 4310.71 4335.69 4400.64 4475.58 4595.48 4675.42
 4720.39 4760.36 4820.31 4885.26 5010.16  5090.1 5130.07 5249.97 5314.92 5399.86
  5474.8 5504.77 5564.73 5619.68 5664.65 5714.61 5779.56 5824.52 5839.51 5889.47
 5954.42  6109.3 6219.21 6349.11 6394.08 6439.04  6623.9 6698.84 6738.81  6883.7
 7028.58 7123.37 7207.09 7276.03 7370.46 7455.04 7484.88 7544.56 7683.81 7827.93
 7917.37 7986.65 8045.89 8110.07 8137.37 8161.24 8218.37  8234.9 8293.19 8314.59
 8352.53 8397.46 8462.36 8512.28 8567.19 8672.03 8761.73 8846.33 8965.77 9109.41
 9193.56 9257.91 9317.31 9402.17 9432.15  9527.1 9577.07 9637.03 9751.96 9781.95
 9841.91 9896.88 9986.8310061.7810086.7710131.7410141.7410171.72 10196.710291.65
10356.6110426.5710461.5510571.4810676.4210796.3510871.3110966.2510986.2411036.21
11096.1811206.1111281.0711331.0411381.0111455.97 11560.911595.8811645.8511715.81
11750.7911835.7411860.7311960.6712010.6412065.6112170.55 12255.512270.4912365.43
12435.3912515.3412550.3212620.2812725.2212850.1512890.1212960.0813045.03 13093.7
13126.2213167.3813234.9213354.8513379.8413434.8113509.7613569.7313599.71 13784.6
13829.5713909.5313999.4714059.4414174.3714274.3114329.2814369.2614389.2514424.23
14434.2214504.1814519.1714554.1514599.1214624.1114709.0614734.0414764.0314784.01
14858.9714868.9614898.9514963.9115028.8715063.8515083.8415113.8215183.7815268.73
15288.7215333.6915378.6715458.6215468.6115543.5715598.5415648.5115708.4715728.46
15758.4415773.4315863.3815913.3515923.3515978.31 15998.316063.2616133.22 16173.2
16248.1616263.1516278.14 16348.116408.0716543.01   1657816702.9516747.9316802.91
16897.8816982.8417117.7917182.7617257.7317302.7217382.6917442.6617462.6517517.63
17582.6117642.5817672.5717747.5417827.0917915.9617985.0918024.5918088.7518162.66
18241.5118354.8418374.5618389.3718413.3218413.41 18422.918443.4918445.6519884.84
19902.8920604.7220614.2620615.7120629.6220640.0320640.5720679.7420804.5420839.33
20948.4720993.1221037.7721092.3421172.1521242.0421301.9521337.2821364.6121371.84
21436.3121520.6121580.1221624.76 21729.121763.88 21873.221883.1322042.1322101.76
22186.25   2225122305.7822355.5922430.29   2250522639.4722699.2422773.9522833.71
 22888.522978.1523092.5723157.0423181.8323251.2623350.4423434.74   2352423628.48
23683.3823718.3123778.19 23823.123887.9723987.7824052.6524142.4824192.3824322.12
24391.9924431.9124466.8424511.75 24541.724601.58 24641.524666.4524731.3224836.12
24980.8425025.7525070.6625270.2725355.0425409.7625514.2325563.9725628.6425653.52
25723.1625738.0925782.8625790.89 25820.325852.0925932.9225988.5726002.8426059.12
26081.3326126.1126155.9526280.3226434.7126519.3826609.0226673.7726713.61 26743.5
26803.3726853.33 26893.326899.8926923.4126983.3227005.8227064.8727084.1727113.13
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                                         363.056 362.878   362.9 362.839
                                                                  381.89 389.471
 389.241  380.15  380.15
                                         364.499 364.557 364.315
                                 372.356  373.31 372.887  372.22
Pier Skew, UpSta & Num, DnSta & Num=  ,8205.21, 2 ,8205.21, 2 , 0 , 0 , 0 ,,
    1.75    1.75
     347 394.593
    1.75    1.75
     347 394.593
Pier Skew, UpSta & Num, DnSta & Num=  ,8249.341, 2 ,8249.341, 2 , 0 , 0 , 0 ,,
    1.75    1.75
     347 394.593
    1.75    1.75
     347 394.593
Pier Skew, UpSta & Num, DnSta & Num=  ,18533.1, 2 ,18559.8, 2 , 0 , 0 , 0 ,,
       3       3
  327.17 394.593
       3       3
  327.17 394.593
Pier Skew, UpSta & Num, DnSta & Num=  ,18647.2, 2 ,18673.9, 2 , 0 , 0 , 0 ,,
       3       3
  327.17 394.593
       3       3
  327.17 394.593
Pier Skew, UpSta & Num, DnSta & Num=  ,18761.4, 2 ,18788.1, 2 , 0 , 0 , 0 ,,
       3       3
  327.17 394.593
       3       3
  327.17 394.593
Pier Skew, UpSta & Num, DnSta & Num=  ,18875.5, 2 ,18902.2, 2 , 0 , 0 , 0 ,,
       3       3
  327.17 394.593
       3       3
  327.17 394.593
Pier Skew, UpSta & Num, DnSta & Num=  ,18989.6, 2 ,19016.3, 2 , 0 , 0 , 0 ,,
       3       3
  327.17 394.593
       3       3
  327.17 394.593
Pier Skew, UpSta & Num, DnSta & Num=  ,19103.8, 2 ,19130.5, 2 , 0 , 0 , 0 ,,
       3       3
  327.17 394.593
       3       3
  327.17 394.593
Pier Skew, UpSta & Num, DnSta & Num=  ,19217.9, 2 ,19244.6, 2 , 0 , 0 , 0 ,,
       3       3
  327.17 394.593
       3       3
  327.17 394.593
Pier Skew, UpSta & Num, DnSta & Num=  ,19332, 2 ,19358.7, 2 , 0 , 0 , 0 ,,
       3       3
  327.17 394.593
       3       3
  327.17 394.593
Pier Skew, UpSta & Num, DnSta & Num=  ,19446.2, 2 ,19472.9, 2 , 0 , 0 , 0 ,,
       3       3
  327.17 394.593
       3       3
  327.17 394.593
Pier Skew, UpSta & Num, DnSta & Num=  ,19560.3, 2 ,19587, 2 , 0 , 0 , 0 ,,
       3       3
  327.17 394.593
       3       3
  327.17 394.593
Pier Skew, UpSta & Num, DnSta & Num=  ,19674.5, 2 ,19701.2, 2 , 0 , 0 , 0 ,,
       3       3
  327.17 394.593
       3       3
  327.17 394.593
Pier Skew, UpSta & Num, DnSta & Num=  ,19788.6, 2 ,19815.3, 2 , 0 , 0 , 0 ,,
       3       3
  327.17 394.593
       3       3
  327.17 394.593
Pier Skew, UpSta & Num, DnSta & Num=  ,19902.7, 2 ,19929.4, 2 , 0 , 0 , 0 ,,
       3       3
  327.17 394.593
       3       3
  327.17 394.593
Pier Skew, UpSta & Num, DnSta & Num=  ,20016.9, 2 ,20043.6, 2 , 0 , 0 , 0 ,,
       3       3
  327.17 394.593
       3       3
  327.17 394.593
Pier Skew, UpSta & Num, DnSta & Num=  ,20131, 2 ,20157.7, 2 , 0 , 0 , 0 ,,
       3       3
  327.17 394.593
       3       3
  327.17 394.593
Pier Skew, UpSta & Num, DnSta & Num=  ,20245.1, 2 ,20271.8, 2 , 0 , 0 , 0 ,,
       3       3
  327.17 394.593
       3       3
  327.17 394.593
Pier Skew, UpSta & Num, DnSta & Num=  ,20359.3, 2 ,20386, 2 , 0 , 0 , 0 ,,
       3       3
  327.17 394.593
       3       3
  327.17 394.593
Pier Skew, UpSta & Num, DnSta & Num=  ,20473.4, 2 ,20500.1, 2 , 0 , 0 , 0 ,,
       3       3
  327.17 394.593
       3       3
  327.17 394.593
Pier Skew, UpSta & Num, DnSta & Num=  ,25836.71, 2 ,25881.38, 2 , 0 , 0 , 0 ,,
    2.33    2.33
     354 394.593
    2.33    2.33
     354 394.593
Pier Skew, UpSta & Num, DnSta & Num=  ,25878.37, 2 ,25923.15, 2 , 0 , 0 , 0 ,,
    2.33    2.33
     354 394.593
    2.33    2.33
     354 394.593
Pier Skew, UpSta & Num, DnSta & Num=  ,25919.97, 2 ,25964.91, 2 , 0 , 0 , 0 ,,
    2.33    2.33
     354 394.593
    2.33    2.33
     354 394.593
Pier Skew, UpSta & Num, DnSta & Num=  ,26940.36, 2 ,26942.19, 2 , 0 , 0 , 0 ,,
    1.17    1.17
     350 394.593
    1.17    1.17
     350 394.593
Pier Skew, UpSta & Num, DnSta & Num=  ,26970.18, 2 ,26971.93, 2 , 0 , 0 , 0 ,,
    1.17    1.17
     350 394.593
    1.17    1.17
     350 394.593
Pier Skew, UpSta & Num, DnSta & Num=  ,26999.92, 2 ,27001.86, 2 , 0 , 0 , 0 ,,
    1.17    1.17
     350 394.593
    1.17    1.17
     350 394.593
Pier Skew, UpSta & Num, DnSta & Num=  ,27030.08, 2 ,27031.42, 2 , 0 , 0 , 0 ,,
    1.17    1.17
     350 394.593
    1.17    1.17
     350 394.593
Abutment Skew #Up #Dn= , 2 , 2
18418.9418475.25
  381.89 363.316
18445.6518501.96
  381.89 363.316
Abutment Skew #Up #Dn= , 2 , 2
20548.2520587.55
 367.481  380.15
20574.9620614.26
 367.481  380.15
BR Coef=-1 , 1 , 0 ,0.95, 0 ,,,0.8,-1,1.2,0,
WSPro=,,,, 1 ,,,, 0 ,,,, 0 ,,,,-1 ,-1 ,-1 , 0 , 0 , 0 , 0 , 0
Culvert=2,7,7,58.5,0.12,0.5,1,58,1,355.8093,13117.29,355.84,13122.45,Culvert #1  , 0 ,119.44
13117.2913122.45
BC Culvert Barrel=1,Barrel #1,0
Culvert Bottom n=0.12
Culvert=2,7,7,58.5,0.12,0.5,1,58,1,355.8093,13125,355.84,13130.09,Culvert #2  , 0 ,119.44
   1312513130.09
BC Culvert Barrel=1,Barrel #1,0
Culvert Bottom n=0.12
Culvert=2,2.5,6,58.5,0.12,0.5,1,58,1,360.97,21362.43,360.19,21367.32,Culvert #3  , 0 ,128.53
21362.4321367.32
BC Culvert Barrel=1,Barrel #1,0
Culvert Bottom n=0.12
BC Mult= 1 ,0,1500,0,1300
BC Mult= 3 ,1500,12700,1300,12500
BC Mult= 2 ,8700,18000,8500,18000
BC Mult= 3 ,13800,21300,13500,21150
BC Mult= 2 ,20800,25500,20700,25600
BC Mult= 3 ,22100,27500,22280,27500
BC Mult= 1 ,27500,30964.49,27500,30964.4
BR U #Sta/Elev= 426
       0  418.17   44.94  413.47   68.16  411.92   147.9  403.71  211.42  395.93
  231.96   394.7   295.6   394.6  370.27  397.26  421.08  399.15  530.45  402.21
  591.15  404.52  640.38  405.44  686.79  405.17  720.46  404.15  792.86  400.75
  931.06  390.45   976.8  388.07 1140.08  381.29 1235.66  378.87 1284.49  377.89
 1365.54  376.69 1430.58   375.3 1453.59  372.54 1503.04  370.96 1597.03  368.77
 1659.68  366.92  1789.4  364.16 1946.67  361.23 2022.98  361.53 2093.01  360.92
 2138.27  360.75 2254.48  360.32 2541.58  359.53 2769.32  358.92 3018.01  358.99
 3209.79  358.86 3585.21  359.05 3780.38  359.41 3883.09   358.9 4098.46  359.48
  4466.5  359.45 4782.71  359.61 4832.33  359.71    4894  359.93 4961.85  359.81
 5079.99  360.07 5241.01   359.9 5371.39  359.97 5517.48  359.71 5835.54  359.81
    5965  359.63 6082.61  360.14 6328.14  360.04 6385.67   360.3 6489.73  360.07
 6912.71  360.24 7010.17   360.5 7250.89   360.4 7603.78  360.96 7749.02  361.69
 7825.68  361.58 8000.55   362.6 8036.69  362.12 8155.69 359.683 8216.88 347.664
 8237.14 346.604 8253.38 347.235 8304.44 356.379 8617.79  362.89 8720.48  363.42
 9069.11  362.72 9203.84  361.96 9341.34  361.94 9448.21  361.59 9551.59  361.57
 9633.79  361.25 9836.95  361.38 9903.87  361.1510078.95  361.1910217.57  361.21
10410.26  361.3810854.36  361.0111208.18   361.111365.96  360.8111422.04  360.81
11500.06  360.5311694.08  360.6611798.59  360.2411884.12  360.5411957.31  360.34
12434.32  360.4712507.57  360.7612599.51  360.5812743.95  360.7612916.25  360.49
13063.83 359.11413085.85 358.95713097.01 359.087 13113.7 355.80913120.88 355.809
13121.38 355.80913128.62 355.80913132.78 359.55513167.76 359.42713186.72   359.1
   13229 359.48213242.89 359.28113248.22 359.043 13258.6 358.95713260.82 358.957
13267.03 359.086 13288.3 358.17813290.88 357.90813291.05 357.90713296.24  357.81
 13302.7  357.8113312.38 358.89313312.78 358.89713317.29 358.19213326.38 358.506
13344.35 358.33813350.77 358.15713354.54 358.169 13361.6 357.97113368.06 357.969
13373.35 357.83113377.24 357.90213382.03 358.31913386.48 358.39313390.23 358.203
 13400.4 358.778 13411.6 359.06313441.62 359.94113470.44 360.19113509.08  360.42
13612.43  361.1813842.65  361.2713927.21  361.5814129.09  360.99 14457.5  360.89
14547.52  360.3814654.94   360.614729.18  360.1714974.88  360.3515164.12  360.09
15288.64  359.8215485.28  359.32 15523.1  359.4515558.56  360.6615611.24  361.02
15666.19   359.915733.99  361.2515834.59  360.3515890.62  360.6715913.24  361.21
16015.72  360.9916063.88  360.7216141.77  361.3316222.52  363.0616295.28  364.42
16423.47  366.0816472.44  366.6216518.83  366.4516694.56  368.5616797.51  368.53
16836.76   367.916990.65  365.9317040.83  366.6217092.81  368.04 17153.5  367.62
17189.78  368.0217206.36   367.217223.22  364.4217282.95  363.3517316.87  360.88
17388.81   360.7 17536.2  360.0417652.49   360.417713.52  363.14 18469.3  364.52
18517.26  362.8118550.98  362.8618577.92  361.6118598.75  362.2918621.68  361.33
18727.91  361.1718760.78  360.3218811.13  354.1218852.63  360.8318932.88  361.13
19033.74  361.0819121.18  360.9819276.15  362.1419359.73  362.8519526.18  363.66
19600.57  365.2219668.76  367.07 19679.1  364.8319700.53  363.6119701.56   360.9
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BR U #Mann= 10
       0      .1  370.27     .07 2541.58     .05 4832.33      .1 5517.48     .05
17713.52      .119701.56    .05520003.09      .120568.99      .127164.25     .06
BR D #Sta/Elev= 468
       0  413.48  115.93  403.29  196.46  394.62  221.23  386.66  241.62  391.67
  295.51  393.16  325.28  392.45   345.7  389.87  381.49  382.53  411.01  381.17
  417.35  386.41  461.86  386.02  496.43   388.6  525.35  389.14   573.9  388.77
  620.62   388.6  858.35  384.33  893.47  384.45  951.09   383.2 1000.53  383.25
 1064.63  384.92 1217.92  380.63 1255.95  377.23 1296.57  376.03 1320.87  373.74
  1358.4  370.79 1514.88  365.17 1708.05  362.13 1868.77  359.13 2002.43  359.12
 2070.87  358.46 2229.51  358.38 2396.18  358.46 2678.79   358.5 3139.32  358.91
 3327.24  358.73 3474.27  359.28 3517.43  358.92 3667.21  359.09  3910.4  359.05
 3962.56  359.32 4107.05  359.19  4268.8  359.45  4579.4  359.28 4655.35  359.55
 4706.25  358.97 4914.18   359.5 4977.65  359.25 5143.63  359.48 5402.14  359.42
 5450.81  359.61 5613.05  359.28 5669.84  359.75 5784.75  359.91 5917.85  359.69
 6422.38  360.12 6815.83  360.34 6887.97   360.2 7243.93  360.54 7498.78  361.38
 7569.44  361.78 7784.75  362.19  8131.8 360.884 8178.93 350.739 8211.95 346.536
 8228.96 347.814 8311.47  364.53 8409.11  361.49 8465.98  361.94 8641.11  361.65
 8710.63  361.32 8963.53  361.25 9269.25  360.68 9564.88  360.37   10032  360.37
10555.68  360.4310923.69  360.3711229.12  360.4311309.84  360.8311331.59  362.91
 11354.8  363.1311383.61  360.3311482.17  360.17 11540.6  360.4311719.49  360.14
11807.05  360.3711919.12  360.2712099.58  360.6112533.31  360.6512663.82  360.37
12848.83 359.11412876.81 358.957 12890.8 359.55212932.78 359.41912946.77 359.121
12960.76 359.10612988.75 359.45213016.73 359.04313030.72 358.95713044.71 359.083
 13058.7 358.17813100.68 357.58913118.84  355.8413126.05  355.8413126.43  355.84
13133.74  355.8413142.65 358.56313156.64 358.89313170.64 358.89713198.62 358.192
13212.61 358.621 13226.6 358.59213240.59 357.97113268.58 357.83113296.56 357.984
13324.54 358.39313338.53 358.29313366.52 358.91913380.51  358.93 13394.5 360.042
13408.49 360.19113428.69  362.8613461.17  363.3613561.86  363.3913900.07  362.88
13993.52  361.9814250.33   362.314340.21  362.7514434.25  362.2914477.72   361.6
14592.33  362.5314692.65   362.414728.62  361.7114839.82  362.0414982.76  361.04
15024.17  361.5115071.06  361.0215113.38  361.7615162.93  360.0115321.92  359.67
15450.81  358.7815521.27  360.5615583.45  361.0315659.61  360.7515759.56  360.86
15787.18  359.3515815.77  359.8415843.15  361.5715907.07  360.8615985.53  360.56
16018.12  361.7416084.89  361.59 16115.5  360.55 16179.3  363.5816222.72  364.51
16276.55  363.6816355.49  364.5916466.63  364.2416512.43  364.98 16633.3  366.14
   16699   366.116727.26  365.2916831.39  364.2516875.26  364.8216943.71  363.09
17001.22  360.2917099.64  360.5817178.43  359.9617316.86  359.9217343.64  360.96
 17422.7  360.1417486.56  360.65 17512.3  360.1217638.93  359.9817685.75  360.78
17713.71  359.8517769.95   360.217804.99   362.7 17820.4  365.0617860.27  364.51
17902.71  361.4217988.34  361.7418015.71  361.3518056.52  361.4918178.76  361.07
18248.21  364.8518284.04  368.0318335.34  370.6718416.56  373.3118433.66  377.48
18438.59  378.4818443.53  378.8618448.46  379.22 18453.4  379.5218458.33  379.76
18463.27  379.9518468.21  380.0618473.14  380.1618478.08  380.1118483.01  379.92
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BR D #Mann= 8
       0      .1 2396.18     .0518015.71      .119757.48    .05520031.36      .1
21417.91     .0623235.21      .127074.96     .06
BC Design=,, 0 ,, 0 ,,,,,,
BC Use User HTab Curves=0
BC User HTab FreeFlow(D)= 0

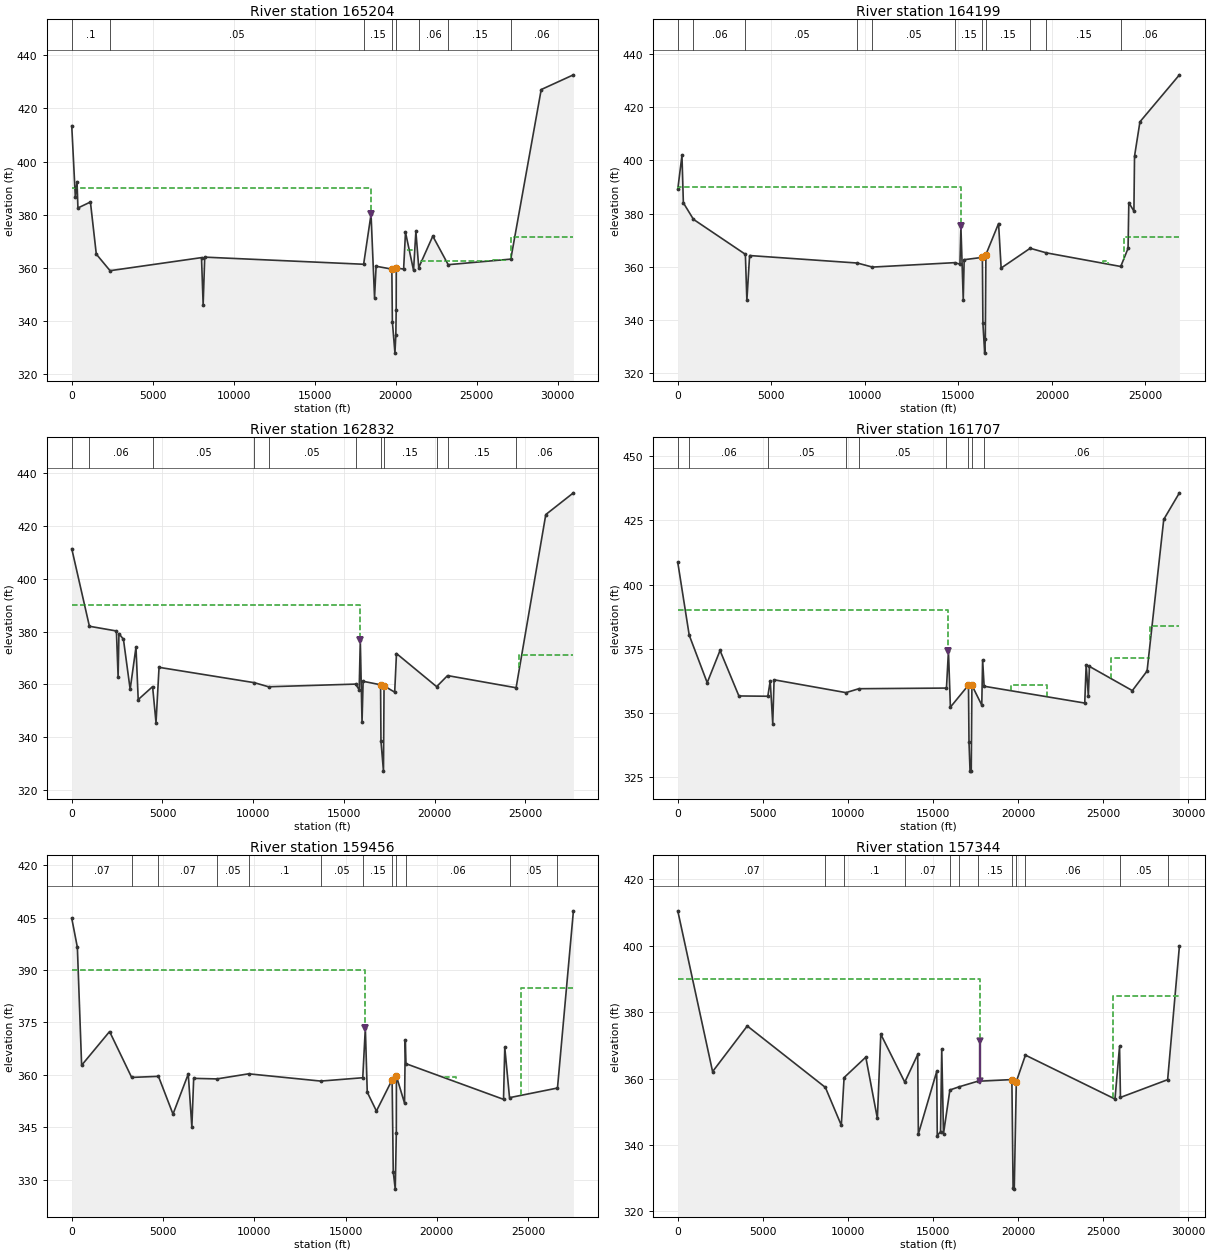
Type RM Length L Ch R = 1 ,165204  ,2833.82,1004.45,1013.94
BEGIN DESCRIPTION:
DS Bridge
LOB - Bois D'Arc
END DESCRIPTION:
XS GIS Cut Line= 6
2571148.471632786919340.467399712566087.707743886914099.32156637
2565193.957743886912277.099344142559059.235521646906042.55073301
2555996.041077196904886.995177452547776.423021616899942.02989966
#Sta/Elev= 30
       0  413.48  221.23  386.66  325.28  392.45  381.49  382.53 1152.41  384.78
 1514.88  365.17 2364.41  358.93 8009.12  363.85 8110.32  346.16 8208.18  364.03
18015.71  361.3518473.14  380.1618689.36  348.7918785.87   360.619757.48  359.53
19790.41   339.7 19948.8 327.90720003.44 334.86320025.39  344.1720031.36  359.91
20484.38  359.5520599.72  373.3721096.56  359.0721240.92  373.6921417.91   360.1
   22285  371.9423235.21  361.1927098.06  363.2828976.79   427.1 30964.4  432.64
#Mann= 8 ,-1 , 0
       0      .1       0 2364.41     .05       018015.71     .15       0
19757.48    .055       020031.36     .15       021417.91     .06       0
23235.21     .15       027098.06     .06       0
Levee=-1,18473.14,380.16,0,,,,
#XS Ineff= 5 ,-1
       018473.14     390   20664   21172   366.8   21562   25782   362.5
   26019 26861.1     363   27104 30964.4   371.6
Permanent Ineff=
       F       F       F       F       F
Bank Sta=19757.48,20031.36
XS Rating Curve= 0 ,0
Exp/Cntr=0.5,0.3

Type RM Length L Ch R = 1 ,164199  ,1428.2,1367.21,1058.58
BEGIN DESCRIPTION:
LOB - Bois D'Arc
END DESCRIPTION:
XS GIS Cut Line= 4
2572565.59443196 6911360.62073692559008.077070836904842.65198688
2557098.354848616904203.763097992548372.084459926899827.39656934
#Sta/Elev= 30
       0  389.12  224.44  401.91   299.2  384.07  838.45  377.86 3614.19   364.7
 3694.54   347.4 3840.79  364.24 9599.25  361.4210407.14   359.914797.07  361.56
15084.37     36115135.94  375.3115261.81  347.5815310.66  362.6816284.31  363.55
16312.96  338.6816407.93  327.5316441.75  332.9916473.03  364.6117150.04  376.29
17287.03  359.5318838.98  366.9719705.71  365.2523681.46  360.1224072.29  366.94
24113.22  384.1624385.24  380.9324418.55  401.6124708.18  414.55 26818.9  432.22
#Mann= 11 ,-1 , 0
       0     .07       0  838.45     .06       0 3614.19     .05       0
 9599.25      .1       010407.14     .05       014797.07     .15       0
16284.31    .055       016473.03     .15       018838.98     .06       0
19705.71     .15       023681.46     .06       0
Levee=-1,15135.94,375.31,0,,,,
#XS Ineff= 4 ,-1
       015135.94     390   18198   21933     362   22748   23000   362.2
   23830 26818.9   371.3
Permanent Ineff=
       F       F       F       F
Bank Sta=16284.31,16473.03
XS Rating Curve= 0 ,0
Exp/Cntr=0.3,0.1

Type RM Length L Ch R = 1 ,162832  ,930.2,1125.12,1407.97
BEGIN DESCRIPTION:
LOB - Bois D'Arc
END DESCRIPTION:
XS GIS Cut Line= 4
2573672.057226476910324.489491232559342.144032026903463.29157455
2557416.102365356902900.791574552548203.307226456899716.85060233
#Sta/Elev= 30
       0  411.45  972.85  382.03 2460.75  380.24 2553.94  362.85 2600.63  379.25
 2848.45  377.07 3218.18  358.12 3539.16   374.1 3661.86  354.22 4454.66  359.13
 4643.12  345.45 4809.96  366.4510064.97  360.6210841.67  359.0815640.54  360.09
 15836.7  357.9115899.03  376.7915994.62  345.6716055.16  361.1517016.16  359.83
17037.44  338.4917175.73  327.0817207.69  359.4217793.92  357.0317892.38  371.69
20104.77  359.1220707.46  363.3224483.67   358.726120.06   424.427641.74  432.64
#Mann= 11 ,-1 , 0
       0     .07       0  972.85     .06       0 4454.66     .05       0
10064.97      .1       010841.67     .05       015640.54     .15       0
17016.16    .055       017207.69     .15       020104.77     .06       0
20707.46     .15       024483.67     .06       0
Levee=-1,15899.03,376.79,0,,,,
#XS Ineff= 3 ,-1
       015899.03     390   19214   22320   361.3   2466627641.74   371.2
Permanent Ineff=
       F       F       F
Bank Sta=17016.16,17207.69
XS Rating Curve= 0 ,0
Exp/Cntr=0.3,0.1

Type RM Length L Ch R = 1 ,161707  ,1287.44,2251.17,2226.65
BEGIN DESCRIPTION:
LOB - Bois D'Arc
END DESCRIPTION:
XS GIS Cut Line= 4
 2573919.27944876909528.308935682559622.057226476902553.30893567
2557775.182226466901729.35060234 2547235.25167096896976.22560234
#Sta/Elev= 30
       0  408.66  673.33  380.22 1730.72  361.68 2484.87  374.25 3593.53   356.5
  5294.1  356.39 5435.28  362.36 5583.78  345.73 5662.01  362.81 9889.96   357.8
10646.13  359.3315796.61  359.5815913.21  374.1116027.77  352.1317091.24  360.75
17121.09  338.5217183.35  327.1617253.35  327.1617293.04  360.6817871.87  352.93
17921.79  370.6318010.71  360.2923925.79  353.7324009.32  368.6724137.73  356.47
24200.98  368.0426724.05  358.5927590.31  366.2428570.23  425.41 29492.4  435.79
#Mann= 9 ,-1 , 0
       0     .07       0  673.33     .06       0  5294.1     .05       0
 9889.96      .1       010646.13     .05       015796.61     .15       0
17091.24    .055       017293.04     .15       018010.71     .06       0
Levee=-1,15913.21,374.11,0,,,,
#XS Ineff= 4 ,-1
       015913.21     390   19577   21689   360.6   25475   27788   371.2
   27788 29492.4     384
Permanent Ineff=
       F       F       F       F
Bank Sta=17091.24,17293.04
XS Rating Curve= 0 ,0
Exp/Cntr=0.3,0.1

Type RM Length L Ch R = 1 ,159456  ,1796.97,2111.7,856.13
BEGIN DESCRIPTION:
LOB - Bois D'Arc
END DESCRIPTION:
XS GIS Cut Line= 4
2574022.578059816909063.899213462559391.791022766900614.24643568
2558348.966948696899676.746435672550237.855837576895365.98254678
#Sta/Elev= 30
       0  404.85   307.8  396.52  540.76  362.74 2072.69   372.4  3282.1  359.26
 4750.08  359.57  5546.9  348.75 6383.02  360.23 6580.04  345.05  6680.2  358.99
  7953.6  358.83 9688.69  360.2913642.18  358.2115942.82  359.1716083.73  373.43
16189.08  355.0216691.93  349.6317550.99  358.5817613.52  332.1917722.64  327.26
17780.74  343.2917786.32  359.6118232.31  351.8818272.77  369.9518310.25  363.19
23654.16  352.9823722.66  367.87 23983.2  353.4626610.13  356.2227483.23  406.98
#Mann= 12 ,-1 , 0
       0     .07       0  3282.1     .06       0 4750.08     .07       0
  7953.6     .05       0 9688.69      .1       013642.18     .05       0
15942.82     .15       017550.99    .055       017786.32     .15       0
18310.25     .06       0 23983.2     .05       026610.13     .06       0
Levee=-1,16083.73,373.43,0,,,,
#XS Ineff= 3 ,-1
       016083.73     390   20448   21044   359.3   2462127483.23     385
Permanent Ineff=
       F       F       F
Bank Sta=17550.99,17786.32
XS Rating Curve= 0 ,0
Exp/Cntr=0.3,0.1

Type RM Length L Ch R = 1 ,157344  ,948.05,3077.14,2486.59
BEGIN DESCRIPTION:
LOB - Bois D'Arc
END DESCRIPTION:
XS GIS Cut Line= 4
2576124.256300566909043.413102352560240.402133886898849.66310234
2558682.068800546898932.996435672550808.120060356894467.16161053
#Sta/Elev= 30
       0  410.53 2046.93  362.09 4085.18  375.84 8675.15  357.34 9612.65  345.92
 9776.27   360.311051.82  366.4511732.16  347.9811932.42  373.3613343.42  358.91
14104.43  367.2614140.35  343.2815220.16  362.1415252.47  342.7815444.82  344.04
   15515   368.915619.05  343.3915994.19  356.5616544.95  357.5317624.69  359.18
19638.15  359.6919708.99  327.0119777.38  326.6919898.87  359.0920434.58  367.06
 25698.6  353.8425966.05  369.68 26020.1  354.3228793.51  359.66 29486.2  399.98
#Mann= 12 ,-1 , 0
       0     .07       0 8675.15     .07       0 9776.27      .1       0
13343.42     .07       015994.19     .05       016544.95     .07       0
17624.69     .15       019638.15    .055       019898.87     .15       0
20434.58     .06       0 26020.1     .05       028793.51     .06       0
Levee=-1,17774.12,371.28,0,,,,
#XS Ineff= 2 ,-1
       017774.15     390   25586 29486.2     385
Permanent Ineff=
       F       F
Bank Sta=19638.15,19898.87
XS Rating Curve= 0 ,0
Exp/Cntr=0.3,0.1

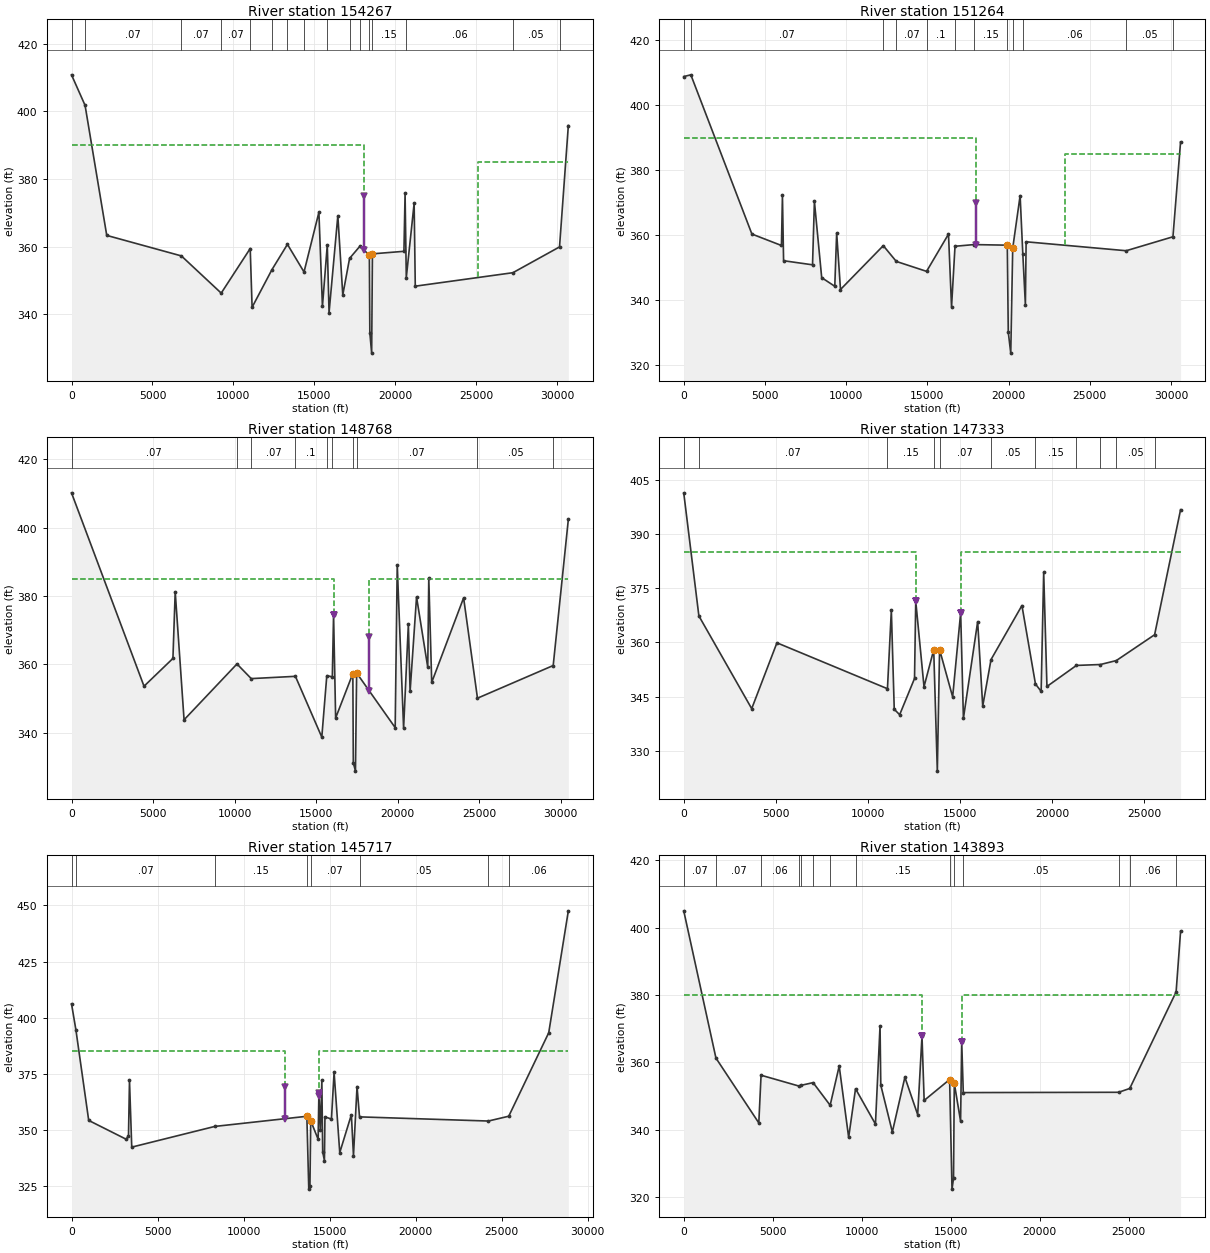
Type RM Length L Ch R = 1 ,154267  ,2928.63,3003.32,1020.6
BEGIN DESCRIPTION:
LOB - Bois D'Arc
END DESCRIPTION:
XS GIS Cut Line= 5
2577683.119930486908112.994882482562017.311695226899122.99645831
2561369.395340146897553.204650392560632.806918296897148.53059098
2550948.498531046894340.13036789
#Sta/Elev= 30
       0   410.8  837.14  401.79 2176.36  363.36 6785.31   357.3 9245.48  346.31
11036.79  359.4911152.87  342.1312375.82  353.2213335.26  360.7214359.38  352.55
15278.67  370.1915496.36  342.3815796.75  360.5815905.35  340.5616448.28  369.19
 16753.2  345.7617172.32  356.5717799.81   360.118394.04  357.59 18423.7  334.59
18536.48  328.5818584.13  357.9120530.15  358.6620600.43  375.7620675.41  350.89
21160.32  372.8521230.31  348.3627259.18  352.3430138.64  359.9630683.54  395.82
#Mann= 16 ,-1 , 0
       0     .07       0  837.14     .07       0 6785.31     .07       0
 9245.48     .07       011036.79      .1       012375.82     .07       0
13335.26      .1       014359.38     .07       015796.75      .1       0
17172.32     .07       017799.81     .15       018394.04    .055       0
18584.13     .15       020675.41     .06       027259.18     .05       0
30138.64     .06       0
Levee=-1,18057.04,375.03,0,,,,
#XS Ineff= 2 ,-1
       018057.04     390   2511730683.54     385
Permanent Ineff=
       F       F
Bank Sta=18394.04,18584.13
XS Rating Curve= 0 ,0
Exp/Cntr=0.3,0.1

Type RM Length L Ch R = 1 ,151264  ,621.55,2495.98,3306.68
BEGIN DESCRIPTION:
LOB - Bois D'Arc
END DESCRIPTION:
XS GIS Cut Line= 5
 2578634.50910386906008.828159062562540.853627156895992.51026523
2560824.186784896896009.176898552560782.641592386895987.49255873
2551073.515013316894178.02144015
#Sta/Elev= 30
       0  408.76  437.28  409.29 4197.57  360.34 6017.73  356.82 6077.77   372.2
 6148.51  352.14 7931.23  350.88 8046.75  370.36 8495.57  346.93  9301.6  344.28
 9417.25  360.68 9653.25  343.2912288.91  356.7713090.76  351.9214954.12  348.87
16304.17  360.3216491.45  337.9316705.35  356.5817869.34   357.119925.13  356.92
19985.24  330.1520138.63  323.7320258.42  355.9620714.75  372.1520879.38  354.32
21039.31  338.5921084.29  357.9627246.89  355.2130125.76   359.530595.58  388.68
#Mann= 12 ,-1 , 0
       0     .07       0  437.28     .07       012288.91      .1       0
13090.76     .07       014954.12      .1       016705.35     .07       0
17869.34     .15       019925.13    .055       020258.42     .15       0
20879.38     .06       027246.89     .05       030125.76     .06       0
Levee=-1,17986.26,369.76,0,,,,
#XS Ineff= 2 ,-1
       017986.26     390   2347630595.58     385
Permanent Ineff=
       F       F
Bank Sta=19925.13,20258.42
XS Rating Curve= 0 ,0
Exp/Cntr=0.3,0.1

Type RM Length L Ch R = 1 ,148768  ,2180.3,1434.55,1008.26
BEGIN DESCRIPTION:
LOB - Bois D'Arc, ROB - Dallas LID14/Ellis LID3
END DESCRIPTION:
XS GIS Cut Line= 4
2577606.524819086904625.264954192563948.885930186896182.44088012
 2562996.10815246894187.996435672552068.006300556888778.94550974
#Sta/Elev= 30
       0   410.2 4445.82  353.59 6217.95  361.73 6357.72  381.24 6900.93  343.76
10144.33  360.1111018.73  355.8213727.42  356.4915344.99  338.6915651.79  356.69
15990.23  356.33 16066.7  374.5416193.44   344.317248.37  357.3117277.84  331.16
17408.81  328.7417480.52  357.4719844.38  341.4719969.15     38920360.09  341.27
 20652.3  371.7820758.15  352.0521154.15  379.7221840.75  359.1421903.79  385.29
22083.69  354.7224039.39  379.4624889.55  350.0929531.82  359.6530460.41  402.43
#Mann= 10 ,-1 , 0
       0     .07       010144.33      .1       011018.73     .07       0
13727.42      .1       015651.79     .07       015990.23     .15       0
17248.37    .055       017480.52     .07       024889.55     .05       0
29531.82     .06       0
Levee=-1,16066.7,374.54,-1,18258.25,368.05,,
#XS Ineff= 2 ,-1
       0 16066.7     38518258.2530460.41     385
Permanent Ineff=
       F       F
Bank Sta=17248.37,17480.52
XS Rating Curve= 0 ,0
Exp/Cntr=0.3,0.1

Type RM Length L Ch R = 1 ,147333  ,1522.48,1615.72,1708.82
BEGIN DESCRIPTION:
LOB - Bois D'Arc, ROB - Dallas LID14/Ellis LID3
END DESCRIPTION:
XS GIS Cut Line= 2
2576276.933184796900889.164637482552908.284078336887410.88995419
#Sta/Elev= 30
       0  401.37  822.29  367.34 3690.28  341.71  5060.3  359.9111061.22  347.22
11272.42  368.9211430.28  341.5411723.82  340.0312531.27  350.0512596.91  371.45
13046.23  347.7713573.14  357.9713769.15  324.44 13891.7  358.0314601.28  344.96
15036.43  368.2115185.93  339.0415959.54  365.7716234.04   342.416684.98  355.28
18363.08  370.2119098.34  348.5219406.18  346.4919544.29  379.3819721.06  347.84
21322.53  353.6622624.37  353.9123487.85     35525566.94  362.1426977.04  396.71
#Mann= 11 ,-1 , 0
       0     .07       0  822.29     .07       011061.22     .15       0
13573.14    .055       0 13891.7     .07       016684.98     .05       0
19098.34     .15       021322.53     .05       022624.37     .08       0
23487.85     .05       025566.94     .06       0
Levee=-1,12596.91,371.45,-1,15036.43,368.21,,
#XS Ineff= 2 , 0
       012596.91     38515036.43       0     385
Permanent Ineff=
       F       F
Bank Sta=13573.14,13891.7
XS Rating Curve= 0 ,0
Exp/Cntr=0.3,0.1

Type RM Length L Ch R = 1 ,145717  ,2352.85,1824.58,1766.13
BEGIN DESCRIPTION:
LOB - Bois D'Arc, ROB - Dallas LID14/Ellis LID3
END DESCRIPTION:
XS GIS Cut Line= 3
2576750.617863126899723.127008332562501.812617966891032.92161155
2552179.679563736884538.09631899
#Sta/Elev= 30
       0   406.2  255.83  394.59  999.97  354.31 3176.04  345.95 3312.42  347.44
 3370.76  372.11 3501.63  342.43 8331.41  351.6413682.74  356.1513794.34  323.75
13862.02  325.09 13907.7  354.1414338.01  345.9414382.71   366.314470.26  349.86
14554.33  372.1914603.38  340.3214704.13  336.4414734.37   355.9 15112.4  354.91
15266.05  375.7215595.33  339.9916270.53  356.8516393.24  338.6316600.02  369.38
16744.27  355.8924236.03  354.0425420.18  356.1827744.78  393.3128885.25  447.54
#Mann= 8 ,-1 , 0
       0     .07       0  255.83     .07       0 8331.41     .15       0
13682.74    .055       0 13907.7     .07       016744.27     .05       0
24236.03     .15       025420.18     .06       0
Levee=-1,12408.07,369.23,-1,14387.71,366.38,,
#XS Ineff= 2 , 0
       012408.07     38514387.71       0     385
Permanent Ineff=
       F       F
Bank Sta=13682.74,13907.7
XS Rating Curve= 0 ,0
Exp/Cntr=0.3,0.1

Type RM Length L Ch R = 1 ,143893  ,1386.21,2002.89,2192.25
BEGIN DESCRIPTION:
LOB - Bois D'Arc, ROB - Dallas LID14/Ellis LID3
END DESCRIPTION:
XS GIS Cut Line= 4
2578362.103522786898989.489491232566872.207689446891416.57282456
2565204.464633896890648.517269012554808.631300566884061.71171345
#Sta/Elev= 30
       0  405.02  1809.1  361.27 4215.91  342.01 4343.07  356.18 6490.13  352.93
 6578.34  353.16 7266.71  353.98 8222.76  347.25 8731.12   358.9 9262.43  337.71
 9648.58  352.1610767.26  341.6611025.21  370.8311066.73  353.24 11716.3  339.32
12420.42  355.5813139.14  344.4713381.12  367.8213503.12  348.69   14933   354.9
15066.51  322.34 15152.1  325.5115195.09  353.8415548.36  342.5115611.78  366.16
15700.22  351.0224423.11  351.1125048.71  352.2427653.42  380.9327904.03  398.92
#Mann= 14 ,-1 , 0
       0     .07       0  1809.1     .07       0 4343.07     .06       0
 6490.13     .07       0 6578.34     .06       0 7266.71     .07       0
 8222.76     .06       0 9648.58     .15       0   14933    .055       0
15195.09     .15       015700.22     .05       024423.11      .1       0
25048.71     .06       027653.42     .06       0
Levee=-1,13381.12,367.82,-1,15611.78,366.16,,
#XS Ineff= 2 , 0
       013381.12     38015611.78       0     380
Permanent Ineff=
       F       F
Bank Sta=14933,15195.09
XS Rating Curve= 0 ,0
Exp/Cntr=0.3,0.1

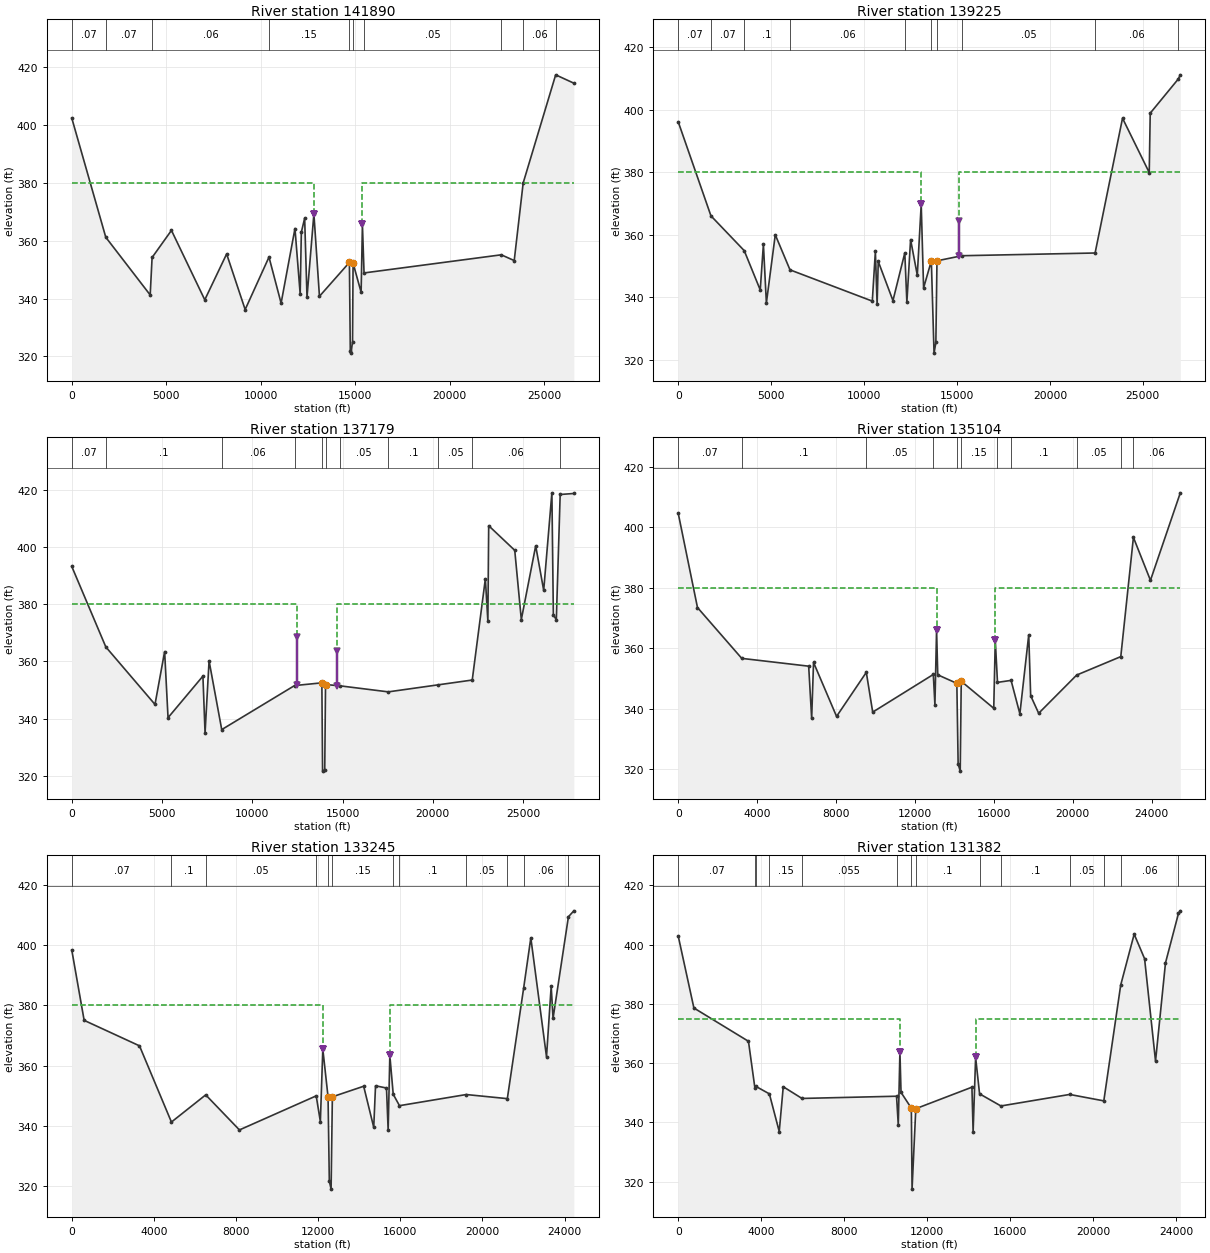
Type RM Length L Ch R = 1 ,141890  ,652.55,2664.82,1441.16
BEGIN DESCRIPTION:
LOB - Bois D'Arc, ROB - Dallas LID14/Ellis LID3
END DESCRIPTION:
XS GIS Cut Line= 4
2578488.353522786898883.58671344 2568553.35641636890829.58063706
2566718.041022786889165.878380122557641.131300556882425.25338011
#Sta/Elev= 30
       0  402.43 1800.06   361.2 4150.41  341.24 4251.12   354.2  5275.6  363.58
 7039.13  339.56 8196.75  355.43 9176.52  336.19 10438.1  354.3411079.09   338.4
11813.32  364.2312088.64  341.5712149.99  362.9412325.52  367.7812449.91  340.47
12814.72  369.3113108.45  340.7814693.74  352.4914741.93  321.7114782.41  321.12
14860.21  325.1114888.41  352.25   15314  342.1715382.57  365.6215468.64  348.86
22731.81  355.1323416.95  353.1423891.33  379.9925611.27  417.39 26572.7   414.5
#Mann= 10 ,-1 , 0
       0     .07       0 1800.06     .07       0 4251.12     .06       0
 10438.1     .15       014693.74    .055       014888.41     .15       0
15468.64     .05       022731.81     .06       023891.33     .06       0
25611.27     .06       0
Levee=-1,12814.72,369.31,-1,15382.57,365.62,,
#XS Ineff= 2 , 0
       012814.72     38015382.57       0     380
Permanent Ineff=
       F       F
Bank Sta=14693.74,14888.41
XS Rating Curve= 0 ,0
Exp/Cntr=0.3,0.1

Type RM Length L Ch R = 1 ,139225  ,2176.74,2045.8,1473.69
BEGIN DESCRIPTION:
LOB - Bois D'Arc, ROB - Dallas LID14/Ellis LID3
END DESCRIPTION:
XS GIS Cut Line= 5
2580054.216385846898561.619567212569420.297967226890896.57282456
2569022.728522786889783.725602332568733.911971856889067.08063706
2559482.337673346881500.95068294
#Sta/Elev= 30
       0  396.08 1759.93  366.06 3551.36  354.94 4412.54  342.38  4582.4  356.97
 4742.74  338.24 5221.17  360.01 6013.33  348.8110441.95  338.8210607.14   354.7
10700.41  337.8110761.86  351.4911552.72  338.9912190.13  354.2212301.86  338.47
 12501.8  358.4812862.34   347.113073.38  369.7213201.59  343.0413618.32  351.66
13764.12  322.2113861.47  325.6113921.57  351.6915260.04  353.3222429.54  354.19
23905.14  397.2425342.24  379.8825395.36  398.8526903.19  409.7527014.43   411.1
#Mann= 10 ,-1 , 0
       0     .07       0 1759.93     .07       0 3551.36      .1       0
 6013.33     .06       012190.13     .15       013618.32    .055       0
13921.57     .15       015260.04     .05       022429.54     .06       0
26903.19     .05       0
Levee=-1,13073.38,369.72,-1,15128.06,364.44,,
#XS Ineff= 2 , 0
       013073.38     38015128.06       0     380
Permanent Ineff=
       F       F
Bank Sta=13618.32,13921.57
XS Rating Curve= 0 ,0
Exp/Cntr=0.3,0.1

Type RM Length L Ch R = 1 ,137179  ,1988.3,2074.85,2404.85
BEGIN DESCRIPTION:
LOB - Bois D'Arc, ROB - Dallas LID14/Ellis LID3
END DESCRIPTION:
XS GIS Cut Line= 2
2581101.955804856897688.613708642559828.689956316879779.65028662
#Sta/Elev= 30
       0  393.14 1885.94  365.03  4609.3  344.95 5143.27   363.4 5331.64  340.32
  7263.9  354.84 7382.41  334.95 7604.47  360.17 8305.71  336.1612339.54  351.54
13851.67  352.4913891.11  321.66 14010.4  322.04 14055.2   351.914829.02  351.47
17529.78  349.3420308.99  351.8122180.46  353.4722907.18  388.8323046.43  374.04
23091.54  407.3724534.58  398.7724898.53  374.5825694.94  400.35 26138.2   384.8
26591.84  418.8526673.43  376.2526837.38  374.5127051.21  418.2727807.95  418.62
#Mann= 11 ,-1 , 0
       0     .07       0 1885.94      .1       0 8305.71     .06       0
12339.54     .15       013851.67    .055       0 14055.2     .15       0
14829.02     .05       017529.78      .1       020308.99     .05       0
22180.46     .06       027051.21     .05       0
Levee=-1,12479.5,368.33,-1,14714.5,363.6,,
#XS Ineff= 2 , 0
       0 12479.5     380 14714.5       0     380
Permanent Ineff=
       F       F
Bank Sta=13851.67,14055.2
XS Rating Curve= 0 ,0
Exp/Cntr=0.3,0.1

Type RM Length L Ch R = 1 ,135104  ,1573.64,1859.49,1698.1
BEGIN DESCRIPTION:
LOB - Bois D'Arc, ROB - Dallas LID14/Ellis LID3
END DESCRIPTION:
XS GIS Cut Line= 4
 2582536.83044336896710.411491352572529.409657046888196.18943335
2571674.374934826886894.974155572563718.53002741 6879660.5412852
#Sta/Elev= 30
       0  404.66  975.72  373.49 3219.69  356.68 6611.98   354.1 6763.34  336.82
 6858.08  355.34 8025.49  337.48 9533.62  352.06 9856.99   338.912929.63  351.36
13010.82  341.3113094.66  366.0913154.63  351.2414122.17  348.4214187.93  321.73
14293.16  319.3814345.25  349.1115992.55  340.1716070.54   362.716182.41  348.74
16871.52   349.417316.75  338.3417766.38  364.4717864.29  344.3418269.85  338.52
20196.52  351.1622432.12  357.2623072.47   396.723936.33   382.525449.53  411.45
#Mann= 11 ,-1 , 0
       0     .07       0 3219.69      .1       0 9533.62     .05       0
12929.63     .15       014122.17    .055       014345.25     .15       0
16182.41     .05       016871.52      .1       020196.52     .05       0
22432.12     .06       023072.47     .06       0
Levee=-1,13094.66,366.09,-1,16070.54,362.7,,
#XS Ineff= 2 , 0
       013094.66     38016060.55       0     380
Permanent Ineff=
       F       F
Bank Sta=14122.17,14345.25
XS Rating Curve= 0 ,0
Exp/Cntr=0.3,0.1

Type RM Length L Ch R = 1 ,133245  ,1421.06,1862.89,859.67
BEGIN DESCRIPTION:
LOB - Bois D'Arc, ROB - Dallas LID14/Ellis LID3
END DESCRIPTION:
XS GIS Cut Line= 4
2583349.971217766895215.749990182573768.877249636887647.78086853
2573663.182805196886553.753090752565391.637884436879090.74999018
#Sta/Elev= 30
       0  398.35   602.8  375.05  3297.8   366.6 4852.94  341.34 6522.78  350.35
  8164.1  338.7311903.46  350.0212105.59  341.4712224.68  365.5512480.25  349.65
12541.74  321.7812628.18  319.1112690.26  349.7114214.83  353.2114704.48  339.59
14791.81  353.3615326.07  352.62 15406.5  338.6415488.41  363.4615653.89  350.54
15958.05  346.7719208.68  350.4621210.16   349.122006.64  385.8322354.15  402.38
 23118.1  362.9723345.48   386.323437.44  375.7524184.88  409.3824449.29  411.35
#Mann= 12 ,-1 , 0
       0     .07       0 4852.94      .1       0 6522.78     .05       0
11903.46     .15       012480.25    .055       012690.26     .15       0
15653.89     .05       015958.05      .1       019208.68     .05       0
21210.16      .1       022006.64     .06       024184.88     .05       0
Levee=-1,12224.68,365.55,-1,15488.41,363.46,,
#XS Ineff= 2 , 0
       012224.68     38015488.41       0     380
Permanent Ineff=
       F       F
Bank Sta=12480.25,12690.26
XS Rating Curve= 0 ,0
Exp/Cntr=0.3,0.1

Type RM Length L Ch R = 1 ,131382  ,1497.01,1820.98,1004.37
BEGIN DESCRIPTION:
LOB - Bois D'Arc, ROB - Dallas LID14/Ellis LID3
END DESCRIPTION:
XS GIS Cut Line= 4
2584317.349471856894327.364201862575937.488360746887689.86420186
2575304.155027416886867.64197964 2565867.59982616878713.40774316
#Sta/Elev= 30
       0  402.91  754.96  378.64 3384.72   367.4 3691.95   351.8 3726.55  352.24
 4392.35  349.66 4867.98  336.94  5061.3  352.06 5964.83  348.11 10522.3  348.86
 10605.5  339.1910685.22  363.9510738.01  350.1611235.91  344.8311269.98   317.5
11450.27  344.6514155.48  351.91 14213.2  336.8814333.52  361.9514524.14  349.67
15552.36  345.57 18867.2  349.4620512.32  347.2921326.36  386.3821975.55  403.56
22477.45  395.2823005.03  360.7223485.15  393.8724110.71  410.5624199.55  411.44
#Mann= 14 ,-1 , 0
       0     .07       0 3691.95      .1       0 3726.55     .07       0
 4392.35     .15       0 5964.83    .055       0 10522.3     .15       0
11235.91    .055       011450.27      .1       014524.14     .05       0
15552.36      .1       0 18867.2     .05       020512.32      .1       0
21326.36     .06       024110.71     .05       0
Levee=-1,10685.22,363.95,-1,14333.52,361.95,,
#XS Ineff= 2 , 0
       010685.22     37514333.52       0     375
Permanent Ineff=
       F       F
Bank Sta=11235.91,11450.27
XS Rating Curve= 0 ,0
Exp/Cntr=0.3,0.1