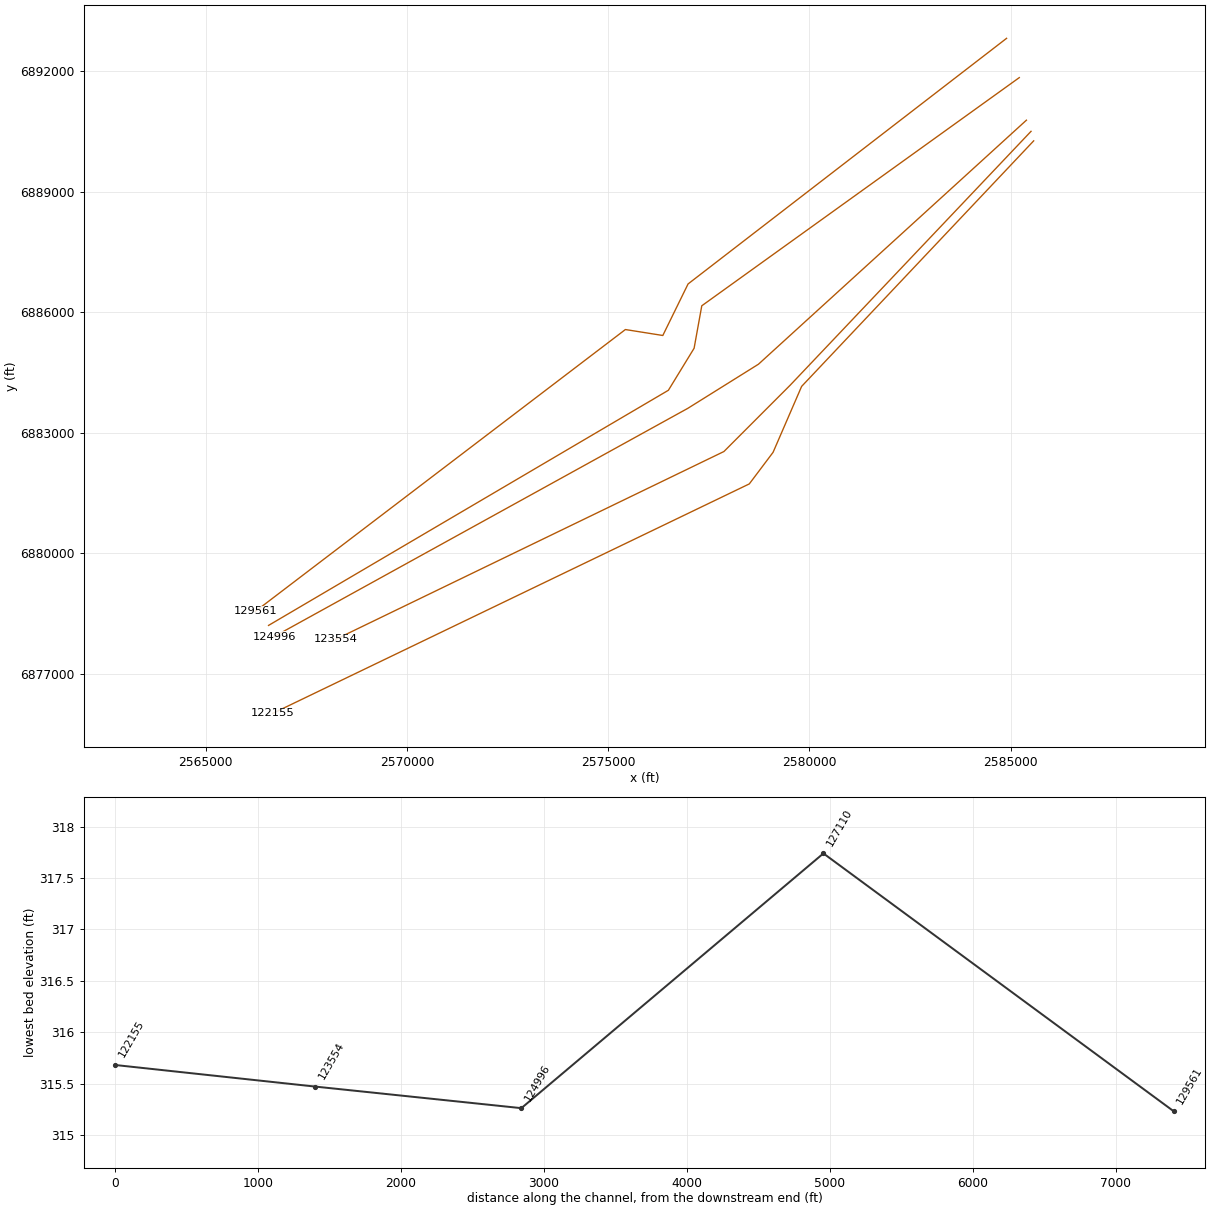
HEC-RAS study TR_FEMA.prj: Trinity_River_FEMA

--- TR_FEMA.g08 (geometry) --- (continued)

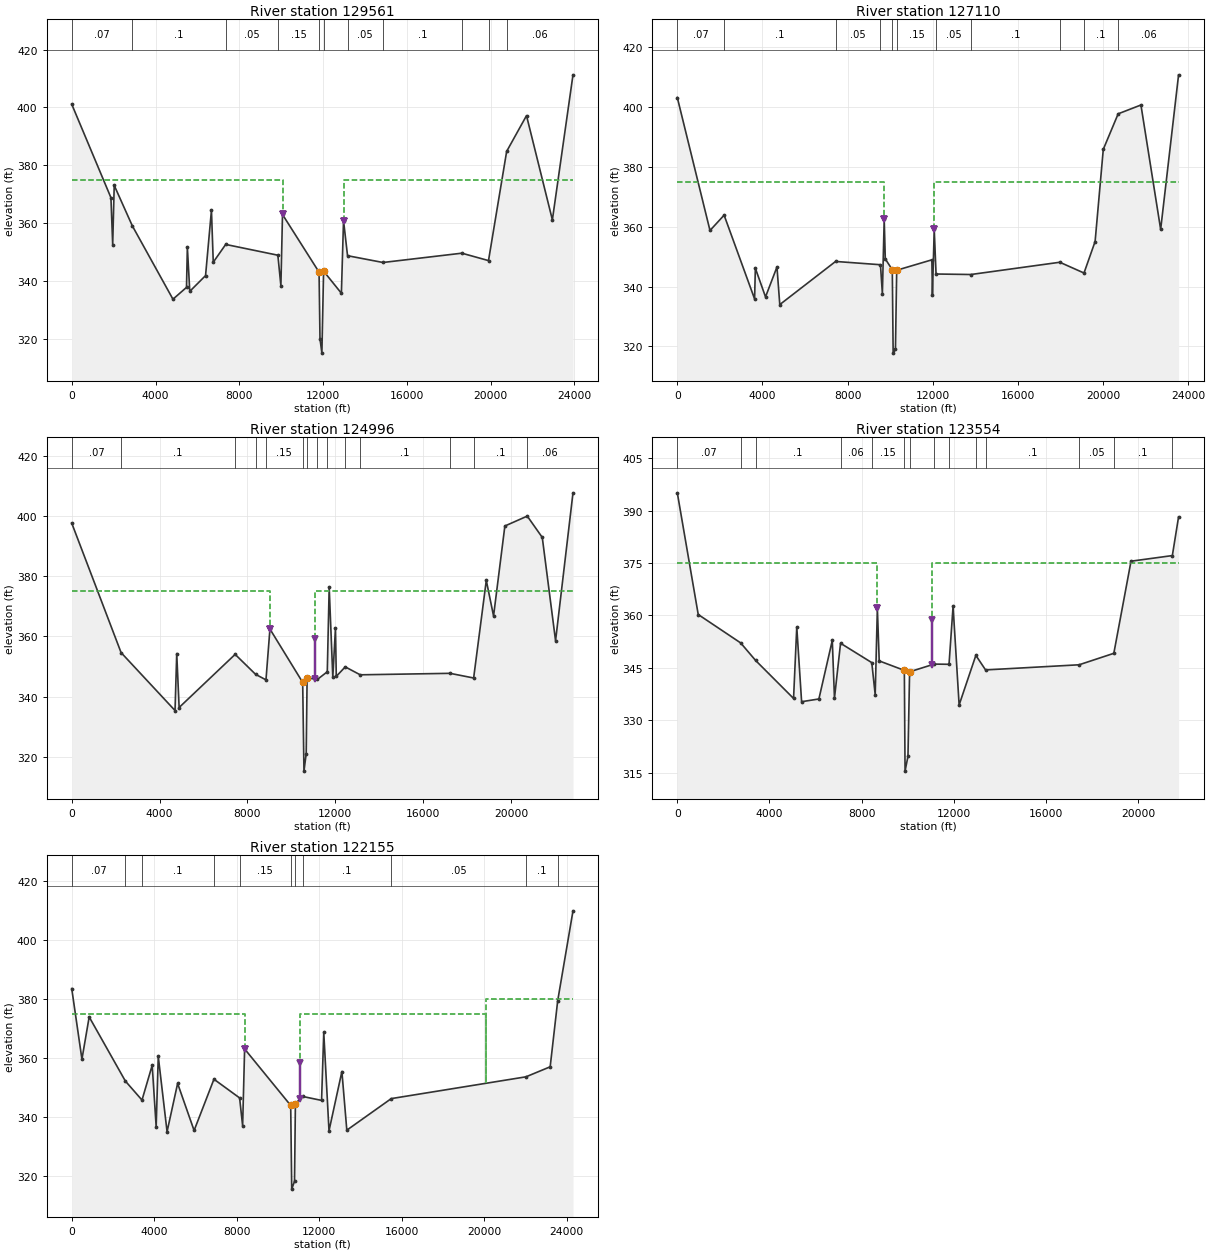
Type RM Length L Ch R = 1 ,129561  ,712.19,2450.97,1729.68
BEGIN DESCRIPTION:
LOB - Bois D'Arc, ROB - Dallas LID14/Ellis LID3
END DESCRIPTION:
XS GIS Cut Line= 5
2584901.377249636892811.391979632576986.909657046886702.86188705
2576359.13187926 6885420.91744262575429.270768156885568.83410927
2566232.183159436878557.15774316
#Sta/Elev= 30
       0  401.13 1872.04  368.87 1955.56  352.69 2028.68  373.11 2893.87  359.14
 4832.74  333.84 5479.59  337.92 5519.86  351.82 5635.94  336.55  6389.1  341.98
 6670.49  364.54 6757.04   346.6  7350.2  352.74 9841.16  349.02 9985.82  338.51
10062.62  363.0711808.27  343.1711852.09  320.22 11943.3  315.23 12024.1  343.53
12874.15  335.8912976.12  360.9713167.68  348.8514860.51  346.5118624.95  349.72
19897.79  347.1620764.35  384.8521712.11  397.1922946.95  361.2223931.62  411.27
#Mann= 11 ,-1 , 0
       0     .07       0 2893.87      .1       0  7350.2     .05       0
 9841.16     .15       011808.27    .055       0 12024.1     .15       0
13167.68     .05       014860.51      .1       018624.95     .05       0
19897.79      .1       020764.35     .06       0
Levee=-1,10062.62,363.07,-1,12976.12,360.97,,
#XS Ineff= 2 , 0
       010062.62     37512976.12       0     375
Permanent Ineff=
       F       F
Bank Sta=11808.27,12024.1
XS Rating Curve= 0 ,0
Exp/Cntr=0.3,0.1

Type RM Length L Ch R = 1 ,127110  ,1790.05,2113.72,648.82
BEGIN DESCRIPTION:
LOB - Bois D'Arc, ROB - Dallas LID14/Ellis LID3
END DESCRIPTION:
XS GIS Cut Line= 5
2585217.20479592 6891834.55748892577327.50572185 6886159.7600352
2577136.649240376885103.446377792576497.76035148 6884058.3074889
2566562.044270546878209.93552094
#Sta/Elev= 30
       0  403.21 1534.94  358.75 2198.55  363.88 3630.38  335.86 3665.79  346.14
 4143.58  336.54 4681.18  346.55 4813.25  333.97 7434.72   348.4 9542.72   347.3
  9632.6  337.64 9718.61  362.54 9769.52  349.2510098.13  345.6210139.04  317.74
10246.55  318.9810305.39  345.4611956.64  348.9411983.88   337.112068.25  359.18
12153.81   344.213789.35  344.0317966.64  348.1319103.62  344.5319625.18  355.07
20009.36  385.8920708.11  397.7721777.79  400.7222704.35  359.1223546.05  410.81
#Mann= 11 ,-1 , 0
       0     .07       0 2198.55      .1       0 7434.72     .05       0
 9542.72     .15       010098.13    .055       010305.39     .15       0
12153.81     .05       013789.35      .1       017966.64     .05       0
19103.62      .1       020708.11     .06       0
Levee=-1,9718.61,362.54,-1,12068.25,359.18,,
#XS Ineff= 2 , 0
       0 9718.61     37512068.25       0     375
Permanent Ineff=
       F       F
Bank Sta=10098.13,10305.39
XS Rating Curve= 0 ,0
Exp/Cntr=0.3,0.1

Type RM Length L Ch R = 1 ,124996  ,778.22,1442.73,1331.79
BEGIN DESCRIPTION:
LOB - Bois D'Arc, ROB - Dallas LID14/Ellis LID3
END DESCRIPTION:
XS GIS Cut Line= 4
2585394.264981116890775.946377792578735.931647786884706.50193334
2576979.681647776883608.585266682566700.933159436877932.15774316
#Sta/Elev= 30
       0  397.63 2246.66  354.63 4703.32  335.38 4780.89  354.32 4889.73  336.39
 7439.97  354.04 8370.86  347.41 8843.92  345.57 9024.18  362.4510515.38  344.73
10573.38  315.2610675.89  321.0910716.75  346.2511183.85  345.72 11635.3  348.25
11722.04  376.3411886.44  346.5212008.34  362.7912045.16  346.7412453.64  349.88
13134.25  347.2517225.42  347.7418299.05  346.1918875.03  378.5919205.62   366.8
19720.69  396.6720740.13  399.9621423.72  392.8822028.93  358.5722822.69  407.69
#Mann= 14 ,-1 , 0
       0     .07       0 2246.66      .1       0 7439.97     .06       0
 8370.86     .05       0 8843.92     .15       010515.38    .055       0
10716.75     .15       011183.85     .05       0 11635.3      .1       0
12453.64     .05       013134.25      .1       017225.42     .05       0
18299.05      .1       020740.13     .06       0
Levee=-1,9024.18,362.44,-1,11083.76,359.07,,
#XS Ineff= 2 , 0
       0 9024.18     37511083.76       0     375
Permanent Ineff=
       F       F
Bank Sta=10515.38,10716.75
XS Rating Curve= 0 ,0
Exp/Cntr=0.3,0.1

Type RM Length L Ch R = 1 ,123554  ,223.62,1398.9,1040.15
BEGIN DESCRIPTION:
LOB - Bois D'Arc, ROB - Dallas LID14/Ellis LID3
END DESCRIPTION:
XS GIS Cut Line= 4
2585509.000037216890498.497733262579526.932805186884187.75193334
2577877.627249636882534.974155562568228.710937216877862.71329872
#Sta/Elev= 30
       0  395.08  907.75  360.27 2748.21  352.15 3397.43  347.13 5044.32  336.26
 5183.41   356.7 5393.26  335.33  6143.7  336.11 6724.73  352.85 6819.31  336.34
 7083.41  352.05 8438.49  346.51 8586.94   337.3 8680.47  362.07 8760.93     347
 9851.44  344.29  9882.4  315.4710008.54   319.710079.93  343.8811146.16  346.09
11790.33  346.0311965.99  362.6212228.57   334.412954.43  348.5813375.61  344.42
17435.15  345.8918941.52  349.1719687.33  375.5221480.53  377.1321750.92  388.22
#Mann= 14 ,-1 , 0
       0     .07       0 2748.21     .06       0 3397.43      .1       0
 7083.41     .06       0 8438.49     .15       0 9851.44    .055       0
10079.93     .15       011146.16     .05       011790.33      .1       0
12954.43     .05       013375.61      .1       017435.15     .05       0
18941.52      .1       021480.53     .06       0
Levee=-1,8680.47,362.07,-1,11041.08,358.82,,
#XS Ineff= 2 , 0
       0 8680.47     37511041.08       0     375
Permanent Ineff=
       F       F
Bank Sta=9851.44,10079.93
XS Rating Curve= 0 ,0
Exp/Cntr=0.3,0.1

Type RM Length L Ch R = 1 ,122155  ,264.7,1249.35,675.81
BEGIN DESCRIPTION:
LOB - Bois D'Arc, ROB - Dallas LID14/Ellis LID3
ROB IFA station 20096: flow expansion due to natural high ground upstream
END DESCRIPTION:
XS GIS Cut Line= 5
2585574.994147786890261.849155572579808.489518156884154.81211854
2579098.767295936882514.534340762578508.489518156881729.81211854
2566666.210937216876022.43552094
#Sta/Elev= 30
       0  383.65  494.88  359.71  846.43  374.04 2600.82  352.31 3408.26  345.86
 3903.21  357.65 4095.35  336.83 4197.44  360.67  4624.4  335.14  5136.3   351.5
 5935.95  335.55 6898.27  352.93 8142.87  346.59 8289.74  337.15 8385.98  363.19
10621.02  344.0510670.96  315.6810806.46  318.3410849.79   344.711204.51  347.08
12118.58  345.7512224.99  368.7712479.21  335.4413104.59  355.5413343.22  335.66
15499.24  346.3622031.38  353.7423207.33  357.14 23572.3  379.5424314.35     410
#Mann= 11 ,-1 , 0
       0     .07       0 2600.82     .06       0 3408.26      .1       0
 6898.27     .06       0 8142.87     .15       010621.02    .055       0
10849.79     .15       011204.51      .1       015499.24     .05       0
22031.38      .1       0 23572.3     .06       0
Levee=-1,8385.98,363.19,-1,11095.25,358.45,,
#XS Ineff= 3 ,-1
       0 8385.98     37511095.25   20096     375   2009624314.35     380
Permanent Ineff=
       F       F       F
Bank Sta=10621.02,10849.79
XS Rating Curve= 0 ,0
Exp/Cntr=0.3,0.1