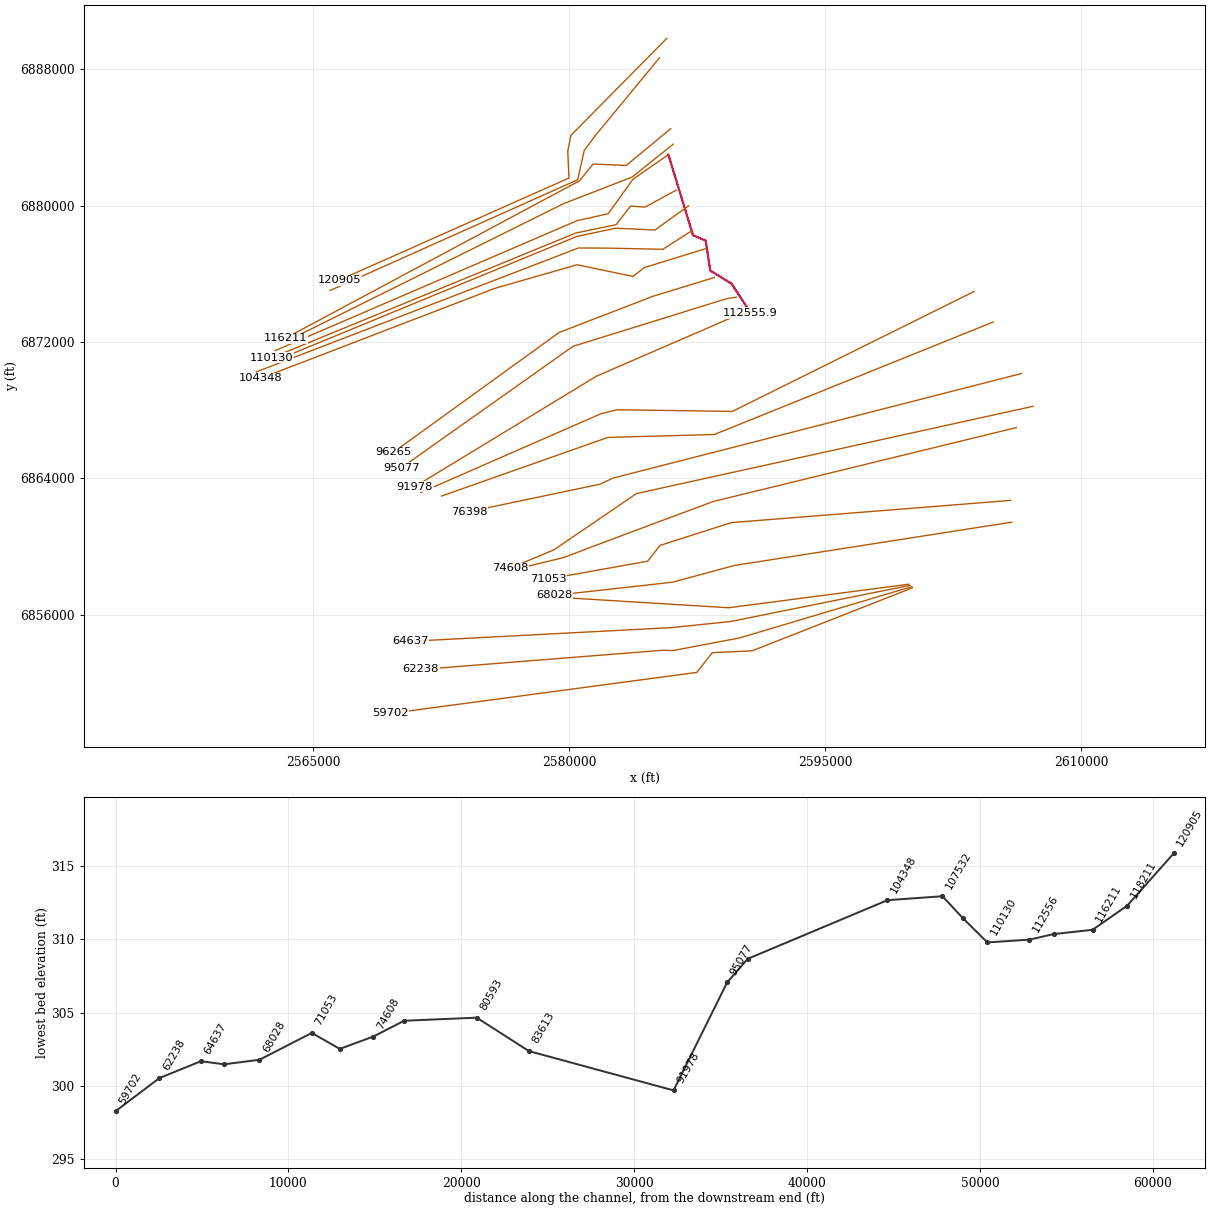
HEC-RAS study TR_FEMA.prj: Trinity_River_FEMA

--- TR_FEMA.g08 (geometry) --- (continued)

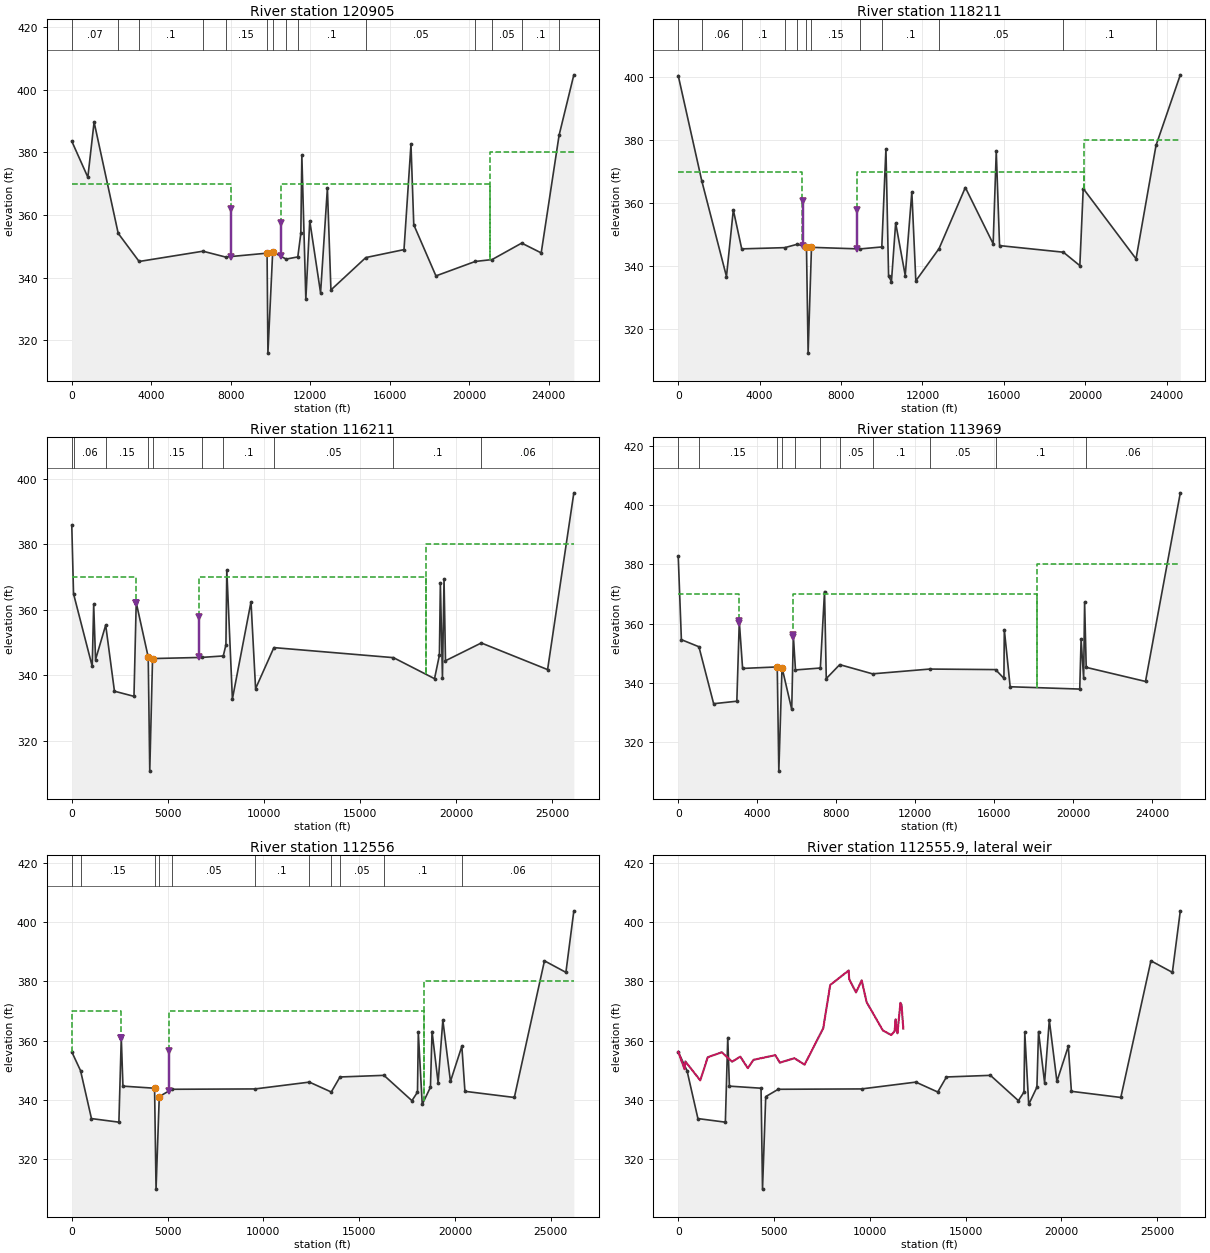
Type RM Length L Ch R = 1 ,120905  ,976.82,2694.7,313.19
BEGIN DESCRIPTION:
LOB - Bois D'Arc, ROB - Dallas LID14/Ellis LID3
ROB IFA station 21033: flow expansion due to natural high ground upstream
END DESCRIPTION:
XS GIS Cut Line= 5
2585714.392295936889812.555174092580091.614518156884120.88850743
2579906.058962596883189.013507422579976.886508896881615.51235001
2566509.960937216875623.12996538
#Sta/Elev= 30
       0  383.56  808.93  372.05 1123.59  389.67 2336.29  354.12 3389.41  345.13
 6601.08  348.41 7738.89  346.55 9828.58  347.79 9870.55  315.8510110.79   348.2
10786.36  345.8911374.55  346.5911527.09   354.111578.13  379.0811778.86  333.04
11975.94  358.1412520.65  335.1112863.31  368.5313041.78  336.0314797.73  346.38
16718.92  348.9217069.88  382.5617210.52  356.8618325.61  340.5220301.79  345.13
 21151.2  345.7422641.51     35123623.41  347.87 24524.3  385.4925265.88  404.76
#Mann= 14 ,-1 , 0
       0     .07       0 2336.29     .06       0 3389.41      .1       0
 6601.08     .06       0 7738.89     .15       0 9828.58    .055       0
10110.79     .15       010786.36     .05       011374.55      .1       0
14797.73     .05       020301.79      .1       0 21151.2     .05       0
22641.51      .1       0 24524.3     .06       0
Levee=-1,8005.69,361.93,-1,10526.72,357.49,,
#XS Ineff= 3 ,-1
       0 8005.69     37010526.72   21033     370   2103325265.88     380
Permanent Ineff=
       F       F       F
Bank Sta=9828.58,10110.79
XS Rating Curve= 0 ,0
Exp/Cntr=0.3,0.1

Type RM Length L Ch R = 1 ,118211  ,2761.13,1999.76,334.75
BEGIN DESCRIPTION:
LOB - Bois D'Arc, ROB - Dallas LID14/Ellis LID3
ROB IFA station 19915: flow expansion due to natural high ground upstream
END DESCRIPTION:
XS GIS Cut Line= 5
2585283.489518156888671.588738912581496.568221856884073.32485001
2580869.947851486883221.472998162580486.151555196881514.99151668
2565971.766492776875015.49107649
#Sta/Elev= 30
       0  400.54 1155.44   367.1 2369.85  336.65 2705.98  357.83 3119.07  345.44
  5232.5  345.83    5850  346.91 6300.75  345.99 6380.81  312.28 6546.02  345.93
 8921.03  345.42 10001.1  346.0510203.83  377.2710334.41  336.7610474.72  335.05
10681.82   353.711152.35  336.9611476.65  363.5511672.77  335.2712815.94  345.55
14105.39  364.9615471.42  347.0615624.14  376.4715786.65  346.4818921.67  344.38
19730.73  340.11 19897.3  364.6322492.53  342.2723472.56  378.3424666.69   400.8
#Mann= 12 ,-1 , 0
       0     .07       0 1155.44     .06       0 3119.07      .1       0
  5232.5     .06       0    5850     .15       0 6300.75    .055       0
 6546.02     .15       0 8921.03     .05       0 10001.1      .1       0
12815.94     .05       018921.67      .1       023472.56     .06       0
Levee=-1,6113.49,360.77,-1,8803.29,357.77,,
#XS Ineff= 3 ,-1
       0 6090.96     370 8803.29   19915     370   1991524666.69     380
Permanent Ineff=
       F       F       F
Bank Sta=6300.75,6546.02
XS Rating Curve= 0 ,0
Exp/Cntr=0.3,0.1

Type RM Length L Ch R = 1 ,116211  ,785.21,2241.73,739.29
BEGIN DESCRIPTION:
LOB - Bois D'Arc, ROB - Dallas LID14/Ellis LID3
ROB IFA station 18461: flow expansion due to natural high ground upstream
END DESCRIPTION:
XS GIS Cut Line= 5
     2585944.032     6884510.862     2583333.374     6882355.269
     2581389.228     6882435.162     2580590.329     6881450.457
       2563367.6     6872220.352
#Sta/Elev= 30
       0  385.96   91.21  364.89 1065.04  342.66 1141.18  361.61 1238.75  344.76
 1766.31   355.3 2221.93  335.08 3238.73  333.51  3355.6  362.19 3980.32  345.52
 4060.59  310.64 4205.73  345.06    6757  345.41  7887.7  345.86 8025.89  349.25
 8071.31  372.13 8363.02   332.7 9331.79   362.4 9570.76  335.8810522.81  348.41
   16749  345.3418887.42  338.9119140.57   346.119191.16  368.1219299.06  339.21
19381.64  369.3819457.52  344.3921321.25  349.8324773.52  341.6926140.52  395.74
#Mann= 10 ,-1 , 0
       0     .06       0   91.21     .06       0 1766.31     .15       0
 3980.32    .055       0 4205.73     .15       0    6757     .05       0
  7887.7      .1       010522.81     .05       0   16749      .1       0
21321.25     .06       0
Levee=-1,3355.6,362.19,-1,6627.08,357.69,,
#XS Ineff= 3 ,-1
       0  3355.6     370 6627.09   18461     370   1846126140.52     380
Permanent Ineff=
       F       F       F
Bank Sta=3980.32,4205.73
XS Rating Curve= 0 ,0
Exp/Cntr=0.3,0.1

Type RM Length L Ch R = 1 ,113969  ,147.93,1413.33,1346.26
BEGIN DESCRIPTION:
LOB - Bois D'Arc, ROB - Dallas LID14/Ellis LID3
ROB IFA station 18189: flow expansion due to natural high ground upstream
END DESCRIPTION:
XS GIS Cut Line= 4
     2586091.755     6883602.693      2583678.94     6881674.698
     2579642.858     6880103.664     2563506.489     6872081.463
#Sta/Elev= 30
       0  382.66   159.6  354.63  1048.5  352.24 1794.21  333.06 2969.13   333.9
  3093.5  360.77 3261.33  344.94 5016.81  345.45 5096.83  310.35 5258.88  345.24
 5750.62  331.14 5831.83  356.07  5940.4  344.43 7201.38  345.08 7412.86  370.84
 7501.14  341.52 8182.78  346.22 9844.37  343.1212740.14  344.7316078.38  344.55
16502.85   341.616522.41  358.0216819.29  338.7720344.84  337.9920413.57  354.79
 20542.7   341.620591.31  367.2820672.55   345.323676.91  340.5625440.86  404.09
#Mann= 11 ,-1 , 0
       0     .06       0  1048.5     .15       0 5016.81    .055       0
 5258.88     .15       0  5940.4     .05       0 7201.38      .1       0
 8182.78     .05       0 9844.37      .1       012740.14     .05       0
16078.38      .1       020672.55     .06       0
Levee=-1,3098.5,360.77,-1,5836.82,356.19,,
#XS Ineff= 3 ,-1
       0  3098.5     370 5837.07   18189     370   1818925440.86     380
Permanent Ineff=
       F       F       F
Bank Sta=5016.81,5258.88
XS Rating Curve= 0 ,0
Exp/Cntr=0.3,0.1

Type RM Length L Ch R = 1 ,112556  ,1808.05,2425.98,739.38
BEGIN DESCRIPTION:
LOB - Bois D'Arc, ROB - Dallas LID14/Ellis LID3
ROB IFA station 18373: flow expansion due to natural high ground upstream
END DESCRIPTION:
XS GIS Cut Line= 5
       2585804.9     6882984.953     2583737.924     6881552.473
     2582268.896     6879518.792     2580440.598     6879109.695
     2562759.961     6871491.186
#Sta/Elev= 30
       0  356.27   458.5  349.92 1027.81  333.76 2459.89  332.55 2584.82  361.08
 2671.59   344.7 4322.59     344 4399.32  309.97 4567.55  341.17 5218.84  343.64
 9568.96  343.7612403.64  346.0613546.54  342.7214001.42  347.7916296.95  348.34
17757.01   339.818047.48  342.6918090.18  362.7918294.91  338.5318723.42  344.35
18807.48  363.1219124.28  345.8519370.51  366.9519768.17  346.2920362.28  358.15
20523.92  342.9523102.89  340.8824674.92  386.9625794.75  383.0726209.19  403.82
#Mann= 11 ,-1 , 0
       0     .06       0   458.5     .15       0 4322.59    .055       0
 4567.55     .15       0 5218.84     .05       0 9568.96      .1       0
12403.64     .05       013546.54      .1       014001.42     .05       0
16296.95      .1       020362.28     .06       0
Levee=-1,2584.82,361.08,-1,5083.59,356.56,,
#XS Ineff= 3 ,-1
       0 2584.82     370 5083.57   18373     370   1837326209.19     380
Permanent Ineff=
       F       F       F
Bank Sta=4322.59,4567.55
XS Rating Curve= 0 ,0
Exp/Cntr=0.3,0.1

Type RM Length L Ch R = 6 ,112555.9,,,
BEGIN DESCRIPTION:
Spill to East Fork
END DESCRIPTION:
Lateral Weir Pos= 0
Lateral Weir End=Trinity River   ,1               ,83613   ,
Lateral Weir Distance=0
Lateral Weir TW Multiple XS=0
Lateral Weir WD=20
Lateral Weir Coef=0.5
LW OverFlow Method 2D=0
LW OverFlow Use Velocity Into 2D=0
Lateral Weir WSCriteria=-1
Lateral Weir Flap Gates= 0
Lateral Weir Hagers EQN= 0 ,,,,,
Lateral Weir SS=0.05,0.05,
Lateral Weir Type= 0
Lateral Weir Connection Pos and Dist= 0 ,
Lateral Weir SE= 30
       0  356.25  332.53  350.37   371.6  353.03 1150.58  346.62 1537.82  354.43
 2270.43  356.13 2811.64  352.95 3240.91  354.64  3631.1  350.78 3930.46  353.58
 5066.88  355.14  5304.3  352.61  6065.1  354.13 6593.92  351.92 7570.23  364.25
 7933.66  378.82 8898.18   383.7 8923.29   380.8 9280.11  376.31 9577.02  380.38
 9834.14     373   10683  363.4811119.45  361.9411294.72  363.2311354.82  367.26
11371.39  364.2311443.15  362.53   11600   372.811658.15  372.0811748.17   364.1
Lateral Weir Centerline= 6
2585804.899634426882984.953209122587251.912076566878253.03769988
2587990.309067316877948.335732282588258.879669166876188.25399038
2589511.295401726875412.822347912590625.797712836873699.69922657
LW Div RC= 0 ,False,,

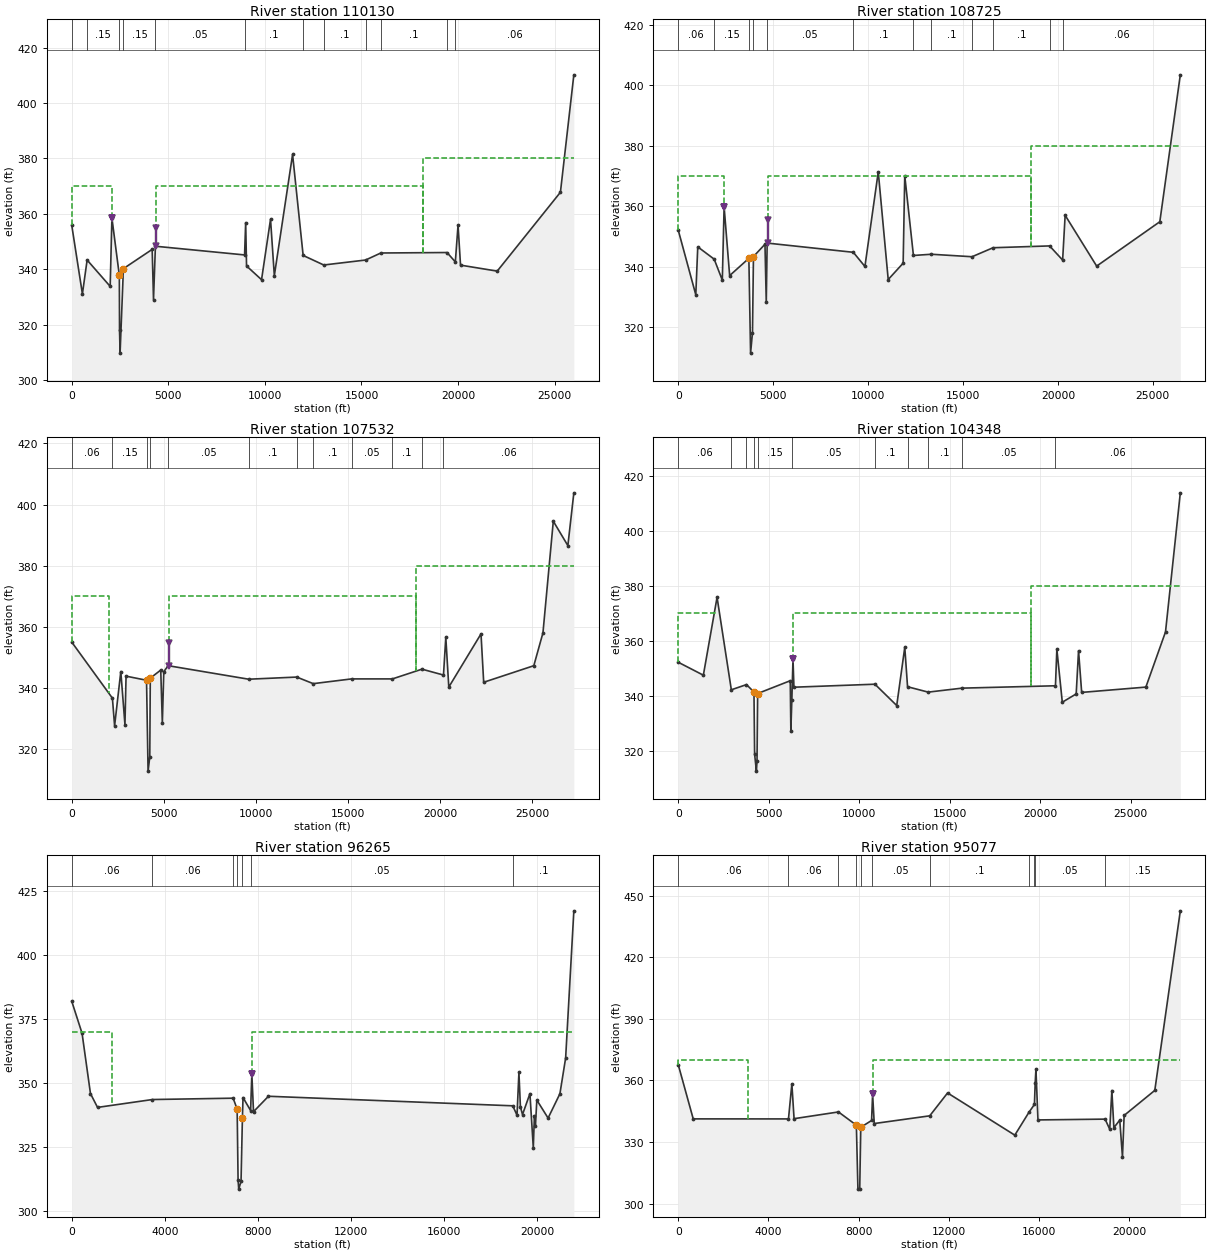
Type RM Length L Ch R = 1 ,110130  ,1466.65,1404.73,264.23
BEGIN DESCRIPTION:
LOB - Bois D'Arc, ROB - Dallas LID14/Ellis LID3
ROB IFA station 18172: flow expansion due to natural high ground upstream
END DESCRIPTION:
XS GIS Cut Line= 6
     2586262.889     6880907.974     2584444.605     6879911.516
     2583586.604     6879971.917     2582737.646     6878879.903
      2580370.91       6878386.5     2562568.989     6871074.519
#Sta/Elev= 30
       0  355.84  550.58  331.14  795.01  343.36 1988.81  333.85 2078.42   358.5
 2462.45  337.85 2472.91  318.02 2501.58  309.78 2673.18  340.25 4162.76   347.2
 4231.97   329.1 4330.13  348.34 8947.24   345.2 9003.47  356.86 9048.75  341.22
 9825.57  336.2710290.49  358.0610487.69  337.7411432.32  381.4411979.33  345.02
13046.22  341.5715210.35  343.3616001.13   345.919427.69  346.0719858.94  342.69
19999.03  355.9420127.81  341.5222026.83  339.3625299.58  367.8125994.54  410.17
#Mann= 12 ,-1 , 0
       0     .06       0  795.01     .15       0 2462.45    .055       0
 2673.18     .15       0 4330.13     .05       0 8947.24      .1       0
11979.33     .05       013046.22      .1       015210.35     .05       0
16001.13      .1       019427.69     .05       019858.94     .06       0
Levee=-1,2078.42,358.5,-1,4345.46,354.96,,
#XS Ineff= 3 ,-1
       0 2078.42     370 4345.07   18172     370   1817225994.54     380
Permanent Ineff=
       F       F       F
Bank Sta=2462.45,2673.18
XS Rating Curve= 0 ,0
Exp/Cntr=0.3,0.1

Type RM Length L Ch R = 1 ,108725  ,1186.89,1193.33,695.83
BEGIN DESCRIPTION:
LOB - Bois D'Arc, ROB - Dallas LID14/Ellis LID3
ROB IFA station 18591: flow expansion due to natural high ground upstream
END DESCRIPTION:
XS GIS Cut Line= 5
     2586988.651     6879984.728     2585018.827      6878567.75
     2582706.327     6878671.917     2580424.382     6878185.459
     2562516.905     6870796.741
#Sta/Elev= 30
       0  352.13  924.84  330.74 1028.29  346.59 1893.33  342.52    2322  335.58
 2416.54  359.83  2708.8  337.08 3721.05  342.79  3811.2  311.42 3911.73  318.19
 3962.76  343.37 4569.42  347.46 4637.55  328.23 4684.98  347.84 9222.72  344.79
 9834.86   340.110537.58  371.4111061.39  335.7811848.95  341.1911932.97  370.14
 12390.1  343.7413336.15  344.1415477.19  343.3216586.04   346.319563.45   346.9
20250.32  342.2220382.85  357.0322043.72  340.2225369.97   354.926449.92  403.52
#Mann= 12 ,-1 , 0
       0     .06       0 1893.33     .15       0 3721.05    .055       0
 3962.76     .15       0 4684.98     .05       0 9222.72      .1       0
 12390.1     .05       013336.15      .1       015477.19     .05       0
16586.04      .1       019563.45     .05       020250.32     .06       0
Levee=-1,2416.54,359.83,-1,4719.96,355.32,,
#XS Ineff= 3 ,-1
       0 2416.54     370 4720.04   18591     370   1859126449.92     380
Permanent Ineff=
       F       F       F
Bank Sta=3721.05,3962.76
XS Rating Curve= 0 ,0
Exp/Cntr=0.3,0.1

Type RM Length L Ch R = 1 ,107532  ,1037.27,3183.75,659.24
BEGIN DESCRIPTION:
ROB - Dallas LID14/Ellis LID3
LOB IFA station 2008: flow expansion due to Bois D'Arc levee upstream
ROB IFA station 18676: flow expansion due to natural high ground upstream
END DESCRIPTION:
XS GIS Cut Line= 5
     2587214.015     6878546.995     2585482.484     6877434.648
     2582272.183     6877502.519     2580529.243     6877510.806
      2561648.85     6870241.186
#Sta/Elev= 30
       0  355.06  2206.6  336.75 2324.95  327.73 2661.98  345.45 2886.92  328.11
 2946.88  343.95 4058.67  342.61 4141.97  312.93 4234.63  317.57 4262.58  343.29
 4830.06  345.94 4916.76   328.6  4995.3  345.38 5229.58  347.37 9602.06  342.95
12212.69  343.6513108.48   341.515191.19  343.0517405.58  343.05 19010.2  346.23
20178.41  344.3120304.07  356.6320466.76  340.3822215.42  357.75 22361.1  341.95
25081.37  347.3625577.96  358.0826139.72  394.5526930.64  386.5827255.17  403.82
#Mann= 12 ,-1 , 0
       0     .06       0  2206.6     .15       0 4058.67    .055       0
 4262.58     .15       0 5229.58     .05       0 9602.06      .1       0
12212.69     .05       013108.48      .1       015191.19     .05       0
17405.58      .1       0 19010.2     .05       020178.41     .06       0
Levee=0,,,-1,5263.36,354.63,,
#XS Ineff= 3 ,-1
       0    2008     370 5263.37   18676     370   1867627255.17     380
Permanent Ineff=
       F       F       F
Bank Sta=4058.67,4262.58
XS Rating Curve= 0 ,0
Exp/Cntr=0.3,0.1

Type RM Length L Ch R = 1 ,104348  ,1720.81,8083.46,4276.21
BEGIN DESCRIPTION:
ROB - Dallas LID14/Ellis LID3
LOB IFA station 2091: flow blocked at natural high ground
ROB IFA station 19491: flow expansion due to natural high ground upstream
END DESCRIPTION:
XS GIS Cut Line= 6
     2587959.751      6877462.12     2584395.378     6876361.093
      2583731.07     6875844.172     2580450.933     6876525.908
      2575638.85     6875144.808     2561891.905     6869859.241
#Sta/Elev= 30
       0  352.26 1387.58  347.55 2144.66  375.87 2932.52  342.24 3769.51  344.13
  4183.4  341.42 4218.77  318.86 4317.71  312.66 4351.15  316.23 4386.78  340.88
 6187.54  345.54 6220.33  327.42 6275.76  338.64 6339.09  353.48 6389.68  343.18
 10865.3  344.2712068.66  336.5212513.24   357.712666.27  343.3513806.08  341.39
15676.84  342.8420836.46   343.720913.16  356.9821214.51  337.7221981.43  340.74
22111.55  356.4622284.05  341.2925829.78  343.2226914.69  363.28 27732.7  413.87
#Mann= 11 ,-1 , 0
       0     .06       0 2932.52     .06       0 3769.51     .15       0
  4183.4    .055       0 4386.78     .15       0 6275.76     .05       0
 10865.3      .1       012666.27     .05       013806.08      .1       0
15676.84     .05       020836.46     .06       0
Levee=0,,,-1,6339.09,353.48,,
#XS Ineff= 3 ,-1
       0    2091     370 6338.03   19491     370   19491 27732.7     380
Permanent Ineff=
       F       F       F
Bank Sta=4183.4,4386.78
XS Rating Curve= 0 ,0
Exp/Cntr=0.3,0.1

Type RM Length L Ch R = 1 ,96265   ,1483.83,1188.02,1196.23
BEGIN DESCRIPTION:
ROB - Dallas LID14/Ellis LID3
LOB IFA station 1717: flow expansion due to natural high ground upstream
END DESCRIPTION:
XS GIS Cut Line= 4
     2588505.007     6875781.772     2584879.573     6874669.972
     2579399.972     6872554.087     2569704.405     6865536.324
#Sta/Elev= 30
       0  381.97  442.56   369.5  803.83  345.96 1107.88  340.57 3464.47  343.64
 6936.88  344.17  7109.5  339.88 7148.95  312.28 7177.18  308.66 7276.27  311.65
 7335.69  336.59  7361.7  344.42 7687.49  339.35 7740.77  353.59  7812.9  338.89
 8454.78  344.9218958.26  341.1919139.77  337.5119221.88   354.219285.88  340.82
19375.95  337.7819694.72  345.9419839.85  324.8419888.09  337.3519931.03  333.18
19991.59  343.4320475.66   336.420983.95   345.921230.28  359.8721582.92  417.32
#Mann= 7 ,-1 , 0
       0     .06       0 3464.47     .06       0 6936.88     .15       0
  7109.5    .055       0 7335.69     .15       0 7687.49     .05       0
18958.26      .1       0
Levee=0,,,-1,7740.77,353.59,,
#XS Ineff= 2 , 0
       0    1717     370 7740.21       0     370
Permanent Ineff=
       F       F
Bank Sta=7109.5,7335.69
XS Rating Curve= 0 ,0
Exp/Cntr=0.3,0.1

Type RM Length L Ch R = 1 ,95077   ,1759.01,3098.93,2125.14
BEGIN DESCRIPTION:
ROB - Dallas LID14/Ellis LID3
LOB IFA station 3088: flow expansion due to natural high ground upstream
END DESCRIPTION:
XS GIS Cut Line= 4
     2589788.177     6874622.495     2589245.262     6874544.293
     2580213.774     6871740.284     2570155.794     6864616.186
#Sta/Elev= 30
       0  367.72  664.27  341.29 4886.42  341.27 5036.25  358.35 5134.01  341.39
 7101.49  344.67 7895.14  338.22 7964.34  307.05 8044.15  307.05 8091.33   337.2
 8569.44  340.51 8615.35  353.33 8687.44  339.0211147.39  342.7811938.23  353.93
 14917.9  333.3615544.08  344.4915787.85  348.3215821.34  358.8615854.25  365.51
15944.49  340.7818919.48  341.1719125.61  336.2519219.92  355.1219309.16  337.01
19569.22  340.6919689.88  322.75 19763.6  342.9721122.58  355.1722253.59   442.7
#Mann= 11 ,-1 , 0
       0     .06       0 4886.42     .06       0 7101.49     .15       0
 7895.14    .055       0 8091.33     .15       0 8569.44     .05       0
11147.39      .1       015544.08     .05       015787.85     .15       0
15821.34     .05       018919.48     .15       0
Levee=0,,,-1,8615.35,353.33,,
#XS Ineff= 2 , 0
       0    3088     370 8614.84       0     370
Permanent Ineff=
       F       F
Bank Sta=7895.14,8091.33
XS Rating Curve= 0 ,0
Exp/Cntr=0.3,0.1

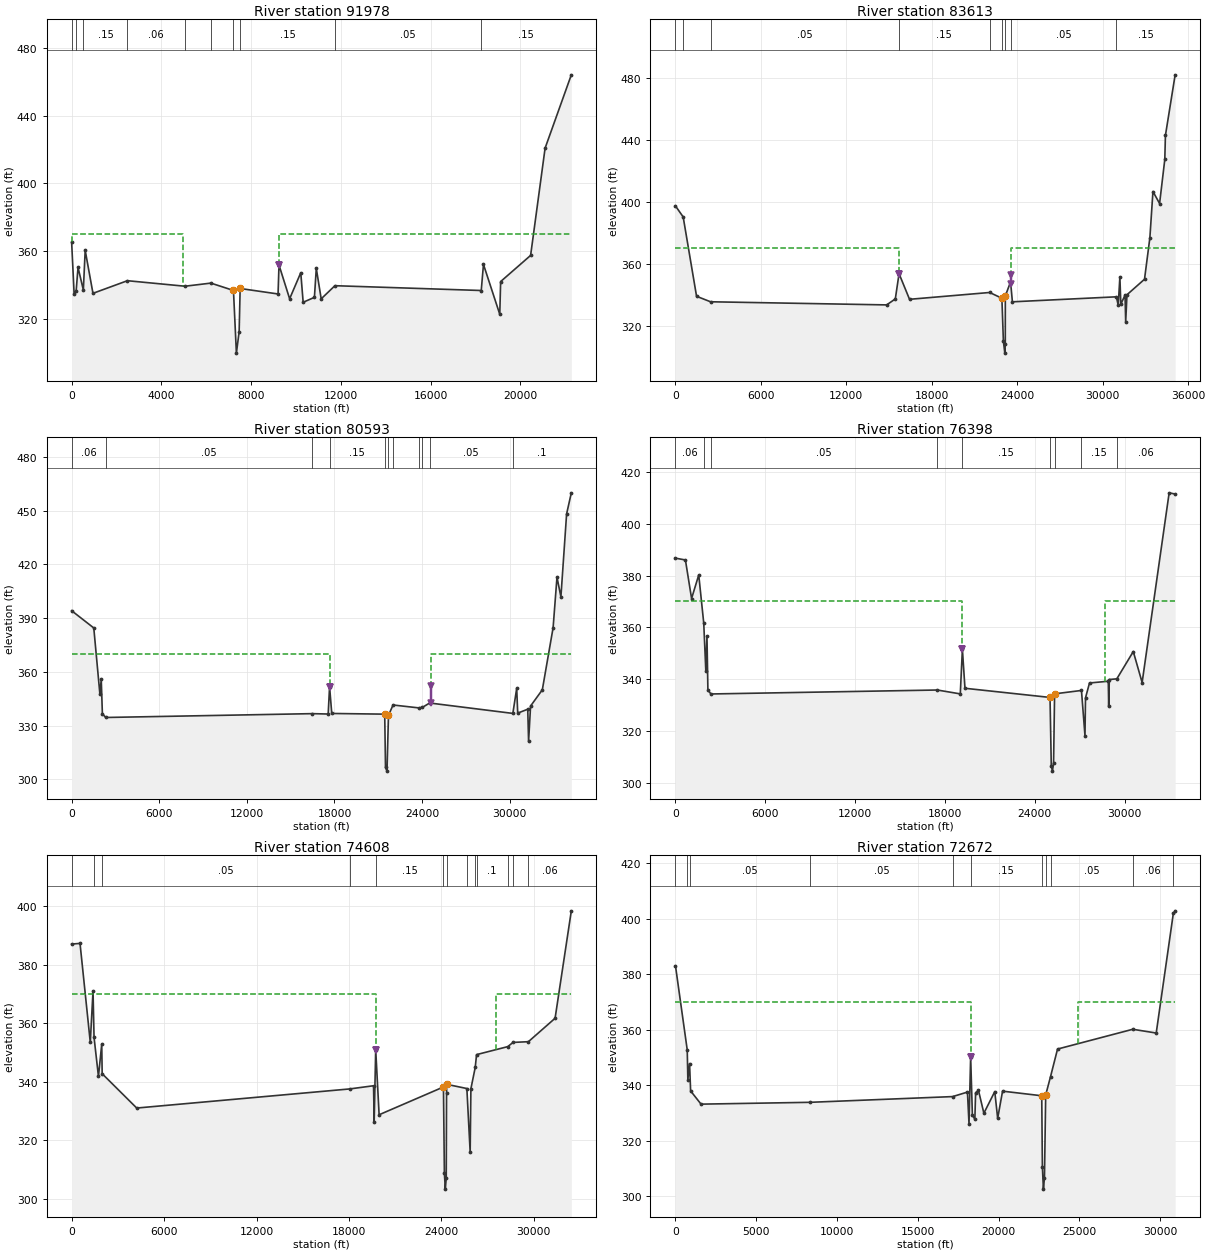
Type RM Length L Ch R = 1 ,91978   ,4138.76,8364.88,1686.69
BEGIN DESCRIPTION:
ROB - Dallas LID14/Ellis LID3
LOB IFA station 3088: flow expansion due to natural high ground upstream
END DESCRIPTION:
XS GIS Cut Line= 4
     2590625.798     6873699.699     2589782.682     6873544.148
     2581579.557      6869985.12     2570937.044     6863505.074
#Sta/Elev= 30
       0  365.13  109.35  334.88  201.58  336.47  284.32  350.34  521.47  336.98
  603.74  360.39  950.43  335.01 2486.36  342.47 5052.56  339.21 6207.56  341.05
 7214.87  336.71  7345.3  299.69 7468.33  312.42 7512.83  337.87 9203.08  334.63
 9244.69  351.73 9718.85   331.810215.64  347.19 10322.3  329.7310824.22  332.64
10907.49  349.7411126.28  331.7611738.14  339.5218262.54  336.6818361.42   352.1
 19088.2  322.63 19127.3  341.9620463.34  357.4121109.56  420.7822278.61  464.08
#Mann= 10 ,-1 , 0
       0      .1       0  201.58     .06       0  521.47     .15       0
 2486.36     .06       0 5052.56     .15       0 6207.56     .15       0
 7214.87    .055       0 7512.83     .15       011738.14     .05       0
18262.54     .15       0
Levee=0,,,-1,9244.69,351.73,,
#XS Ineff= 2 , 0
       0    4947     370 9245.09       0     370
Permanent Ineff=
       F       F
Bank Sta=7214.87,7512.83
XS Rating Curve= 0 ,0
Exp/Cntr=0.3,0.1

Type RM Length L Ch R = 1 ,83613   ,1518.94,3020.05,1285.42
BEGIN DESCRIPTION:
LOB - Kaufman MUD1, ROB - Dallas LID14/Ellis LID3
END DESCRIPTION:
XS GIS Cut Line= 5
 2603730.71705116874962.430372162589554.058159446867922.78274316
2582787.478298336868020.815150572581851.714409446867784.70403946
2571296.158853886863163.17626168
#Sta/Elev= 30
       0  397.32  540.81  390.23 1480.71  339.04 2461.87   335.514828.84  333.48
15435.57  337.3415698.16  353.6316433.92  337.09 22060.2  341.4922918.43  337.78
23023.94  310.1423124.06  302.3723156.99  308.27 23160.3  339.2523528.43  348.36
23656.09  335.47 30958.4   338.7 31086.6  333.2431202.91   351.431269.87  333.96
31565.77  339.7931610.92  322.4731700.83  340.0332932.54  350.0433309.22  376.78
33524.86  406.6433991.07  398.8934357.37  427.3634400.71   442.835083.67  481.91
#Mann= 9 ,-1 , 0
       0     .05       0  540.81     .06       0 2461.87     .05       0
15698.16     .15       0 22060.2     .15       022918.43    .055       0
 23160.3     .15       023528.43     .05       0 30958.4     .15       0
Levee=-1,15698.16,353.63,-1,23541.78,353,,
#XS Ineff= 2 , 0
       015698.94     37023541.72       0     370
Permanent Ineff=
       F       F
Bank Sta=22918.43,23160.3
XS Rating Curve= 0 ,0
Exp/Cntr=0.3,0.1

Type RM Length L Ch R = 1 ,80593   ,1304.95,4194.89,2623.31
BEGIN DESCRIPTION:
LOB - Kaufman MUD1, ROB - Dallas LID14/Ellis LID3
END DESCRIPTION:
XS GIS Cut Line= 6
2604850.392977026873169.60629808 2588498.97540486866569.52707184
2584746.024015916866460.15207184 2584447.41290486866460.15207184
2582244.114293696866392.443738512572504.492187216862954.84292834
#Sta/Elev= 30
       0  394.15  1516.1  384.52 1932.41  347.79  2026.7   355.8 2104.64   336.7
 2330.28  334.5816478.23  336.7217568.33  336.5117663.45  351.74 17813.6  336.82
 21439.5  336.4421493.62   306.721595.69  304.6521696.77  335.7322009.81  341.55
23755.07  339.9524019.96  340.2224517.68  342.6630214.87  336.8530477.93  350.79
30547.66  337.0131235.09  339.1931292.71  321.24 31428.5  340.9732233.27  350.02
 32971.5  384.6633237.13  412.85 33505.8  401.8833895.88  448.14 34219.2  459.92
#Mann= 11 ,-1 , 0
       0     .06       0 2330.28     .05       016478.23     .15       0
17663.45     .15       0 21439.5    .055       021696.77     .15       0
22009.81     .06       023755.07     .15       024019.96     .06       0
24517.68     .05       030214.87      .1       0
Levee=-1,17663.45,351.74,-1,24580.11,352,,
#XS Ineff= 2 , 0
       017663.57     37024580.11       0     370
Permanent Ineff=
       F       F
Bank Sta=21439.5,21696.77
XS Rating Curve= 0 ,0
Exp/Cntr=0.3,0.1

Type RM Length L Ch R = 1 ,76398   ,1366.66,1790.14,1812.24
BEGIN DESCRIPTION:
LOB - Kaufman MUD1
ROB IFA station 28654: flow expansion due to Dallas LID14/Ellis LID3 levee upstream
END DESCRIPTION:
XS GIS Cut Line= 4
2606496.303529836870144.903692242582555.794270566864008.95461815
2581795.377603896863650.621284822574149.081307596862047.68147001
#Sta/Elev= 30
       0  386.75  664.16  386.05 1075.59  371.15 1553.77  380.26 1887.39  361.67
 2028.38     343 2102.55  356.67 2165.46  335.77 2369.57  334.26 17484.7  335.79
19019.32  334.2919159.68  351.5219332.29  336.4625011.92  332.9225095.98  306.48
25173.32  304.4425249.32   307.725316.97  334.3127111.45  335.6227346.03  318.15
27381.17  332.7527648.06  338.5128902.27  339.1828930.64  329.4228969.84  339.84
29472.69  340.1130572.04  350.6631162.57  338.6932967.12     41233367.44  411.53
#Mann= 9 ,-1 , 0
       0     .06       0 1887.39      .1       0 2369.57     .05       0
 17484.7     .15       019159.68     .15       025011.92    .055       0
25316.97     .06       027111.45     .15       029472.69     .06       0
Levee=-1,19159.68,351.52,0,,,,
#XS Ineff= 2 , 0
       019160.35     370   28654       0     370
Permanent Ineff=
       F       F
Bank Sta=25011.92,25316.97
XS Rating Curve= 0 ,0
Exp/Cntr=0.3,0.1

Type RM Length L Ch R = 1 ,74608   ,1431.86,1935.4,1883.95
BEGIN DESCRIPTION:
LOB - Kaufman MUD1
ROB IFA station 27520: flow contraction due to Ellis LID2 levee downstream
END DESCRIPTION:
XS GIS Cut Line= 4
2607172.70399279 6868220.89906262583937.460937236863102.84350704
2579097.669270566859799.892118152576528.224826116858723.50322926
#Sta/Elev= 30
       0  386.99  544.02  387.21 1209.35  353.46 1387.84  371.06  1453.2   355.2
 1739.91  341.83 1952.79   352.8 1981.77  342.74 4224.41  331.0318049.59  337.55
19598.54  338.6419639.09  326.3419738.14  350.9919959.74  328.7424137.05  338.22
24196.64  308.8824256.73  303.3624317.16  307.0724337.97  336.15 24351.3  339.12
25656.08  337.6925870.55  315.9925918.44  337.6326199.21  344.8826285.54  349.26
28312.69  351.9928652.85  353.4329650.73  353.6731383.55  361.6732437.45  398.33
#Mann= 13 ,-1 , 0
       0     .06       0  1453.2      .1       0 1981.77     .05       0
18049.59     .15       019738.14     .15       024137.05    .055       0
 24351.3     .06       025656.08     .15       026199.21     .06       0
26285.54      .1       028312.69     .06       028652.85     .05       0
29650.73     .06       0
Levee=-1,19738.14,350.99,0,,,,
#XS Ineff= 2 , 0
       019738.01     370   27520       0     370
Permanent Ineff=
       F       F
Bank Sta=24137.05,24351.3
XS Rating Curve= 0 ,0
Exp/Cntr=0.3,0.1

Type RM Length L Ch R = 1 ,72672   ,1501.06,1619.39,1672.71
BEGIN DESCRIPTION:
LOB - Kaufman MUD1
ROB IFA station 24899: flow contraction due to Ellis LID2 levee downstream
END DESCRIPTION:
XS GIS Cut Line= 5
2606198.363715026866971.767118162588441.419270566862638.43378482
2583873.020374556860934.26640181  2579635.8637156859339.82267371
2576476.141492786858575.93378482
#Sta/Elev= 30
       0  383.01   727.2  352.74  766.89  341.94  871.99  347.76  937.51  337.91
 1582.58  333.15 8340.55  333.8117154.88  335.8718074.57  337.4918170.86  326.06
18272.61  350.1918379.52  329.3318533.11  327.6518579.39  337.2818758.24  338.07
19091.29  329.8819765.68  337.6719945.51  328.0220247.72  337.8322673.05  336.17
22712.98  310.65 22777.3  302.5222842.09  306.6622918.57  336.4623219.55   343.1
23651.49     353 28308.2  360.1329760.24  358.7830818.87  401.8830931.89  402.82
#Mann= 11 ,-1 , 0
       0     .06       0   727.2      .1       0  871.99     .05       0
 8340.55     .05       017154.88     .15       018272.61     .15       0
22673.05    .055       022918.57     .15       023219.55     .05       0
 28308.2     .06       030818.87     .06       0
Levee=-1,18272.61,350.19,0,,,,
#XS Ineff= 2 , 0
       018272.99     370   24899       0     370
Permanent Ineff=
       F       F
Bank Sta=22673.05,22918.57
XS Rating Curve= 0 ,0
Exp/Cntr=0.3,0.1

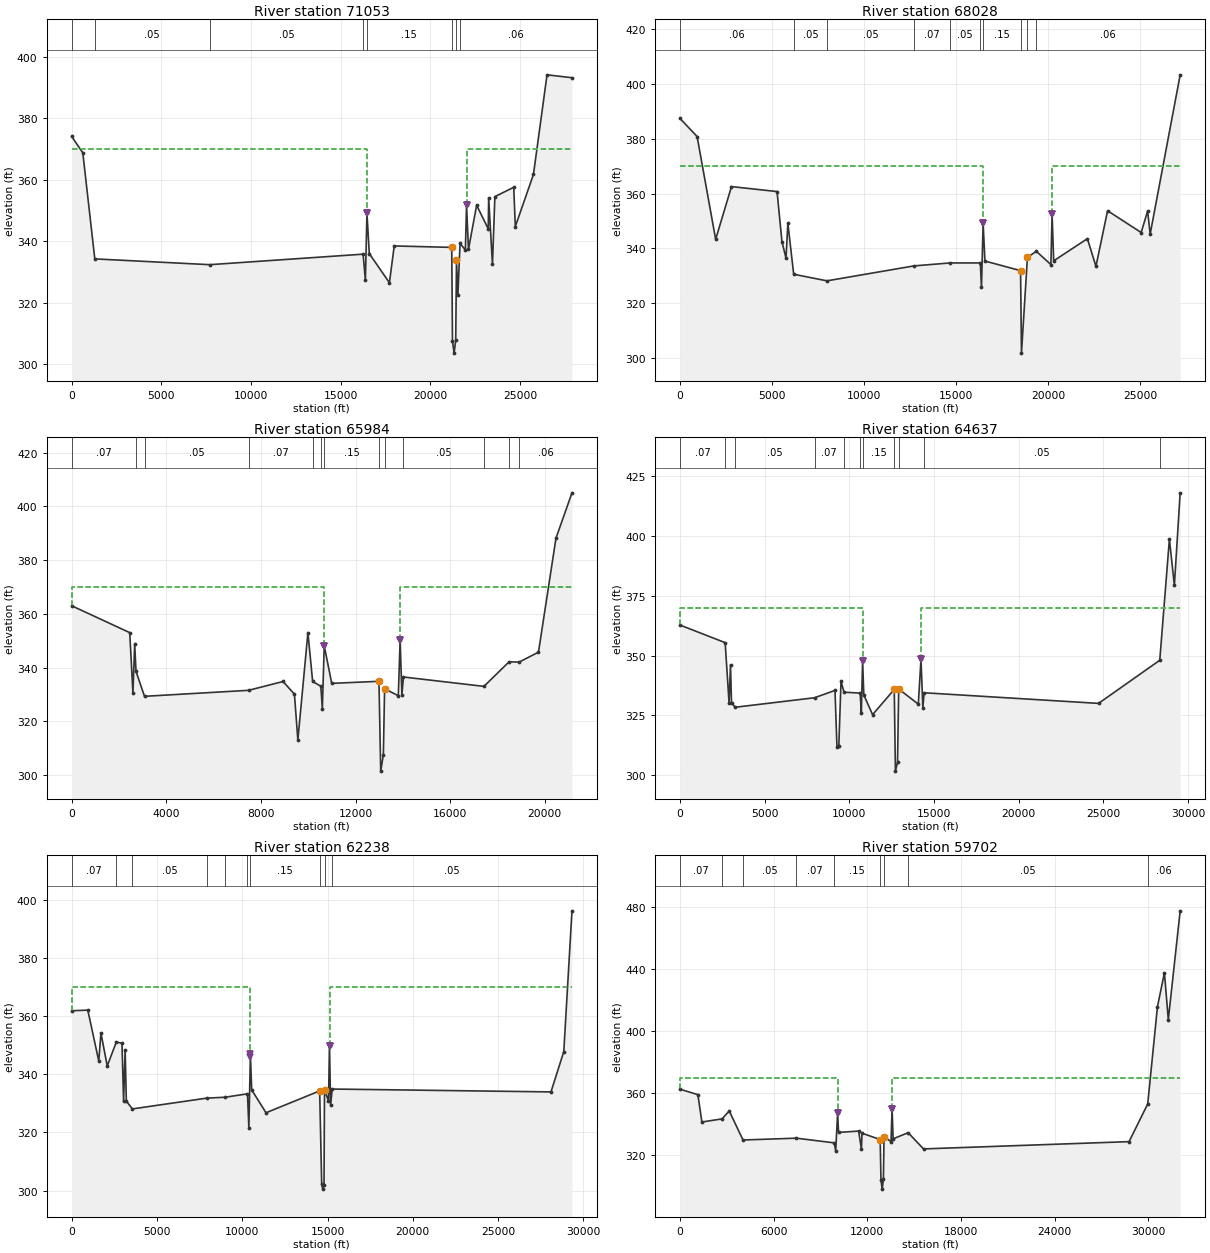
Type RM Length L Ch R = 1 ,71053   ,2459.34,3024.49,2512.9
BEGIN DESCRIPTION:
LOB - Kaufman MUD1, ROB - Ellis LID2
END DESCRIPTION:
XS GIS Cut Line= 5
2605863.33767335 6862699.80531262589491.809895566861397.72197927
2585316.462673346860060.916423712584586.601562236859133.13864593
2578762.64322889 6858090.4303126
#Sta/Elev= 30
       0  374.05  619.76  368.76 1289.43  334.25 7702.91  332.3716253.83  335.79
16381.42  327.3416468.21  349.1416598.92  335.9817721.62  326.4917989.07  338.46
21197.53  337.9921239.12  307.5521329.45  303.6121420.01  307.87 21462.5  333.79
21539.34  322.4721661.53  339.3521958.48  337.1222022.37  351.7122131.22  337.35
22586.16   351.723233.27  344.0223256.45  354.0823468.82   332.5 23604.2   354.5
24655.53  357.5324743.94  344.7825755.54  361.7126512.19   394.127904.46  393.16
#Mann= 8 ,-1 , 0
       0     .06       0 1289.43     .05       0 7702.91     .05       0
16253.83     .15       016468.21     .15       021197.53    .055       0
 21462.5     .15       021661.53     .06       0
Levee=-1,16468.21,349.14,-1,22022.37,351.71,,
#XS Ineff= 2 , 0
       016467.63     37022022.37       0     370
Permanent Ineff=
       F       F
Bank Sta=21197.53,21462.5
XS Rating Curve= 0 ,0
Exp/Cntr=0.3,0.1

Type RM Length L Ch R = 1 ,68028   ,2550.09,2044.38,1660.23
BEGIN DESCRIPTION:
LOB - Kaufman MUD1, ROB - Ellis LID2
END DESCRIPTION:
XS GIS Cut Line= 4
2605931.785011316861423.225451462589668.590566876858881.67452554
2586047.062789096857900.771747762579138.035011316857129.47545146
#Sta/Elev= 30
       0   387.5  935.94  380.86 1943.46  343.33 2802.54  362.58 5277.51  360.76
 5543.05  342.47  5763.6  336.46 5863.55  349.23 6180.16  330.58 7986.68  328.17
12702.35  333.6214668.17   334.716313.76  334.7116376.19  325.7416466.15  349.24
16563.36   335.418498.82  331.8918547.94  301.7818871.39  336.7219352.53  338.95
20145.87  334.1120209.69   352.620296.95  335.4722128.28  343.5722591.26  333.46
23223.39  353.76 25046.8  345.81 25397.3  353.6525536.06  345.2527164.56  403.38
#Mann= 10 ,-1 , 0
       0     .06       0 6180.16     .05       0 7986.68     .05       0
12702.35     .07       014668.17     .05       016313.76     .15       0
16466.15     .15       018498.82    .055       018871.39     .15       0
19352.53     .06       0
Levee=-1,16466.15,349.24,-1,20209.69,352.6,,
#XS Ineff= 2 ,-1
       016467.39     37020209.7127164.56     370
Permanent Ineff=
       F       F
Bank Sta=18498.82,18871.39
XS Rating Curve= 0 ,0
Exp/Cntr=0.3,0.1

Type RM Length L Ch R = 1 ,65984   ,761.4,1346.66,1829.69
BEGIN DESCRIPTION:
LOB - Kaufman MUD1, ROB - Ellis LID2
END DESCRIPTION:
XS GIS Cut Line= 4
2599899.674578646857782.477761572589338.451606636856402.66982564
2586149.562643236856597.114318642578859.972563656857045.02648056
#Sta/Elev= 30
       0  363.01 2454.07  353.01 2589.02  330.55 2663.99  348.86 2718.96  338.58
 3078.82  329.31 7477.09  331.54 8936.51  334.83 9416.33  330.09 9561.27  313.02
  9986.1  353.0310186.02  334.8310530.89  333.0710595.86  324.7510676.33  348.07
10993.27  334.1312989.66   334.913063.81  301.4713175.51  307.5413227.37  332.13
13807.24  329.5313884.37  350.3313958.72  329.8914025.36   336.517427.05  333.01
18489.29  342.1518916.26  342.0519732.17  345.7420473.26  388.1821149.13  405.04
#Mann= 13 ,-1 , 0
       0     .07       0 2718.96     .06       0 3078.82     .05       0
 7477.09     .07       010186.02     .05       010530.89     .15       0
10676.33     .15       012989.66    .055       013227.37     .06       0
14025.36     .05       017427.05     .06       018489.29     .05       0
18916.26     .06       0
Levee=-1,10676.33,348.07,-1,13884.37,350.33,,
#XS Ineff= 2 ,-1
       010675.66     37013884.3221149.13     370
Permanent Ineff=
       F       F
Bank Sta=12989.66,13227.37
XS Rating Curve= 0 ,0
Exp/Cntr=0.3,0.1

Type RM Length L Ch R = 1 ,64637   ,1009.07,2399.06,1604.33
BEGIN DESCRIPTION:
LOB - Kaufman MUD1, ROB - Ellis LID2
END DESCRIPTION:
XS GIS Cut Line= 4
2599965.936913316857716.215426892589427.340536486855588.78103347
2585969.007230046855236.003195732570686.948883476854434.65768556
#Sta/Elev= 30
       0  362.84 2674.05  355.45 2903.96  330.26 2988.93  346.18 3048.91  330.12
 3273.83  328.42 7947.17  332.39 9156.71  335.47 9271.66  311.98 9381.62  312.13
 9511.57  339.22  9691.5  334.7110641.13  334.34 10711.1  326.1910786.73  347.98
10856.94  333.5711375.03  325.32 12655.1  335.8812722.57  301.6812847.47  305.35
12917.21  336.05   14074  329.7114232.38  348.5214343.15  328.1414416.02  334.48
24712.42  330.0328326.19  348.0828895.17  398.7729188.35  379.4529530.52  418.16
#Mann= 11 ,-1 , 0
       0     .07       0 2674.05     .06       0 3273.83     .05       0
 7947.17     .07       0  9691.5     .05       010641.13     .15       0
10786.73     .15       0 12655.1    .055       012917.21     .06       0
14416.02     .05       028326.19     .06       0
Levee=-1,10786.76,347.98,-1,14232.38,348.52,,
#XS Ineff= 2 ,-1
       010787.51     37014233.2229530.52     370
Permanent Ineff=
       F       F
Bank Sta=12655.1,12917.21
XS Rating Curve= 0 ,0
Exp/Cntr=0.3,0.1

Type RM Length L Ch R = 1 ,62238   ,934.88,2536.56,1721.21
BEGIN DESCRIPTION:
LOB - Kaufman MUD1, ROB - Ellis LID2
END DESCRIPTION:
XS GIS Cut Line= 5
 2600070.0630174 6857640.48723192589996.437823476854635.30885907
2586090.592944896853892.311001232585441.287484976853906.20008107
2571292.502462396852779.63737357
#Sta/Elev= 30
       0   361.8  944.76  362.01  1589.6   344.5 1714.56  354.18 2084.47  342.84
 2619.34  351.08 2949.25  350.62 3044.23  330.72 3134.21  348.27 3204.19  330.77
  3559.1  328.08 7917.97  331.79 8987.74  332.0910307.48  333.2710387.47  321.62
10477.67  346.8610552.87  334.6311392.43  326.76   14538  334.2714657.47  302.21
14722.48  300.5314793.15  301.8814821.85  334.5615054.51  330.8615115.79  349.72
15180.49  329.3515272.27  334.9128099.84  333.9228850.59  347.7729331.23  396.12
#Mann= 10 ,-1 , 0
       0     .07       0 2619.34     .06       0  3559.1     .05       0
 7917.97     .07       0 8987.74     .05       010307.48     .15       0
10477.67     .15       0   14538    .055       014821.85     .06       0
15272.27     .05       0
Levee=-1,10482.67,346.86,-1,15115.79,349.72,,
#XS Ineff= 2 ,-1
       0 10483.4     37015115.5229331.23     370
Permanent Ineff=
       F       F
Bank Sta=14538,14821.85
XS Rating Curve= 0 ,0
Exp/Cntr=0.3,0.1

Type RM Length L Ch R = 1 ,59702   ,1056.97,2878.56,838.01
BEGIN DESCRIPTION:
LOB - Kaufman MUD1, ROB - Ellis LID2
END DESCRIPTION:
XS GIS Cut Line= 5
 2600117.39330336857574.224897222590721.588932226853876.65125564
2588378.092963076853766.616698822587474.751265796852609.13804264
2569517.328847386850204.46371815
#Sta/Elev= 30
       0  362.63 1154.68  359.07 1409.61  341.48 2704.25   343.5 3159.13  348.59
 4043.89   329.9 7452.94  331.07 9882.27  328.06 9977.25  322.8510099.32  347.32
10159.24  334.7711445.83  335.6411621.68  324.0511661.96  334.2612824.23   330.2
12873.03  304.45 12951.6  298.2713031.31  304.8513070.14  332.0213518.94  328.85
13585.21  350.0913652.52  330.6514614.64   334.6   15599  324.1628757.88  328.84
29952.04   353.130574.18  415.67 31020.4  437.5131270.17  407.4132029.23  477.42
#Mann= 9 ,-1 , 0
       0     .07       0 2704.25     .06       0 4043.89     .05       0
 7452.94     .07       0 9882.27     .15       012824.23    .055       0
13070.14     .15       014614.64     .05       029952.04     .06       0
Levee=-1,10099.32,347.32,-1,13585.21,350.09,,
#XS Ineff= 2 ,-1
       010100.35     37013584.9632029.23     370
Permanent Ineff=
       F       F
Bank Sta=12824.23,13070.14
XS Rating Curve= 0 ,0
Exp/Cntr=0.3,0.1