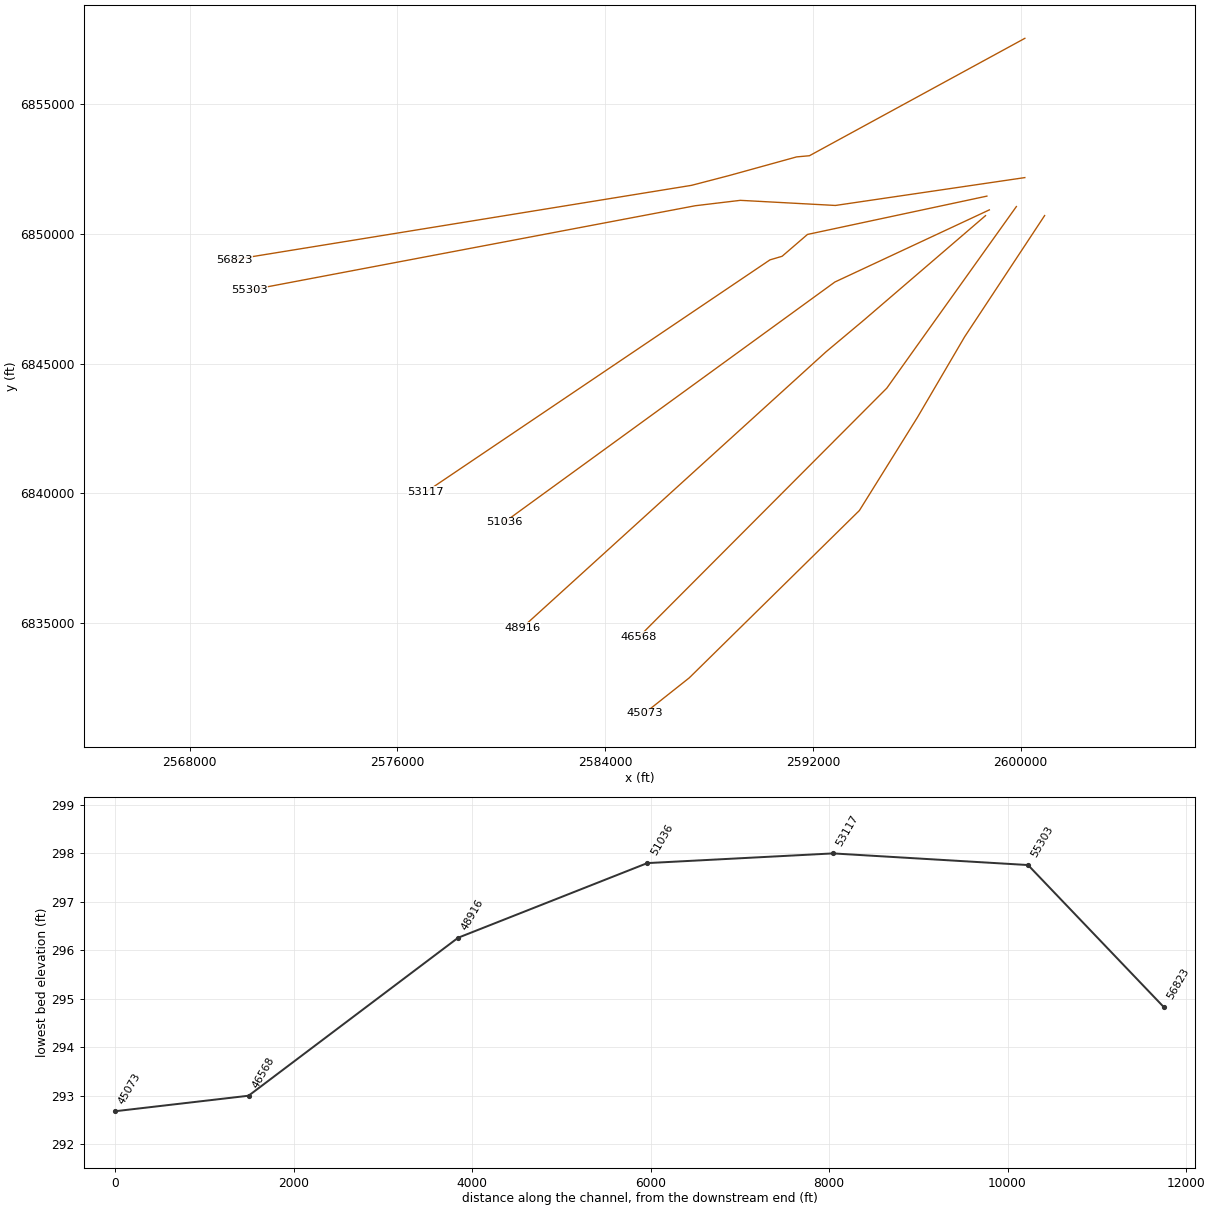
HEC-RAS study TR_FEMA.prj: Trinity_River_FEMA

--- TR_FEMA.g08 (geometry) --- (continued)

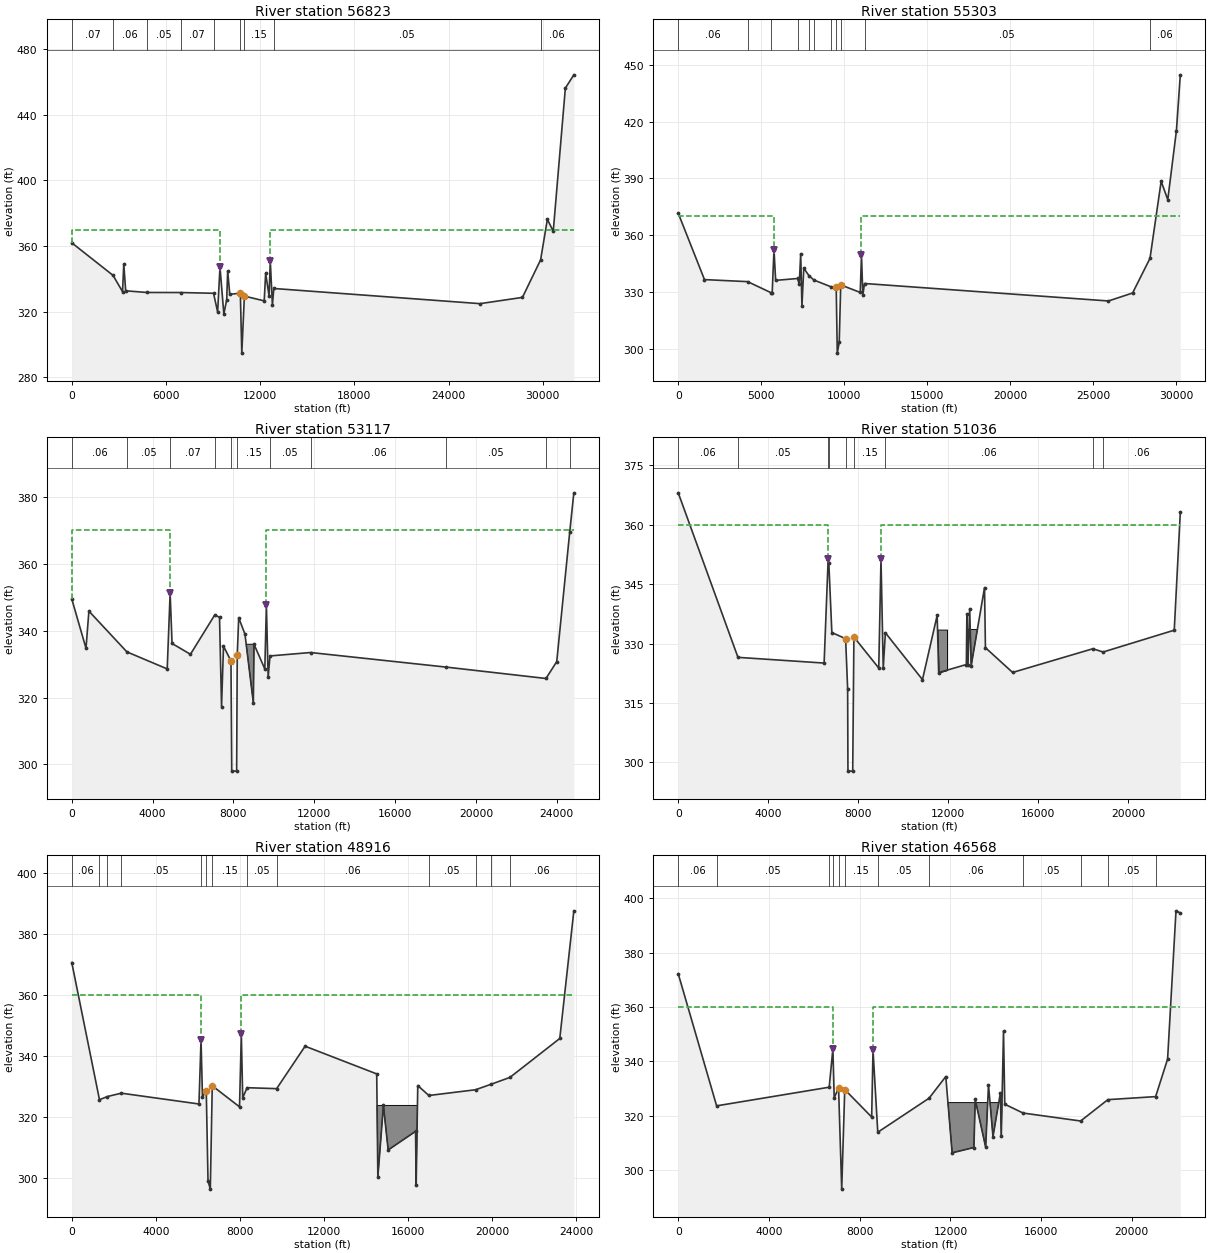
Type RM Length L Ch R = 1 ,56823   ,1814.93,1520.67,905.82
BEGIN DESCRIPTION:
LOB - Kaufman MUD1, ROB - Ellis LID2
END DESCRIPTION:
XS GIS Cut Line= 6
2600164.723589216857545.826660072591868.659144646853018.84982164
2591375.143071296852974.125173552588772.712580656852253.63908173
2587328.241060146851877.223824052569716.981663326849015.22790764
#Sta/Elev= 30
       0  362.01 2628.83  342.19 3233.56  332.27 3313.52  349.09 3433.47  332.78
 4782.89  331.77    6952  331.73 9031.16  331.28 9291.06  319.89 9441.28  347.18
 9686.46  318.71 9869.48  327.38 9931.25  344.8610063.92  330.6410737.48  331.34
10830.73  294.8310995.67  329.5612257.78  326.6612349.83  343.4212568.44  329.76
12644.66  351.0612780.08  324.0812869.66   334.226003.58  324.9628707.25  328.77
29865.42  351.6430294.22  376.3130669.65  369.0431440.07   456.2 31981.7  464.31
#Mann= 9 ,-1 , 0
       0     .07       0 2628.83     .06       0 4782.89     .05       0
    6952     .07       0 9031.16     .15       010737.48    .055       0
10995.67     .15       012869.66     .05       029865.42     .06       0
Levee=-1,9441.28,347.18,-1,12644.66,351.06,,
#XS Ineff= 2 ,-1
       0 9440.25     370 12642.8 31981.7     370
Permanent Ineff=
       F       F
Bank Sta=10737.48,10995.67
XS Rating Curve= 0 ,0
Exp/Cntr=0.3,0.1

Type RM Length L Ch R = 1 ,55303   ,1445.25,2185.82,5056.24
BEGIN DESCRIPTION:
LOB - Kaufman LID1/Henderson LID1, ROB - Ellis LID2
END DESCRIPTION:
XS GIS Cut Line= 5
2600163.400754836852175.874097612592870.282117796851101.55589129
2589209.171006686851298.778113522587475.789913646851091.50307786
2570298.522858526847833.26885425
#Sta/Elev= 30
       0  371.61 1581.82  336.57 4183.88  335.49 5588.81  329.68 5664.35  329.61
 5772.52  352.37 5872.48  336.16 7191.94  337.15  7296.9  334.13 7381.86   350.1
 7457.67  322.57 7567.84   342.6 7884.38  338.58 8186.46  336.31 9217.52  332.75
  9523.9  332.52 9587.79  297.76 9704.98  303.41  9795.5  333.7710971.24   329.8
11047.28  349.3511128.37  328.5511231.58  334.5125935.46  325.2927390.41  329.49
28440.88  347.8229112.58  388.4429512.27  378.7730032.44  415.15 30267.6  444.65
#Mann= 11 ,-1 , 0
       0     .06       0 4183.88     .05       0 5588.81     .07       0
 7191.94      .1       0 7884.38     .07       0 8186.46     .15       0
 9217.52     .05       0  9523.9    .055       0  9795.5     .15       0
11231.58     .05       028440.88     .06       0
Levee=-1,5772.52,352.37,-1,11047.28,349.35,,
#XS Ineff= 2 ,-1
       0 5772.27     37011047.36 30267.6     370
Permanent Ineff=
       F       F
Bank Sta=9523.9,9795.5
XS Rating Curve= 0 ,0
Exp/Cntr=0.3,0.1

Type RM Length L Ch R = 1 ,53117   ,2370.77,2080.68,2424.78
BEGIN DESCRIPTION:
LOB - Kaufman LID1/Henderson LID1, ROB - Ellis LID2
END DESCRIPTION:
XS GIS Cut Line= 5
  2598702.505271 6851461.5101835 2591793.5662614 6849984.0356367
 2590815.2676502 6849141.1536922 2590348.3386047 6849003.1768502
 2577092.3232486 6840049.7655826
#Sta/Elev= 30
       0  349.46  704.03  334.71  847.03  345.83 2727.64  333.64 4721.89  328.55
 4866.64  351.19 4961.57  336.15 5870.93  332.92 7075.07  344.69 7309.78  343.96
 7409.86  317.28  7506.3  335.36 7876.59  330.93 7914.65     298 8156.42     298
 8186.86  332.75 8258.81  343.84 8568.46  338.95 8983.23  318.44 9015.18  335.93
 9551.19  328.54 9628.53  347.66 9715.98  326.05  9806.7  332.4311814.35  333.45
18525.39  329.0923461.93  325.6923993.63  330.7424635.51  369.4524839.83  381.18
#Mann= 11 ,-1 , 0
       0     .06       0 2727.64     .05       0 4866.64     .07       0
 7075.07     .15       0 7876.59    .055       0 8186.86     .15       0
  9806.7     .05       011814.35     .06       018525.39     .05       0
23461.93      .1       024635.51     .06       0
Levee=-1,4866.64,351.19,-1,9628.53,347.66,,
#XS Ineff= 2 ,-1
       0 4865.26     370 9628.5824839.83     370
Permanent Ineff=
       F       F
#Block Obstruct= 1 ,-1
 8274.12  9015.8  335.93
Bank Sta=7876.59,8186.86
XS Rating Curve= 0 ,0
Exp/Cntr=0.3,0.1

Type RM Length L Ch R = 1 ,51036   ,2003.75,2119.69,2544.85
BEGIN DESCRIPTION:
LOB - Kaufman LID1/Henderson LID1, ROB - Ellis LID2
END DESCRIPTION:
XS GIS Cut Line= 3
  2598796.934316 6850931.0148033 2592849.0176502 6848149.7648033
 2580108.8727335  6838879.246163
#Sta/Elev= 30
       0  368.03 2655.86  326.51 6485.69  325.07 6666.02  351.37    6696  350.24
 6829.57  332.78 7441.54  331.22 7531.66  318.56 7545.45   297.8 7756.97   297.8
 7810.45  331.64 8914.66  323.82 9014.57  351.34 9114.73  323.79 9209.35  332.72
 10858.6  320.8911511.65  337.0911578.09  322.6712809.38   324.712832.91  337.47
12878.71  324.6412957.17  338.7713025.04  324.4213617.67  344.1113657.95  328.95
14866.75   322.718432.44  328.6818889.25  327.8622052.62  333.3722322.13  363.14
#Mann= 9 ,-1 , 0
       0     .06       0 2655.86     .05       0 6666.02     .15       0
    6696     .07       0 7441.54    .055       0 7810.45     .15       0
 9209.35     .06       018432.44     .05       018889.25     .06       0
Levee=-1,6666.02,351.37,-1,9014.57,351.34,,
#XS Ineff= 2 ,-1
       0 6663.86     360 9014.6422322.13     360
Permanent Ineff=
       F       F
#Block Obstruct= 2 ,-1
11511.6511950.64  333.5212832.9113617.67  333.52
Bank Sta=7441.54,7810.45
XS Rating Curve= 0 ,0
Exp/Cntr=0.3,0.1

Type RM Length L Ch R = 1 ,48916   ,2124.59,2348.27,2946.84
BEGIN DESCRIPTION:
LOB - Kaufman LID1/Henderson LID1, ROB - Ellis LID2
END DESCRIPTION:
XS GIS Cut Line= 4
   2598649.01765 6850708.0981367 2593949.0176502   6846666.43147
 2592504.5732058 6845455.3203589 2580815.6843169 6834824.7648033
#Sta/Elev= 30
       0  370.67 1318.05  325.63 1699.02  326.68 2359.33  327.77 6050.61  324.22
 6148.76  345.36 6216.82  326.62 6398.52  328.34 6480.95  298.98 6590.29  296.26
 6682.71  330.19 7979.77  323.29 8065.83  347.16  8131.5  326.25 8339.73  329.57
 9745.12  329.2611099.58   343.214506.32   334.114560.31  300.1614824.53  323.75
15051.16  309.1216353.98  315.2316382.98  297.5116458.92  330.2816987.79  327.01
   19209   328.919961.17  330.7420843.19  332.9523214.96  345.7423883.86  387.66
#Mann= 13 ,-1 , 0
       0     .06       0 1318.05     .05       0 1699.02     .06       0
 2359.33     .05       0 6148.76     .09       0 6398.52    .055       0
 6682.71     .15       0 8339.73     .05       0 9745.12     .06       0
16987.79     .05       0   19209     .06       019961.17     .05       0
20843.19     .06       0
Levee=-1,6148.76,345.36,-1,8065.83,347.16,,
#XS Ineff= 2 ,-1
       0 6149.94     360 8065.8923883.86     360
Permanent Ineff=
       F       F
#Block Obstruct= 1 ,-1
14499.6916528.76  323.75
Bank Sta=6398.52,6682.71
XS Rating Curve= 0 ,0
Exp/Cntr=0.3,0.1

Type RM Length L Ch R = 1 ,46568   ,1363.21,1495.23,2484.31
BEGIN DESCRIPTION:
LOB - Kaufman LID1/Henderson LID1, ROB - Ellis LID2
END DESCRIPTION:
XS GIS Cut Line= 4
  2599838.304108 6851059.0992941 2595879.8405669 6845507.4499885
 2594848.5905669 6844057.4499885 2585296.6374419 6834461.8770718
#Sta/Elev= 30
       0  372.21 1692.95  323.63 6656.27  330.49 6818.38   344.6 6877.16  326.62
 7069.87   330.2 7207.75     293 7341.88  329.63 8528.83  319.52 8587.94  344.22
 8797.84  313.9211060.18  326.4411796.41  334.4112076.85  306.3513037.44  308.31
13093.66  325.9913555.12  308.4313679.19  331.3513877.93  312.3414203.31  328.33
14243.51  312.3814341.71  351.1414397.55  324.2315206.15  320.9817741.27  318.06
18943.17  325.9121048.57  327.0321576.53  340.8221947.04  395.3622137.24  394.58
#Mann= 12 ,-1 , 0
       0     .06       0 1692.95     .05       0 6656.27     .09       0
 6818.38     .09       0 7069.87    .055       0 7341.88     .15       0
 8797.84     .05       011060.18     .06       015206.15     .05       0
17741.27     .06       018943.17     .05       021048.57     .06       0
Levee=-1,6818.38,344.6,-1,8587.94,344.22,,
#XS Ineff= 2 ,-1
       0 6818.81     360 8588.0422137.24     360
Permanent Ineff=
       F       F
#Block Obstruct= 1 ,-1
11801.95 14322.2  324.82
Bank Sta=7069.87,7341.88
XS Rating Curve= 0 ,0
Exp/Cntr=0.5,0.3

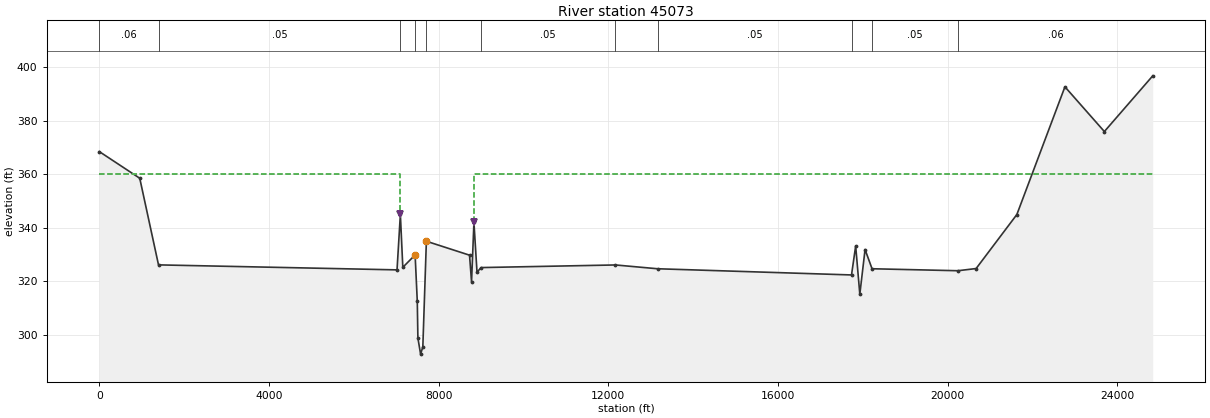
Type RM Length L Ch R = 1 ,45073   ,345.39,280.26,285.37
BEGIN DESCRIPTION:
US Bridge
LOB - Kaufman LID1/Henderson LID1, ROB - Ellis LID2
END DESCRIPTION:
XS GIS Cut Line= 6
  2600926.770416 6850712.1886244 2597846.9093053 6846038.5775133
 2596030.9370831 6842936.1469578 2593793.0898608 6839338.9247355
 2587239.1402081 6832884.5844578  2585513.575972 6831516.0080689
#Sta/Elev= 30
       0  368.47  952.76   358.5 1395.06  326.08 7018.46  324.21 7097.09  344.94
 7154.81  325.17 7444.93  329.81 7496.13  312.38 7510.31   298.7 7574.28  292.68
 7626.64  295.39 7710.21  334.93 8727.83  329.71 8775.26  319.72 8831.57  341.99
 8904.04  323.35 9000.28  325.0712167.55  326.0513159.35  324.6317733.49  322.31
17831.35  333.1517929.29   315.118052.72  331.8318217.56  324.63 20241.9  323.89
20671.26  324.7121631.78  344.9322764.77  392.7223694.75  375.9824835.29  396.83
#Mann= 11 ,-1 , 0
       0     .06       0 1395.06     .05       0 7097.09     .09       0
 7444.93    .055       0 7710.21     .15       0 9000.28     .05       0
12167.55     .06       013159.35     .05       017733.49     .06       0
18217.56     .05       0 20241.9     .06       0
Levee=-1,7097.09,344.94,-1,8831.57,341.99,,
#XS Ineff= 2 ,-1
       0 7096.81     360 8831.5824835.29     360
Permanent Ineff=
       F       F
Bank Sta=7444.93,7710.21
XS Rating Curve= 0 ,0
Exp/Cntr=0.5,0.3