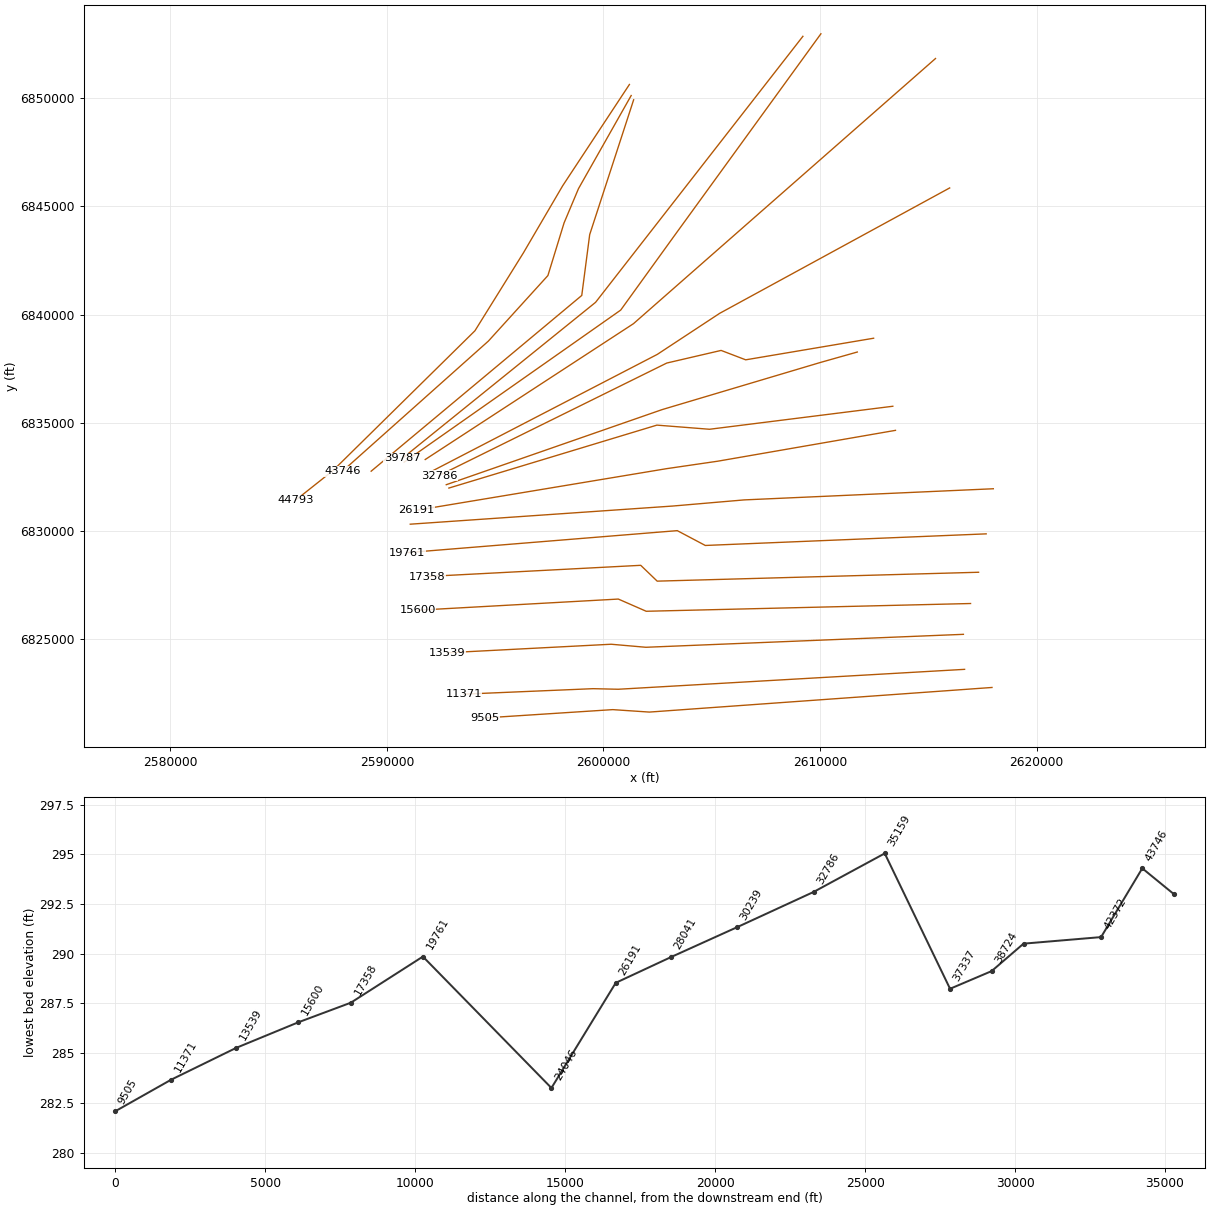
HEC-RAS study TR_FEMA.prj: Trinity_River_FEMA

--- TR_FEMA.g08 (geometry) --- (continued)

Type RM Length L Ch R = 4 ,44923   ,,,
BEGIN DESCRIPTION:
Texas State Highway 34 - Bridge geometry per Compass survey dated July 2018.  Road deck supplemented with Lidar data outside of the surveyed bridge/culvert openings.
END DESCRIPTION:
Node Name=Texas State High
Bridge Culvert--1,0,-1,-1, 0
Deck Dist Width WeirC Skew NumUp NumDn MinLoCord MaxHiCord MaxSubmerge Is_Ogee
126,45,2.6,0, 402, 484, , , 0.98, 0, 0,0,,
       0   24.93   89.75  159.55  199.44  244.31  289.18  309.13     354  378.93
  398.88  413.83  433.78  468.68  473.66  498.59  523.52  558.43  618.26   638.2
  658.14  693.05  703.02  772.82  782.79  862.57  882.51  902.46  917.41  947.33
  972.26 1002.18 1022.12 1032.09 1081.95 1096.91 1126.82 1161.73  1171.7 1181.67
 1211.59 1221.56 1251.47 1306.32 1321.28 1336.24 1351.19 1367.94 1400.02 1434.64
 1440.96 1465.89 1495.81 1510.77 1610.51 1645.42 1730.19 1795.02 1869.82 1929.66
 2193.76 2248.53 2268.45 2318.24 2353.09 2368.03 2437.73 2457.65  2492.5 2537.31
  2587.1    2612  2681.7 2716.56 2761.37 2806.28 2896.25 2926.24 3011.22 3116.19
 3176.17 3231.15 3301.13 3326.12 3371.11 3471.08 3501.07 3640.47 3660.35 3794.51
 3948.55 3963.46 3983.33 4018.11 4082.71 4152.48 4232.37  4292.3 4412.15  4452.1
 4536.99 4596.76 4646.32 4715.71 4755.35 4805.13 4835.02 4889.83 4894.81 4959.58
 5029.33 5069.19 5133.97  5208.7 5268.49 5283.44 5338.25 5363.16 5403.02 5432.91
 5597.33 5647.12    5677 5706.87 5766.62 5806.45 5875.98 5944.43 5978.66 6042.28
 6096.13 6145.08 6174.45 6204.35 6254.19 6304.03 6353.87 6358.85 6403.71 6538.27
 6588.22 6673.14 6708.11 6753.07 6798.03 6823.01 6882.96 6904.946905.6846915.504
6933.3446934.9047570.1047605.194 8831.579028.2949033.5649048.0249058.8749058.966
 9084.28 9124.13 9149.04 9188.89 9263.74 9273.72 9313.64 9398.47 9463.32  9543.1
  9617.9 9707.65  9762.5 9787.43 9822.33 9832.31 9887.16 9922.0610076.3610111.19
10848.8710893.7610918.7111198.0511732.2713427.5413482.06 13556.413586.1313615.87
 13635.713714.99 13724.913774.4613789.3313819.1513859.0314013.5414038.4714068.37
14098.2814118.2214153.1114297.6514357.4714387.3714437.2214526.9414576.7814631.61
 14696.414716.3414771.1714826.05   1496115020.9815115.9415140.9315185.9115235.89
15325.8615410.8215435.8115500.7915520.7815545.7715565.7615615.7415845.3415887.27
15932.07 15990.616110.5516190.5216255.4916300.4816340.4616465.4116565.3716660.34
16700.32 16745.316785.2916880.2516910.2416975.2117025.1917083.1317140.3817175.93
17230.11 17270.117315.0817350.0717405.0417455.03   1751517544.9917579.9817659.95
17744.91 17779.917794.8917799.8917817.2317834.3617842.6517963.0218108.95   18118
18124.5718174.7418224.5718259.3818309.1118338.9418353.8618388.6718423.4818483.15
18532.8818627.36   1869218806.3718871.0218920.8818980.8819030.8819100.8819135.88
19195.8819235.8819290.8819305.8819357.2319394.5619443.13 19450.819470.7819500.75
 19540.719590.6419610.6219650.5719740.4619835.3519855.3319904.63 19936.219957.19
 19965.219995.1720025.1320110.0320144.9920149.9820184.9420209.9120284.7620301.79
20329.44 20362.220409.47 20479.320559.12   2060920628.9520688.8120753.6620808.53
20858.4120898.3220938.2321052.9621107.8321132.7721202.6121277.4321357.2421431.81
21511.2821536.1121595.7121640.4121700.0221729.8221764.5821814.2521863.9221883.79
21973.1922042.7222067.5622107.2922141.8522161.5822255.28   2227522299.6622383.92
22433.7122548.2122617.9122662.3722686.9722731.2522809.9622849.3222878.8422923.19
22977.5423017.0723081.31 23145.823190.5223220.33 23319.723369.3923443.9223498.58
23563.1723602.92 23717.223766.8923831.4823861.3423946.0123980.8824030.6824105.39
24165.1524209.9824249.8224314.5724399.2324404.2124503.8224563.3424652.4324721.71
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         345.107 349.094 348.977 344.257 344.257
                                                 335.467 334.159 333.371
       0   24.93   89.75  154.56  159.55  189.47  199.44  244.31  289.18  309.13
   319.1     354  368.96  378.93  398.88  413.83  433.78  468.68  473.66  498.59
  523.52  558.43  618.26   638.2  658.14  693.05  703.02  772.82  782.79  862.57
  867.55  882.51  902.46  917.41  947.33  972.26 1002.18 1022.12 1032.09 1081.95
 1096.91 1126.82 1161.73  1171.7 1181.67 1211.59 1221.56 1251.47 1306.32 1321.28
 1336.24 1351.19 1367.94 1400.02 1434.64 1440.96 1465.89 1485.84 1495.81 1510.77
 1570.61 1605.52 1610.51 1640.43 1645.42 1700.27 1730.19 1795.02 1809.98 1869.82
 1894.76 1929.66 1959.58 1989.51 2039.37  2089.2 2109.12 2153.93 2168.87 2193.76
 2203.72 2248.53 2268.45 2318.24 2353.09 2368.03 2387.94 2437.73 2447.69 2457.65
 2487.52  2492.5 2522.38 2537.31 2557.23  2587.1    2612 2641.87  2681.7  2706.6
 2716.56 2761.37 2786.28 2806.28 2896.25 2926.24 3011.22 3116.19 3176.17 3231.15
 3301.13 3326.12 3371.11 3471.08 3501.07 3640.47 3660.35 3794.51 3948.55 3963.46
 3983.33 4018.11 4082.71 4152.48 4232.37  4292.3 4412.15  4452.1 4536.99 4596.76
 4646.32 4715.71 4755.35 4805.13 4835.02 4889.83 4894.81 4959.58 5029.33 5069.19
 5133.97  5208.7 5268.49 5283.44 5338.25 5363.16 5403.02 5432.91 5597.33 5647.12
    5677 5706.87 5766.62 5806.45 5875.98 5944.43 5978.66 6042.28 6096.13 6145.08
 6174.45 6204.35 6254.19 6304.03 6353.87 6358.85 6403.71 6538.27 6588.22 6673.14
 6708.11 6753.07 6798.03 6823.01 6882.96 6904.946905.6846915.5046933.3446934.904
7570.1047605.1949028.2949033.5649048.0249058.8749058.966 9084.28 9124.13 9149.04
 9188.89 9263.74 9273.72 9313.64 9398.47 9463.32  9543.1  9617.9 9707.65  9762.5
 9787.43 9822.33 9832.31 9887.16 9922.0610001.72 10026.610076.3610111.1910160.94
10220.6510305.2410384.9610424.8710454.7910499.6910524.6310549.5710609.4310659.31
10679.2710764.0710779.0310848.8710873.8110893.7610918.7110953.6210968.5911013.48
11083.3211198.0511227.98 11342.811467.6311497.5911567.4911632.4111647.3811732.27
11792.1911887.0611966.9512026.8712111.7512151.6912241.5612416.2212441.1712585.89
 12630.812715.63 12780.512855.3612920.2313005.0713109.8613169.5713204.2913243.98
13268.7913348.1613427.5413437.4513482.0613516.75 13556.413586.1313615.87 13635.7
13714.99 13724.913774.4613789.3313819.1513859.0314013.5414038.4714068.3714098.28
14118.2214153.1114297.6514357.4714387.3714437.2214526.9414576.7814631.61 14696.4
14716.3414771.1714826.05   1496115020.9815115.9415140.9315185.9115235.8915325.86
15410.8215435.8115500.7915520.7815535.7815545.7715565.7615615.7415845.3415887.27
15932.07 15990.616110.5516190.5216255.4916300.4816340.4616465.4116565.3716660.34
16700.32 16745.316785.2916880.2516910.2416975.2117025.1917083.1317140.3817175.93
17230.11 17270.117315.0817350.0717405.0417455.03   1751517544.9917579.9817659.95
17744.91 17779.917794.8917799.8917817.2317835.6717842.6517949.5518109.7818118.64
18124.5718174.7418224.5718259.3818309.1118338.9418353.8618388.6718423.4818483.15
18532.8818627.36   1869218806.3718871.0218920.8818980.8819030.8819100.8819135.88
19195.8819235.8819290.8819305.8819357.2319394.5619443.13 19450.819470.7819500.75
 19540.719590.6419610.6219650.5719740.4619835.3519855.3319904.63 19936.219957.19
 19965.219995.1720025.1320110.0320144.9920149.9820184.9420209.9120284.7620301.79
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                                                                         345.107
 349.094 348.977 344.257
                                                 335.425 334.247 333.384
Pier Skew, UpSta & Num, DnSta & Num=  ,7058, 2 ,7058, 2 , 0 , 0 , 0 ,,
       3       3
  292.38 349.094
       3       3
  292.38 349.094
Pier Skew, UpSta & Num, DnSta & Num=  ,7181.2, 2 ,7181.2, 2 , 0 , 0 , 0 ,,
       3       3
  292.38 349.094
       3       3
  292.38 349.094
Pier Skew, UpSta & Num, DnSta & Num=  ,7304.3, 2 ,7304.3, 2 , 0 , 0 , 0 ,,
       3       3
  292.38 349.094
       3       3
  292.38 349.094
Pier Skew, UpSta & Num, DnSta & Num=  ,7427.5, 2 ,7427.5, 2 , 0 , 0 , 0 ,,
       3       3
  292.38 349.094
       3       3
  292.38 349.094
Pier Skew, UpSta & Num, DnSta & Num=  ,7550.6, 2 ,7550.6, 2 , 0 , 0 , 0 ,,
       3       3
  292.38 349.094
       3       3
  292.38 349.094
Pier Skew, UpSta & Num, DnSta & Num=  ,7673.7, 2 ,7673.7, 2 , 0 , 0 , 0 ,,
       3       3
  292.38 349.094
       3       3
  292.38 349.094
Pier Skew, UpSta & Num, DnSta & Num=  ,7796.9, 2 ,7796.9, 2 , 0 , 0 , 0 ,,
       3       3
  292.38 349.094
       3       3
  292.38 349.094
Pier Skew, UpSta & Num, DnSta & Num=  ,7920, 2 ,7920, 2 , 0 , 0 , 0 ,,
       3       3
  292.38 349.094
       3       3
  292.38 349.094
Pier Skew, UpSta & Num, DnSta & Num=  ,8043.2, 2 ,8043.2, 2 , 0 , 0 , 0 ,,
       3       3
  292.38 349.094
       3       3
  292.38 349.094
Pier Skew, UpSta & Num, DnSta & Num=  ,8166.3, 2 ,8166.3, 2 , 0 , 0 , 0 ,,
       3       3
  292.38 349.094
       3       3
  292.38 349.094
Pier Skew, UpSta & Num, DnSta & Num=  ,8289.4, 2 ,8289.4, 2 , 0 , 0 , 0 ,,
       3       3
  292.38 349.094
       3       3
  292.38 349.094
Pier Skew, UpSta & Num, DnSta & Num=  ,8412.6, 2 ,8412.6, 2 , 0 , 0 , 0 ,,
       3       3
  292.38 349.094
       3       3
  292.38 349.094
Pier Skew, UpSta & Num, DnSta & Num=  ,8535.7, 2 ,8535.7, 2 , 0 , 0 , 0 ,,
       3       3
  292.38 349.094
       3       3
  292.38 349.094
Pier Skew, UpSta & Num, DnSta & Num=  ,8658.9, 2 ,8658.9, 2 , 0 , 0 , 0 ,,
       3       3
  292.38 349.094
       3       3
  292.38 349.094
Pier Skew, UpSta & Num, DnSta & Num=  ,8782, 2 ,8782, 2 , 0 , 0 , 0 ,,
       3       3
  292.38 349.094
       3       3
  292.38 349.094
Pier Skew, UpSta & Num, DnSta & Num=  ,8905.1, 2 ,8905.1, 2 , 0 , 0 , 0 ,,
       3       3
  292.38 349.094
       3       3
  292.38 349.094
Pier Skew, UpSta & Num, DnSta & Num=  ,17871.72, 2 ,17872.22, 2 , 0 , 0 , 0 ,,
       2       2
  314.53 349.094
       2       2
  314.83 349.094
Pier Skew, UpSta & Num, DnSta & Num=  ,17911.15, 2 ,17912.01, 2 , 0 , 0 , 0 ,,
       2       2
  314.53 349.094
       2       2
  314.83 349.094
Pier Skew, UpSta & Num, DnSta & Num=  ,17950.67, 2 ,17951.54, 2 , 0 , 0 , 0 ,,
       2       2
  314.53 349.094
       2       2
  314.83 349.094
Pier Skew, UpSta & Num, DnSta & Num=  ,17990.4, 2 ,17990.73, 2 , 0 , 0 , 0 ,,
       2       2
  314.53 349.094
       2       2
  314.83 349.094
Pier Skew, UpSta & Num, DnSta & Num=  ,18030.49, 2 ,18030.41, 2 , 0 , 0 , 0 ,,
       2       2
  314.53 349.094
       2       2
  314.83 349.094
Pier Skew, UpSta & Num, DnSta & Num=  ,18070.28, 2 ,18070.27, 2 , 0 , 0 , 0 ,,
       2       2
  314.53 349.094
       2       2
  314.83 349.094
Abutment Skew #Up #Dn= , 2 , 2
  6934.9 6967.85
  345.11 333.949
  6934.9 6967.85
  345.11 333.949
Abutment Skew #Up #Dn= , 2 , 2
 8997.82 9028.29
 329.705  344.26
 8997.82 9028.29
 329.705  344.26
BR Coef= 1 , 1 , 1 ,0.95, 0 ,,,0.8,-1,1.2,0,
WSPro=,,,, 1 ,,,, 0 ,,,, 0 ,,,,-1 ,-1 ,-1 , 0 , 0 , 0 , 0 , 0
Multiple Barrel Culv=2,6,6,49.25,0.12,0.4,1,8,1,321.88,321.62, 3,Culvert #1  , 0 ,127.32
 1389.38  1389.7 1396.07 1396.24  1402.7 1402.84
BC Culvert Barrel=1,Barrel #1,0
BC Culvert Barrel=2,Barrel #2,0
BC Culvert Barrel=3,Barrel #3,0
Culvert Bottom n=0.12
Multiple Barrel Culv=2,8,10,69.3,0.12,0.4,1,8,1,317.21,317.35, 4,Culvert #2  , 0 ,102.1
15872.79 15872.915883.4615883.5315894.1815894.2315904.9715904.97
BC Culvert Barrel=1,Barrel #1,0
BC Culvert Barrel=2,Barrel #2,0
BC Culvert Barrel=3,Barrel #3,0
BC Culvert Barrel=4,Barrel #4,0
Culvert Bottom n=0.12
Culvert=2,8,10,65.1,0.12,0.4,1,8,1,317.82,17140.94,318.33,17141.22,Culvert #3  , 0 ,111.57
17140.9417141.22
BC Culvert Barrel=1,Barrel #1,0
Culvert Bottom n=0.12
Culvert=2,10,10,91,0.12,0.4,1,8,1,319.47,18223.95,319.08,18223.95,Culvert #4  , 0 ,102.93
18223.9518223.95
BC Culvert Barrel=1,Barrel #1,0
Culvert Bottom n=0.12
Multiple Barrel Culv=2,10,10,73.2,0.12,0.4,1,8,1,317.48,317.72, 4,Culvert #5  , 0 ,110.34
19387.0319387.3119397.6419398.1319408.4119408.9119419.0719419.32
BC Culvert Barrel=1,Barrel #1,0
BC Culvert Barrel=2,Barrel #2,0
BC Culvert Barrel=3,Barrel #3,0
BC Culvert Barrel=4,Barrel #4,0
Culvert Bottom n=0.12
Culvert=2,8,10,84.4,0.12,0.4,1,8,1,317.11,19936.69,317.95,19936.63,Culvert #6  , 0 ,102.38
19936.6919936.63
BC Culvert Barrel=1,Barrel #1,0
Culvert Bottom n=0.12
Culvert=2,7,10,84.6,0.12,0.4,1,8,1,318.52,20336.72,320.55,20336.72,Culvert #7  , 0 ,97.79
20336.7220336.72
BC Culvert Barrel=1,Barrel #1,0
Culvert Bottom n=0.12
BC Mult= 1 ,0,1000,0,1245.78
BC Mult= 2 ,1000,6600,1245.78,6600
BC Mult= 3 ,1550,15500,1550,15500
BC Mult= 2 ,9500,17600,9500,17700
BC Mult= 3 ,17300,18201,17400,18201
BC Mult= 2 ,18150,21160.79,18142,20949.85
BC Mult= 1 ,21160.79,24835.29,20949.85,24835.2
BR U #Sta/Elev= 472
       0  368.47   56.37  368.05  179.85  367.59  233.33  367.99   272.7  368.44
  349.78  368.17  392.53  368.29  456.85  366.95  584.64  362.36  675.22  361.11
  830.66  360.25  876.94  359.71  952.76   358.5  970.39  356.79   991.7  353.45
  1009.5   352.2 1044.64  348.18  1070.7  347.05 1095.59   344.6 1164.94   341.8
 1198.02   338.1 1225.13   333.7 1245.78  332.06 1314.15  329.071379.562 325.957
 1386.38  321.88 1392.38  321.88 1393.07  321.88 1399.22  321.88  1399.8  321.88
  1405.7  321.881409.227 325.8411419.115 325.5851433.947 323.4251438.891 323.526
1443.836 323.536 1448.78 323.3281453.724  323.561483.388 324.6471508.109 325.019
1537.774 325.0661611.935     326 1633.37  326.35 1714.46  325.72 1744.44  324.88
  1855.8  324.99  1905.1   325.3  1969.5 325.2852014.235 325.2622039.087 325.423
2078.851 325.4992113.645 325.3892133.527 325.6472153.409 326.5932183.232 324.896
2203.115 325.5632218.026 325.8182227.967 326.424 2252.82  326.63 2274.36  326.34
  2314.4     326 2358.22  325.84 2488.21  326.23 2513.43  326.69 2593.12  326.29
  2648.1  326.22 2771.36   326.3 2819.29  326.35 2900.93  326.68 2930.74  326.11
 3075.08   326.6 3113.72  326.31 3245.47   326.6 3281.81  326.84 3539.96  326.29
 3613.81  326.65 3703.93  326.59 3731.74  326.84 3794.33   326.6 3837.71  326.87
 3883.41  326.66  3978.5   326.7 4028.31  327.27 4064.65  327.14 4211.34  327.24
 4246.68  327.51 4295.74  327.16 4395.08  327.63 4430.41  327.07 4485.44  327.45
 4516.63  327.15 4587.46  327.53 4638.49  327.46 4720.65  327.78 4837.88  327.85
 4944.52  327.44 4997.02  327.69 5072.65   327.5  5125.3  327.41    5192  327.91
 5342.82  327.89 5434.43  328.17 5525.89  327.89 5705.57  328.33 5743.04  327.99
 5797.67  328.37 5896.09  328.34    6101  328.63 6403.68  331.86 6967.85  333.95
 6982.85  324.55 7002.77  324.35 7018.46  324.21 7026.83  328.14 7055.48  331.97
 7068.87  339.39 7080.21  343.94 7097.09  344.94 7102.06  344.17 7125.91  333.36
 7137.54  331.83 7154.81  325.17 7170.31  324.54 7187.87  330.25 7227.03  331.31
 7306.01     332 7363.01   332.3 7411.83  331.83 7444.93  329.81 7463.46  324.49
 7476.73  316.58 7496.13  312.38 7501.77  308.897510.308 298.7027526.238 295.017
7529.681 294.2437570.369 293.878  7573.8 292.4417583.605 293.8577617.125 294.309
7626.643 295.3877629.889 296.7787632.934 298.271 7647.83  302.66 7654.69   308.3
 7665.33  312.44 7677.81  317.28 7691.53  320.31 7700.34     326 7710.21  334.93
 7802.62  335.47  7887.7  334.03  7919.3  332.82  8015.8  330.68  8070.8  330.72
 8135.93  329.87 8227.14  329.78 8280.89  329.85 8357.07   329.8 8408.76  330.04
 8459.26  329.83 8516.77  329.56 8614.58  328.88 8650.03  329.72 8727.83  329.71
 8756.46  319.74 8775.26  319.72 8787.58  328.02 8819.61  340.53 8826.58  341.78
 8831.57  341.99 8843.29  341.13  8858.3  333.76  8866.4  331.65 8889.82  328.24
 8904.04  323.35 8934.59  323.34 8982.02  325.32 8997.82 329.70510101.21  327.49
10150.97  328.24 10225.6  326.1910270.82  326.2510454.32  326.0210553.54  325.96
10630.42  326.1410778.38  325.8110912.92  325.7910994.46  325.8211079.36  325.71
11182.72 326.17811222.49 326.15811232.43 325.99411297.04 325.85311356.69 325.488
11391.48 325.98811421.31 326.03611461.07 325.91711495.87 326.05311520.72 326.317
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BR U #Mann= 12
       0     .061379.562     .05 6967.85      .1 7097.09     .09 7463.46    .055
 7700.34     .15 8997.82     .05 12285.7     .0613159.35     .0517718.48     .06
18215.82     .0520227.46     .06
BR D #Sta/Elev= 446
       0  364.25   31.52  364.85   44.42  364.35   82.85  364.86  120.31  363.72
  138.66  362.46  186.76  361.58  221.93  361.67   253.1  363.33  263.43  362.28
  310.63  362.01  347.14  359.34  378.21  358.55   403.3  358.67  438.85  357.68
  468.02   357.5  521.97  356.05  568.22  355.87  635.35  354.71  641.79  355.42
  703.01  357.03   759.9  357.34  782.28  356.89   868.5  354.25  975.29  347.62
 1003.85  346.21 1071.89  344.04 1144.33  340.59 1160.65     336 1199.43   336.3
 1234.81  336.04 1245.78  337.72 1271.71  332.79 1297.96  329.77 1327.07  328.21
 1358.86  327.94  1386.7 321.617  1392.7 321.617 1393.31 321.617 1399.24 321.617
 1399.84 321.617 1405.84 321.617 1416.01   325.8 1436.19  323.54    1452  323.08
  1481.4   326.1 1515.13  325.32 1589.65  326.11 1600.94  325.49 1658.21  325.67
  1673.9  324.89 1722.24  324.25 1784.36  323.82 1842.65  324.09 1896.08  325.06
 1921.35  325.01 1967.25  325.83 1990.95  325.56 2052.57  326.04 2119.91  325.72
 2131.55  326.18 2232.22  325.68 2302.09  325.99 2351.87  325.43 2396.61  326.01
 2464.56  325.87 2513.14  326.23 2530.73  325.71  2586.4     326 2604.76  325.34
 2631.38  325.88 2668.28  325.72 2685.78  326.31 2714.04  325.83    2727  326.29
 2758.48  325.95 2797.85  326.24 2819.06  325.81 2861.22  326.02 2933.74  325.82
 3052.01  326.27 3086.06  326.08 3171.97  326.36 3200.12  326.12 3254.56  326.36
 3435.91  326.33 3498.96  326.52 3535.33  326.93 3580.49  326.38 3771.85  326.11
 3970.15  326.52 3993.62  326.38    4194  326.85 4240.06  326.75 4304.44  327.09
  4415.2  326.88 4571.44   326.8 4650.01  327.19 4731.47  326.97 4898.15   327.3
 4913.68  327.53 5051.97  327.24 5123.92  326.91  5181.7  327.11 5260.65  327.39
 5346.02  327.98 5412.55  328.34 5560.39   328.1 5710.36  328.18 5817.61  328.23
 5896.53  328.64 5905.29   329.4  5998.2  330.49 6056.94  330.19 6145.05  331.13
 6967.85  333.95 6981.79  329.71 7014.47  328.43 7028.47  327.24 7049.59  323.55
 7068.61  323.67 7075.88  327.24 7090.26  331.22 7106.87  332.02 7129.65  343.21
 7141.11  345.37 7152.22  344.79  7169.6  336.91 7191.87  330.76 7205.66  324.75
 7213.76  323.88 7224.98  324.98 7242.21   330.9 7249.11  331.61 7277.89  331.11
 7332.82  332.44  7367.1  331.45 7382.29  331.81 7454.74   329.9 7466.32  326.88
 7486.92   328.6  7493.5  326.16 7518.62   322.1 7541.57  316.61 7550.53  312.63
    7557  313.887568.412 296.3077571.809 295.6587574.958 294.7017591.083 293.107
7597.525 292.675 7600.77 293.0077668.617 293.7157689.232 294.178 7718.76   294.7
 7725.62  296.26 7728.52  301.76 7741.74  305.17 7756.79  311.75 7768.74  319.68
  7781.3  329.62 7783.39   336.4 7816.03  334.76  7838.8  335.19 7915.72  334.61
 7943.77  332.92 7968.75  332.63 7990.25  333.15 8113.08  331.08 8189.97  330.58
 8212.59  329.79 8234.37  324.52 8275.04  321.06 8296.89  320.94 8309.86   319.9
 8333.84  319.61 8362.17  320.44 8405.62  320.44 8433.98   321.1 8484.88  320.63
 8510.37  319.36  8534.2  319.46 8591.83  326.61 8593.52  327.35 8637.48  329.16
 8669.41  328.68 8693.81  329.65 8744.54  329.03 8778.64  329.86 8815.25   324.9
 8850.12  335.59 8894.95  343.04 8914.88  341.68 8939.79  333.43 8974.66  325.32
 8997.82 329.705 9927.01  329.08 9998.88  326.6510157.53  326.57 10243.1  326.14
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BR D #Mann= 8
       0     .06 1436.19     .05 6981.79      .1 7141.11     .09 7486.92    .055
  7781.3     .09 8997.82     .0520471.14     .06
BC Design=,, 0 ,, 0 ,,,,,,
BC Use User HTab Curves=0
BC User HTab FreeFlow(D)= 0

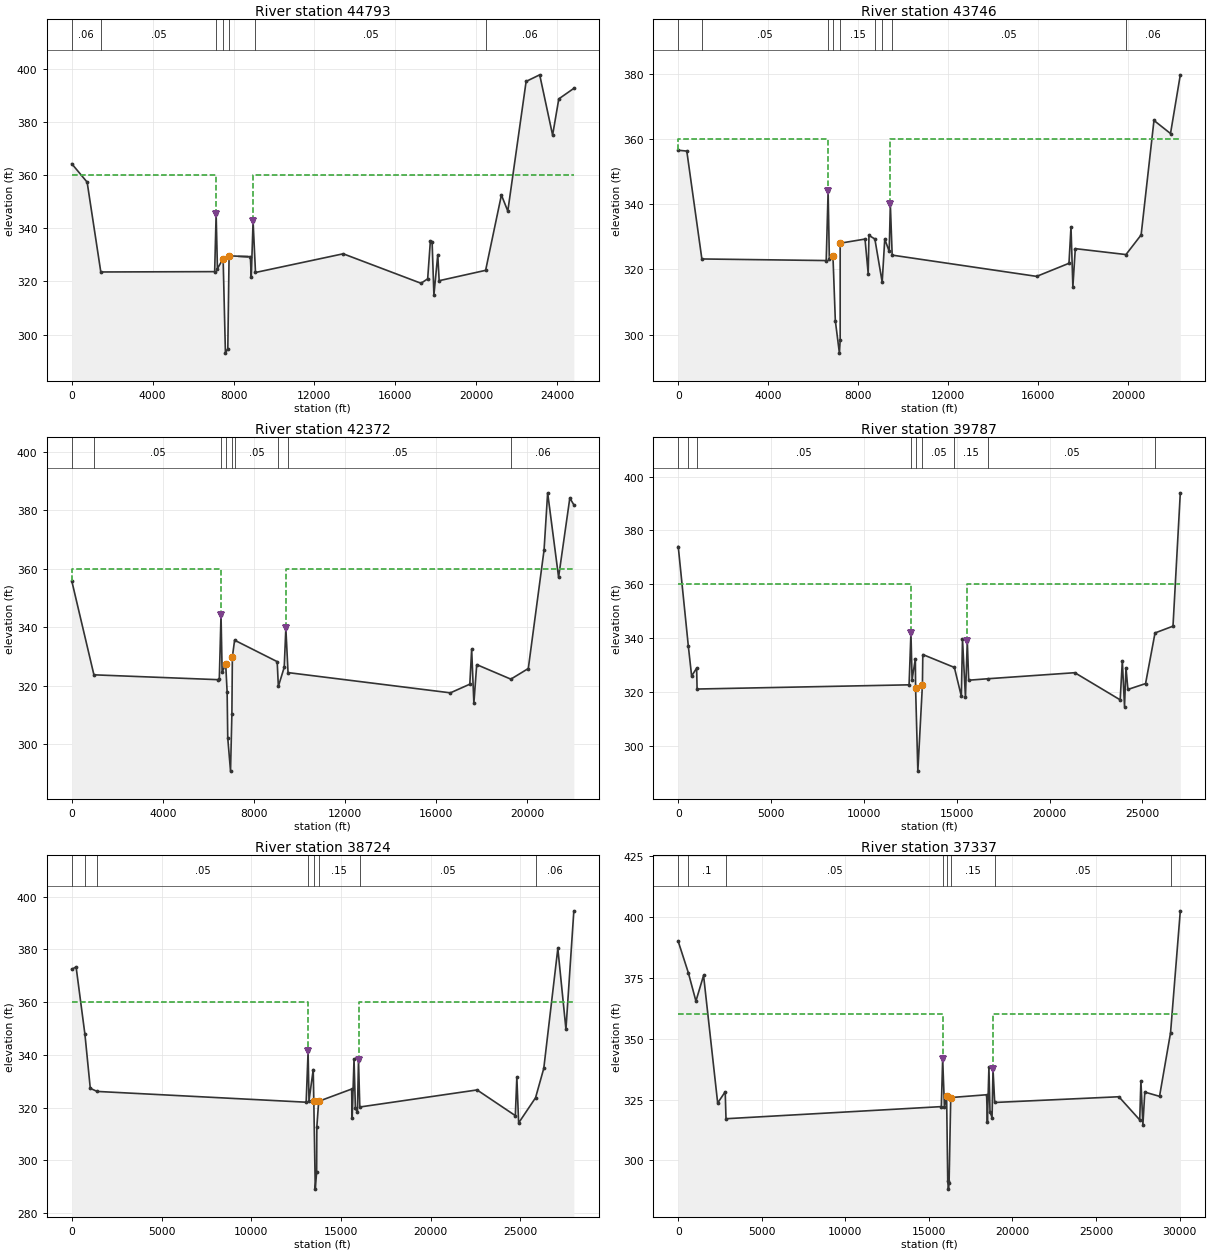
Type RM Length L Ch R = 1 ,44793   ,681.19,1046.32,1063.06
BEGIN DESCRIPTION:
DS Bridge
LOB - Kaufman LID1/Henderson LID1, ROB - Ellis LID2
END DESCRIPTION:
XS GIS Cut Line= 6
   2601201.10032 6850624.5597711 2598121.2392092 6845950.9486599
  2596305.266987 6842848.5181044 2594067.4197648 6839251.2958822
  2587513.470112 6832796.9556044 2585787.9058759 6831428.3792155
#Sta/Elev= 30
       0  364.25   759.9  357.34 1436.19  323.54 7068.61  323.67 7141.11  345.37
 7205.66  324.75 7486.92   328.6 7600.77  293.01 7718.76   294.7  7781.3  329.62
    8834  329.28 8879.09  321.72 8968.54  342.65 9087.95  323.3513426.66  330.38
17275.59  319.2917604.55  320.9617738.86  335.2717824.38  334.8817912.77  314.86
 18104.1  330.0518172.89  320.2620471.14  324.1621252.55  352.49 21568.6  346.44
22474.59  395.2323146.12  397.71 23784.5  375.0324091.36  388.66 24835.2  392.62
#Mann= 7 ,-1 , 0
       0     .06       0 1436.19     .05       0 7141.11     .09       0
 7486.92    .055       0  7781.3     .09       0 9087.95     .05       0
20471.14     .06       0
Levee=-1,7141.11,345.37,-1,8968.54,342.65,,
#XS Ineff= 2 ,-1
       0 7141.96     360 8968.42 24835.2     360
Permanent Ineff=
       F       F
#Block Obstruct= 1 ,-1
 8212.59 8693.81  329.65
Bank Sta=7486.92,7781.3
XS Rating Curve= 0 ,0
Exp/Cntr=0.5,0.3

Type RM Length L Ch R = 1 ,43746   ,782.09,1374.19,1573.74
BEGIN DESCRIPTION:
LOB - Kaufman LID1/Henderson LID1, ROB - Ellis LID2
END DESCRIPTION:
XS GIS Cut Line= 6
   2601283.10594 6850114.9713198 2598849.7726067 6845814.9713198
 2598184.1374419 6844234.0992941 2597436.9152197 6841800.7659607
 2594688.5818863 6838775.3546181 2587952.4707752 6832768.4101737
#Sta/Elev= 30
       0  356.61  380.29  356.35 1050.35  323.22 6576.81  322.73 6661.05  343.98
 6716.36  323.28  6875.8  324.22 6981.87  304.26 7163.12   294.3 7197.19  298.26
 7197.37  328.06 8301.69  329.33 8441.93  318.73 8476.98  330.45  8738.5  329.36
 9064.25  316.11 9178.61  329.34 9376.07  325.53 9426.74  340.03 9508.31   324.4
15930.02  317.8717366.23  321.8917455.67  333.0817539.51  314.6417646.76  326.39
19899.45  324.5720572.74   330.6 21143.6  365.7621878.84  361.7422314.38  379.77
#Mann= 9 ,-1 , 0
       0     .06       0 1050.35     .05       0 6661.05     .15       0
  6875.8    .055       0 7197.37     .15       0  8738.5     .05       0
 9064.25     .15       0 9508.31     .05       019899.45     .06       0
Levee=-1,6661.05,343.98,-1,9426.74,340.03,,
#XS Ineff= 2 ,-1
       0 6660.86     360 9426.7622314.38     360
Permanent Ineff=
       F       F
Bank Sta=6875.8,7197.37
XS Rating Curve= 0 ,0
Exp/Cntr=0.3,0.1

Type RM Length L Ch R = 1 ,42372   ,3867.9,2585.3,725.77
BEGIN DESCRIPTION:
LOB - Kaufman LID1/Henderson LID1, ROB - Ellis LID2
END DESCRIPTION:
XS GIS Cut Line= 4
  2601396.573784 6849917.6173496 2599366.7616801 6843692.2464785
 2599000.7404511 6840882.8951274 2589275.7404511 6832767.6173496
#Sta/Elev= 30
       0  355.87  972.79  323.77 6428.02  322.11 6478.47  322.31 6553.92  344.26
 6602.77   324.7 6759.83  327.34 6822.67   317.8 6849.05  302.22 6971.62  290.84
 7031.24  310.42 7052.39  329.93  7150.5  335.61 9020.06  328.28 9072.11  319.82
 9329.57  326.35 9400.68  339.72 9496.65  324.5316625.65  317.6117479.32  320.57
17559.79   332.5 17657.4  314.0417781.89  327.26 19280.6  322.2920047.19  325.92
20739.15  366.4420896.72     38621377.12  357.1521870.54  384.2222047.19   381.9
#Mann= 9 ,-1 , 0
       0     .06       0  972.79     .05       0 6553.92     .15       0
 6759.83    .055       0 7052.39     .15       0  7150.5     .05       0
 9072.11     .15       0 9496.65     .05       0 19280.6     .06       0
Levee=-1,6553.92,344.26,-1,9400.68,339.72,,
#XS Ineff= 2 ,-1
       0 6555.25     360 9401.3522047.19     360
Permanent Ineff=
       F       F
Bank Sta=6759.83,7052.39
XS Rating Curve= 0 ,0
Exp/Cntr=0.3,0.1

Type RM Length L Ch R = 1 ,39787   ,892.19,1062.65,1007.03
BEGIN DESCRIPTION:
LOB - Kaufman LID1/Henderson LID1, ROB - Ellis LID2
END DESCRIPTION:
XS GIS Cut Line= 3
  2609212.137262 6852849.0371331 2599638.6514077 6840565.1583585
 2590714.0585588 6833359.5000961
#Sta/Elev= 30
       0  374.03  543.82     337  721.29  325.87  990.94   328.8 1015.82  321.04
 12434.1   322.6   12535  342.0312595.48  324.5712773.05   332.312785.25   321.5
12906.56  290.5113152.72   322.613173.96  333.8714873.87  329.0715249.02  318.38
15311.54  339.5715471.06  317.96   15570  338.8615645.78  324.3216688.86  324.87
21361.63  327.1123805.59  317.01   23921  331.5624038.68  314.5324117.98  328.97
24220.47  320.8825172.64  323.0625681.99  341.8926650.31  344.4227044.21     394
#Mann= 9 ,-1 , 0
       0     .06       0  543.82      .1       0  990.94     .05       0
   12535     .15       012785.25    .055       013152.72     .05       0
14873.87     .15       016688.86     .05       025681.99     .06       0
Levee=-1,12535,342.03,-1,15570,338.86,,
#XS Ineff= 2 ,-1
       012534.75     36015569.0127044.21     360
Permanent Ineff=
       F       F
Bank Sta=12785.25,13152.72
XS Rating Curve= 0 ,0
Exp/Cntr=0.3,0.1

Type RM Length L Ch R = 1 ,38724   ,2589.44,1387.22,926.77
BEGIN DESCRIPTION:
LOB - Kaufman LID1/Henderson LID1, ROB - Ellis LID2
END DESCRIPTION:
XS GIS Cut Line= 4
   2610043.95631 6852965.4574309 2603252.0039816 6843606.0567849
 2600797.9969442 6840205.9265522  2590797.408302 6833183.5301745
#Sta/Elev= 30
       0  372.46  240.88  373.37  733.71  347.78 1031.29  327.36 1406.51  326.17
13061.28  322.0813168.51  341.34 13219.1  322.6713454.97  334.4613486.97   322.7
13568.35  289.13 13644.8  295.6113655.92  312.7313758.43  322.4215596.14  327.07
15625.02  316.0815728.31  338.3415805.02  319.7215917.31  318.2815977.76  338.15
16049.68  320.2622584.53  326.7324717.01  316.9924800.38  331.5824901.51  314.22
25843.56  323.7726302.09  334.9127085.14  380.3727536.79  349.7627977.22  394.63
#Mann= 8 ,-1 , 0
       0     .06       0  733.71      .1       0 1406.51     .05       0
13168.51     .15       013486.97    .055       013758.43     .15       0
16049.68     .05       025843.56     .06       0
Levee=-1,13168.51,341.34,-1,15977.76,338.15,,
#XS Ineff= 2 ,-1
       013169.59     36015979.5627977.22     360
Permanent Ineff=
       F       F
Bank Sta=13486.97,13758.43
XS Rating Curve= 0 ,0
Exp/Cntr=0.3,0.1

Type RM Length L Ch R = 1 ,37337   ,3427.32,2177.73,1690.74
BEGIN DESCRIPTION:
LOB - Kaufman LID1/Henderson LID1, ROB - Ellis LID2
END DESCRIPTION:
XS GIS Cut Line= 3
  2615335.622977 6851823.7907643 2601386.6348669 6839577.7655373
 2591771.9152196 6833306.6046181
#Sta/Elev= 30
       0  389.89  601.66   377.1 1058.46  365.41 1515.82  375.93 2360.04  323.58
 2810.74  328.21 2857.44  317.1315741.77   322.115822.04  341.7515928.32  321.93
16057.47  326.4716125.44  291.57   16168  288.2416205.98  290.8716304.57  325.82
18451.41  326.9718498.33  315.9218589.38   338.218653.98  320.0118776.11  317.58
18835.12  337.37 18934.7   323.826364.29  326.1527613.66  316.6427683.05  332.72
27802.17   314.727916.74  328.0628797.64  326.3229457.16  352.4430040.95  402.45
#Mann= 8 ,-1 , 0
       0     .06       0  601.66      .1       0 2857.44     .05       0
15822.04     .15       016057.47    .055       016304.57     .15       0
 18934.7     .05       029457.16     .06       0
Levee=-1,15822.04,341.75,-1,18835.12,337.37,,
#XS Ineff= 2 ,-1
       015821.49     36018835.9830040.95     360
Permanent Ineff=
       F       F
Bank Sta=16057.47,16304.57
XS Rating Curve= 0 ,0
Exp/Cntr=0.3,0.1

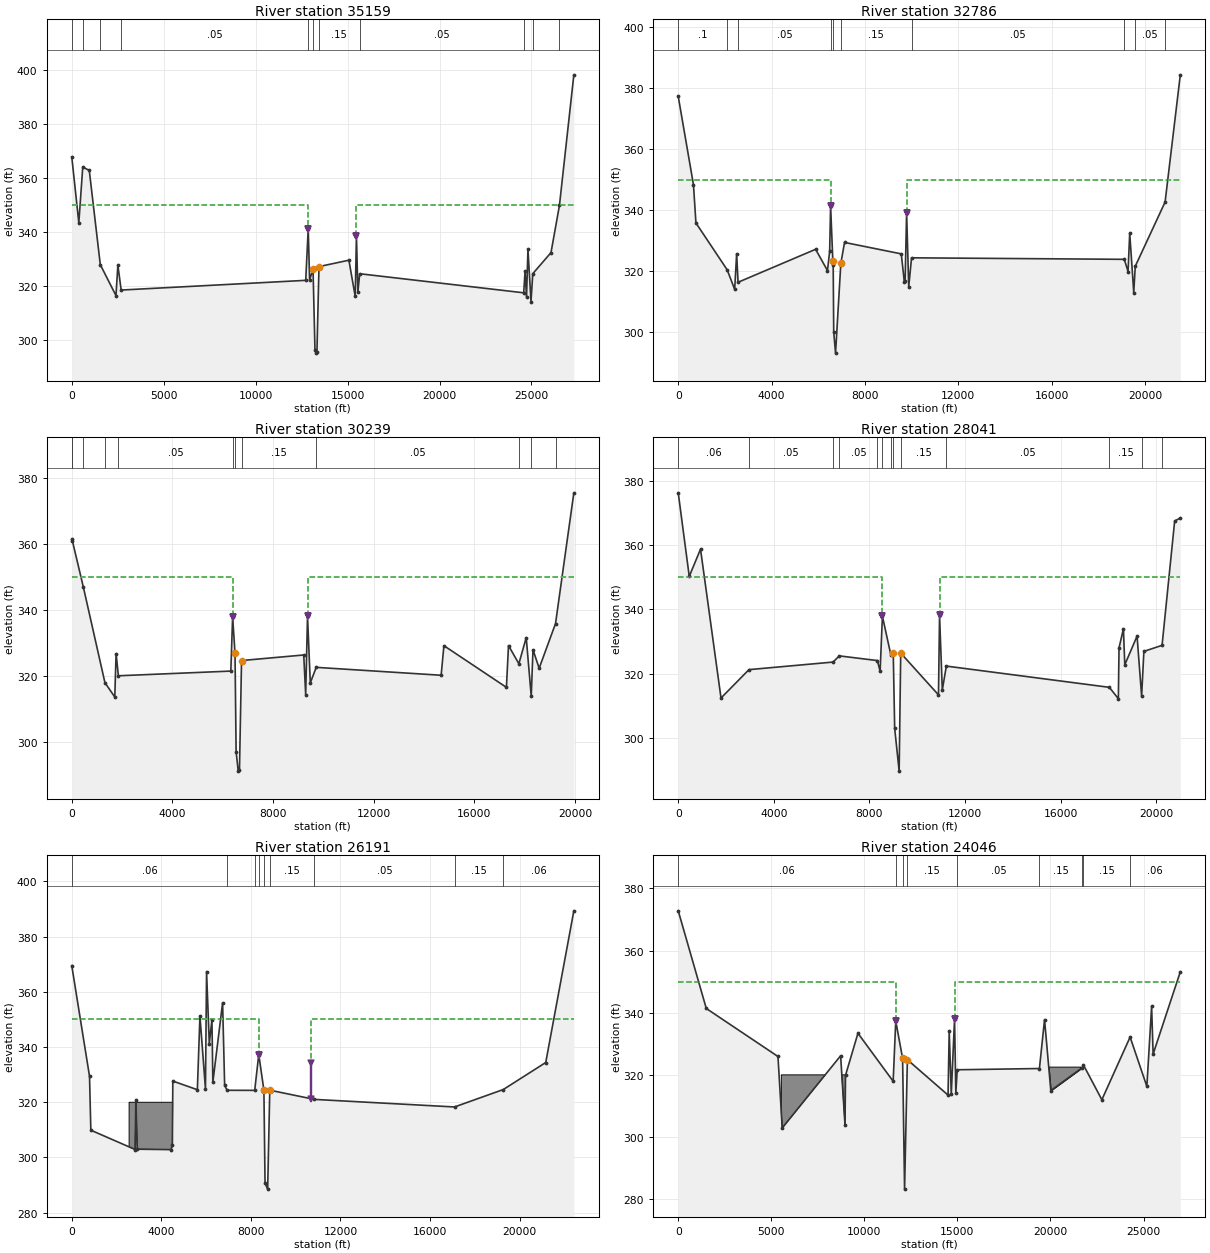
Type RM Length L Ch R = 1 ,35159   ,3333.38,2373.47,517.22
BEGIN DESCRIPTION:
LOB - Kaufman LID1/Henderson LID1, ROB - Ellis LID2
END DESCRIPTION:
XS GIS Cut Line= 4
   2615990.11631 6845847.5727087 2605372.0607548 6840058.6838198
 2602487.6690384 6838160.7157798 2592049.6929974 6832751.0490626
#Sta/Elev= 30
       0  367.84  383.55  343.38   596.9  364.04  951.99  362.81 1551.25  327.86
 2404.04  316.38 2506.63  327.68 2685.93  318.4412722.47  322.0412857.72  341.16
12934.03  322.1713119.58  326.26 13225.6  296.15 13282.3  295.0513332.27  295.53
13443.18  327.1415069.93  329.5115413.88  316.0815480.15  338.6415558.94  317.61
15656.95  324.4924576.89  317.4224649.26  325.3424730.47  315.8624807.06  333.62
24972.62  314.1725070.94  324.5226060.58  332.3326519.65  349.8127302.92  398.25
#Mann= 11 ,-1 , 0
       0      .1       0   596.9     .06       0 1551.25      .1       0
 2685.93     .05       012857.72     .15       013119.58    .055       0
13443.18     .15       015656.95     .05       024576.89     .15       0
25070.94     .05       026519.65     .06       0
Levee=-1,12857.72,341.16,-1,15480.15,338.64,,
#XS Ineff= 2 ,-1
       012857.82     35015480.2127302.92     350
Permanent Ineff=
       F       F
Bank Sta=13119.58,13443.18
XS Rating Curve= 0 ,0
Exp/Cntr=0.3,0.1

Type RM Length L Ch R = 1 ,32786   ,932.09,2546.34,1762.9
BEGIN DESCRIPTION:
LOB - Kaufman LID1/Henderson LID1, ROB - Ellis LID2
END DESCRIPTION:
XS GIS Cut Line= 5
   2612477.24508 6838907.2006829   2606570.87934 6837910.0942014
 2605434.6766815 6838344.2164293 2602926.8978586 6837761.6567014
 2592404.3284141 6832563.4506829
#Sta/Elev= 30
       0  377.24   652.7  348.29  758.57  335.77 2095.92  320.44 2418.58  314.01
  2503.3   325.7 2563.95  316.33 5886.86  327.14 6395.95  320.17 6489.72  326.52
 6529.91  341.49 6625.46  323.35 6640.64  322.08 6663.42  300.01 6742.11  293.11
 6968.26  322.49  7127.6  329.39 9558.81  325.64 9688.36  316.51 9723.16  316.79
 9787.39  339.17 9877.91  314.83 9998.96  324.3519117.69  323.8519277.15  319.85
19348.81   332.419521.83  312.9719586.63  321.5820864.95  342.6221517.27  384.32
#Mann= 10 ,-1 , 0
       0      .1       0 2095.92     .06       0 2563.95     .05       0
 6529.91     .15       0 6625.46    .055       0 6968.26     .15       0
 9998.96     .05       019117.69     .15       019586.63     .05       0
20864.95     .06       0
Levee=-1,6529.91,341.49,-1,9787.39,339.17,,
#XS Ineff= 2 , 0
       0 6530.07     350 9787.44       0     350
Permanent Ineff=
       F       F
Bank Sta=6625.46,6968.26
XS Rating Curve= 0 ,0
Exp/Cntr=0.3,0.1

Type RM Length L Ch R = 1 ,30239   ,2121.82,2198.11,574.75
BEGIN DESCRIPTION:
LOB - Kaufman LID1/Henderson LID1, ROB - Ellis LID2
END DESCRIPTION:
XS GIS Cut Line= 4
  2611724.189525 6838270.3025348 2610022.1061919 6837788.7053126
  2602711.342303  6835611.274757 2592744.1374419 6832143.4101737
#Sta/Elev= 30
       0  361.04    8.18  361.52  462.84  346.92 1317.94  318.09 1708.85  313.77
 1761.26   326.9  1852.1  320.18 6320.15   321.6  6391.5  338.05 6486.82  326.95
 6530.21  297.24 6614.31  291.34 6663.86  291.79 6746.07  324.79 9217.26  326.47
 9294.63  314.49 9367.52  338.23 9478.18  318.03 9713.62  322.7314677.13  320.34
14787.63  329.2917271.11  316.6817353.89  329.3217765.76  323.8218058.24  331.72
18257.43  313.9818326.52  328.0618571.96  322.4519222.44  335.9819950.38  375.52
#Mann= 12 ,-1 , 0
       0      .1       0    8.18     .06       0  462.84      .1       0
 1317.94     .06       0  1852.1     .05       0  6391.5     .15       0
 6486.82    .055       0 6746.07     .15       0 9713.62     .05       0
17765.76     .15       018257.43     .05       019222.44     .06       0
Levee=-1,6391.5,338.05,-1,9367.52,338.23,,
#XS Ineff= 2 , 0
       0 6391.11     350 9367.67       0     350
Permanent Ineff=
       F       F
Bank Sta=6486.82,6746.07
XS Rating Curve= 0 ,0
Exp/Cntr=0.3,0.1

Type RM Length L Ch R = 1 ,28041   ,1424.7,1850.02,1966.69
BEGIN DESCRIPTION:
LOB - Kaufman LID1/Henderson LID1, ROB - Ellis LID2
END DESCRIPTION:
XS GIS Cut Line= 4
   2613364.12008 6835765.9043866  2604898.842303 6834703.4043866
 2602469.6756363 6834894.7238311 2592864.1200808 6831988.1266088
#Sta/Elev= 30
       0  376.19  460.84  350.26  932.26  358.71 1789.54  312.52  2958.9  321.33
  6477.9  323.68 6737.59   325.6 8331.43  324.14 8445.45  320.81 8541.68  337.89
 8891.15  326.02 8995.21  326.45  9054.8  303.11 9241.87  289.84 9307.65  326.47
10887.19   313.510931.68   338.2 11047.2  315.0111215.96  322.4318035.58  315.84
18412.18  312.3118440.22  328.0818624.09  333.9918681.23  322.8419194.99  331.74
19385.52   313.119479.95  326.9920240.48  328.8720767.51  367.4321004.03   368.4
#Mann= 13 ,-1 , 0
       0     .06       0  2958.9     .05       0  6477.9     .06       0
 6737.59     .05       0 8331.43     .06       0 8541.68     .06       0
 8891.15     .15       0 8995.21    .055       0 9307.65     .15       0
11215.96     .05       018035.58     .15       019385.52     .05       0
20240.48     .06       0
Levee=-1,8541.68,337.89,-1,10931.68,338.2,,
#XS Ineff= 2 , 0
       0 8540.92     35010931.05       0     350
Permanent Ineff=
       F       F
Bank Sta=8995.21,9307.65
XS Rating Curve= 0 ,0
Exp/Cntr=0.3,0.1

Type RM Length L Ch R = 1 ,26191   ,2208.75,2145.1,1627.42
BEGIN DESCRIPTION:
LOB - Kaufman LID1/Henderson LID1, ROB - Ellis LID2
END DESCRIPTION:
XS GIS Cut Line= 4
  2613487.036747 6834653.0571644 2605281.5679974 6833229.0120255
 2602909.4104089 6832882.7844453 2591372.6096641 6830962.8546181
#Sta/Elev= 30
       0  369.47   792.5  329.42  851.69  309.89 2830.34  302.89 2862.46  320.93
 2924.58     303 4439.92  302.85 4492.11  304.67 4512.69  327.68 5608.19  324.55
 5723.38  351.24 5970.42  324.82    6019  367.34 6141.37  341.26  6259.7  349.97
 6300.58  327.26 6735.18  356.02 6827.04  326.08 6938.13  324.34 8169.06  324.31
 8350.68   337.3 8579.84  324.38 8630.98  290.66 8747.63  288.54 8842.51  324.38
10837.65  321.0417091.92   318.319269.76  324.6121165.59   334.422420.79  389.34
#Mann= 9 ,-1 , 0
       0     .06       0 6938.13     .05       0 8169.06     .06       0
 8350.68     .06       0 8579.84    .055       0 8842.51     .15       0
10837.65     .05       017091.92     .15       019269.76     .06       0
Levee=-1,8350.68,337.3,-1,10681.42,334.4,,
#XS Ineff= 2 , 0
       0 8350.54     35010681.25       0     350
Permanent Ineff=
       F       F
#Block Obstruct= 1 ,-1
  2559.9 4512.69     320
Bank Sta=8579.84,8842.51
XS Rating Curve= 0 ,0
Exp/Cntr=0.3,0.1

Type RM Length L Ch R = 1 ,24046   ,2150.45,4285.27,1243.91
BEGIN DESCRIPTION:
LOB - Kaufman LID1/Henderson LID1, ROB - Ellis LID2
END DESCRIPTION:
XS GIS Cut Line= 4
  2618005.516276 6831956.4031599 2606504.9013308 6831441.7203589
 2603206.9846641 6831158.3870255 2591081.3268229 6830320.2000931
#Sta/Elev= 30
       0  372.76 1507.73  341.35 5358.95  325.91 5587.33  302.91 8724.77  326.14
 8961.27  303.85 8988.06  319.85 9656.12  333.38 11548.2  317.9411686.88  337.32
12055.11   325.312161.19  283.2512311.37  324.8814497.88  313.4914558.98  334.14
14670.65  313.8414846.15  337.9814915.68  314.1314988.75  321.6419406.97  322.04
19681.62  337.7720018.37  314.9521692.26  322.2521774.55  323.1622761.67     312
24279.19  332.1625179.28  316.2925435.15  342.0325515.71  326.6926976.66  353.15
#Mann= 9 ,-1 , 0
       0     .06       011686.88     .06       012055.11    .055       0
12311.37     .15       014988.75     .05       019406.97     .15       0
21692.26     .05       021774.55     .15       024279.19     .06       0
Levee=-1,11686.88,337.32,-1,14846.15,337.98,,
#XS Ineff= 2 , 0
       011688.81     35014846.14       0     350
Permanent Ineff=
       F       F
#Block Obstruct= 2 ,-1
 5539.12 8988.06     32019868.5521590.32  322.66
Bank Sta=12055.11,12311.37
XS Rating Curve= 0 ,0
Exp/Cntr=0.3,0.1

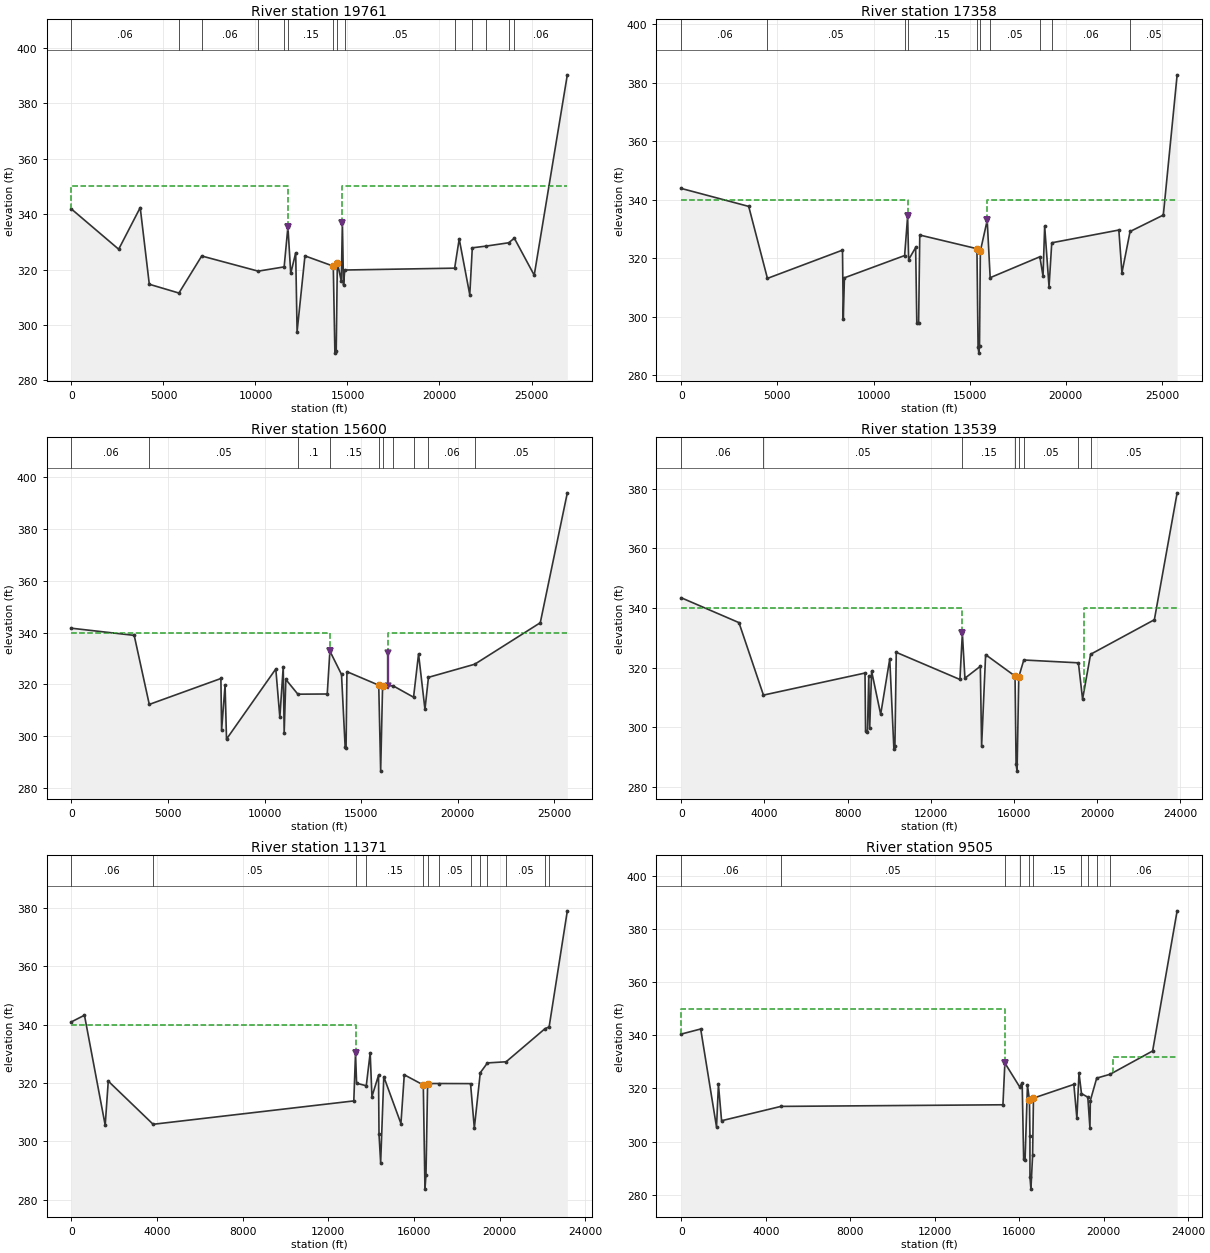
Type RM Length L Ch R = 1 ,19761   ,1667.72,2402.96,1502.54
BEGIN DESCRIPTION:
LOB - Kaufman LID1/Henderson LID1, ROB - Ellis LID2
END DESCRIPTION:
XS GIS Cut Line= 4
  2617675.582382  6829873.695452 2604705.0561615 6829337.5528737
 2603411.4228539 6830022.0524582 2590950.9369418 6829007.6189793
#Sta/Elev= 30
       0  341.85 2566.34  327.35  3736.7  342.38 4229.96  314.71 5839.93  311.54
  7078.7  324.9110148.36  319.4411558.66  320.9811763.17  335.44 11915.8  318.63
12185.79  326.0612261.16  297.5812688.54  324.9514228.22  321.25 14316.2  289.86
14387.41  290.4714449.01  322.5614664.05  315.8714722.77  336.99 14784.7  314.39
14850.28  319.8520823.65  320.5221071.54  331.0621645.63  310.9221782.82  327.86
22513.25  328.4623758.59  329.6824066.84  331.3325148.06  317.98 26946.9  390.28
#Mann= 14 ,-1 , 0
       0     .06       0 5839.93     .05       0  7078.7     .06       0
10148.36     .05       011558.66      .1       011763.17     .15       0
14228.22    .055       014449.01     .15       014850.28     .05       0
20823.65     .15       021782.82     .06       022513.25     .15       0
23758.59     .05       024066.84     .06       0
Levee=-1,11763.17,335.44,-1,14722.77,336.99,,
#XS Ineff= 2 , 0
       011763.38     35014722.91       0     350
Permanent Ineff=
       F       F
Bank Sta=14228.22,14449.01
XS Rating Curve= 0 ,0
Exp/Cntr=0.3,0.1

Type RM Length L Ch R = 1 ,17358   ,1420.5,1758.18,1573.47
BEGIN DESCRIPTION:
LOB - Kaufman LID1/Henderson LID1, ROB - Ellis LID2
END DESCRIPTION:
XS GIS Cut Line= 4
  2617325.027619   6828100.30077 2602483.9771289 6827689.9468975
 2601723.6513308 6828420.8407292 2591844.9203689 6827903.9698543
#Sta/Elev= 30
       0  343.84 3507.69   337.7 4481.58  313.09 8386.33  322.75 8426.59  299.28
 8486.79  313.2911618.63   320.911773.99  334.3111826.98  319.5112191.52  323.65
12251.93   297.812345.92  297.7512406.34  327.9115379.45  323.2415438.49  289.48
15479.56  287.5415513.17  289.8515557.89  322.4215913.33  332.9516067.94  313.33
18652.41  320.4818817.39  313.8418902.67  330.9619130.18   310.219271.54  325.26
22761.06  329.6222921.87  314.9723345.55  329.1225074.75  334.7425793.57  382.68
#Mann= 10 ,-1 , 0
       0     .06       0 4481.58     .05       011618.63      .1       0
11773.99     .15       015379.45    .055       015557.89     .15       0
16067.94     .05       018652.41     .15       019271.54     .06       0
23345.55     .05       0
Levee=-1,11773.99,334.31,-1,15913.33,332.95,,
#XS Ineff= 2 , 0
       011775.13     34015913.35       0     340
Permanent Ineff=
       F       F
Bank Sta=15379.45,15557.89
XS Rating Curve= 0 ,0
Exp/Cntr=0.3,0.1

Type RM Length L Ch R = 1 ,15600   ,1608.95,2060.49,2106.04
BEGIN DESCRIPTION:
LOB - Kaufman LID1/Henderson LID1, ROB - Ellis LID2
END DESCRIPTION:
XS GIS Cut Line= 4
  2616953.851988 6826656.8399823 2601977.2145359 6826298.6985631
 2600689.1096641  6826862.618507 2591425.2169149 6826347.5269563
#Sta/Elev= 30
       0  341.69 3247.39  338.93 4027.84  312.29  7734.2  322.29 7771.73  302.44
 7951.05  319.79 8024.98   298.910576.64  325.9810785.35  307.3210961.44  326.86
11009.95   301.311095.96  321.9211718.38  316.2413238.98  316.3113375.88  332.87
13977.19  323.8714166.39  295.6914213.29  295.57 14257.6  324.9315904.39  319.71
 16003.8  286.5516103.74 319.47616648.49  319.4717706.17  315.07 17965.2  331.78
18296.69  310.3718477.35  322.7420873.65   327.824265.14   343.825665.24  393.93
#Mann= 10 ,-1 , 0
       0     .06       0 4027.84     .05       011718.38      .1       0
13375.88     .15       015904.39    .055       016103.74     .15       0
16648.49     .05       017706.17     .15       018477.35     .06       0
20873.65     .05       0
Levee=-1,13375.88,332.87,-1,16378.11,332.03,,
#XS Ineff= 2 , 0
       013375.87     34016378.11       0     340
Permanent Ineff=
       F       F
Bank Sta=15904.39,16103.74
XS Rating Curve= 0 ,0
Exp/Cntr=0.3,0.1

Type RM Length L Ch R = 1 ,13539   ,1853.81,2167.97,2021.98
BEGIN DESCRIPTION:
LOB - Kaufman LID1/Henderson LID1
ROB IFA station 19377: flow expansion due to Ellis LID2 levee upstream
END DESCRIPTION:
XS GIS Cut Line= 4
  2616623.918094  6825234.000063 2601962.4806649 6824635.9948795
 2600358.5541085 6824776.2990626 2592791.3708253 6824383.1898411
#Sta/Elev= 30
       0  343.39 2775.84  335.06 3953.71  310.76 8841.22  318.16 8867.95  298.84
 8957.82  298.42 9020.78  317.01 9066.89  299.69 9158.91  318.78 9594.84   304.3
10031.85  322.8710230.43   292.8 10280.7  293.5710345.09   325.113408.84     316
13525.78  331.5113649.38  316.4214390.17  320.4114452.01  293.6114644.67  324.32
16060.18  317.1416110.86  287.5716157.83  285.2716241.02 316.86316481.97  322.53
 19109.8  321.58 19310.9  309.4119695.51  324.4422765.08  336.0323861.07  378.58
#Mann= 8 ,-1 , 0
       0     .06       0 3953.71     .05       013525.78     .15       0
16060.18    .055       016241.02     .15       016481.97     .05       0
 19109.8     .15       019695.51     .05       0
Levee=-1,13525.78,331.51,0,,,,
#XS Ineff= 2 , 0
       013521.13     340   19377       0     340
Permanent Ineff=
       F       F
Bank Sta=16060.18,16241.02
XS Rating Curve= 0 ,0
Exp/Cntr=0.3,0.1

Type RM Length L Ch R = 1 ,11371   ,1126.53,1866.67,1035.01
BEGIN DESCRIPTION:
LOB - Kaufman LID1/Henderson LID1
END DESCRIPTION:
XS GIS Cut Line= 4
  2616678.549045 6823617.0750931 2600683.9868244 6822697.6332504
 2599525.4779132 6822724.6510036 2593543.1323784 6822471.2417597
#Sta/Elev= 30
       0  341.02  607.45  343.29 1576.29  305.58 1719.57   320.7 3815.42   305.9
13191.75  313.9113271.83  330.3413321.82  319.9713774.15319.1138 13956.7  330.37
14039.04   315.414346.56  322.6814369.23  302.4814446.18  292.7314592.49   322.2
15393.52  306.1415549.96  322.8716438.22  319.3816516.24  283.6716564.05  288.58
16639.64  319.8617168.75  319.8818645.72  319.84 18822.4  304.5919100.58  323.58
19435.75  326.9420308.26  327.3322124.54  338.6822317.14  339.2923167.53  379.08
#Mann= 13 ,-1 , 0
       0     .06       0 3815.42     .05       013271.83     .06       0
13774.15     .15       016438.22    .055       016639.64     .15       0
17168.75     .05       018645.72     .15       019100.58     .05       0
19435.75     .06       020308.26     .05       022124.54     .06       0
22317.14     .05       0
Levee=-1,13271.83,330.34,0,,,,
#XS Ineff= 2 , 0
       013271.81     340               0
Permanent Ineff=
       F       F
Bank Sta=16438.22,16639.64
XS Rating Curve= 0 ,0
Exp/Cntr=0.3,0.1

Type RM Length L Ch R = 1 ,9505    ,1134.79,1900.98,1032.38
BEGIN DESCRIPTION:
LOB - Kaufman LID1/Henderson LID1
END DESCRIPTION:
XS GIS Cut Line= 4
  2617943.653671  6822780.116724 2602120.2802758  6821643.751677
 2600430.9125433 6821757.1829476 2594525.7712673 6821374.0195375
#Sta/Elev= 30
       0   340.5  919.31  342.41  1668.9  305.46 1758.73  321.51 1908.43  307.85
 4718.92  313.25 15227.5  313.8615319.42  329.5916014.85  320.6716138.72  322.04
16208.93  293.4216274.19  293.01 16389.1  321.1916483.71  315.5916505.97  302.11
16507.06   286.616552.25  282.0816633.09  294.9316672.79  316.3718584.62  321.53
18728.66  308.7218828.48  325.8918946.26  318.0919245.89  316.7119346.87  305.02
19365.78  315.4519666.52   323.920300.58  325.3522314.28  334.1323474.79  386.93
#Mann= 10 ,-1 , 0
       0     .06       0 4718.92     .05       015319.42     .06       0
16014.85     .15       016483.71    .055       016672.79     .15       0
18946.26     .05       019245.89     .15       019666.52     .05       0
20300.58     .06       0
Levee=-1,15319.42,329.59,0,,,,
#XS Ineff= 2 , 0
       015319.21     35020419.34       0     332
Permanent Ineff=
       F       F
Bank Sta=16483.71,16672.79
XS Rating Curve= 0 ,0
Exp/Cntr=0.3,0.1