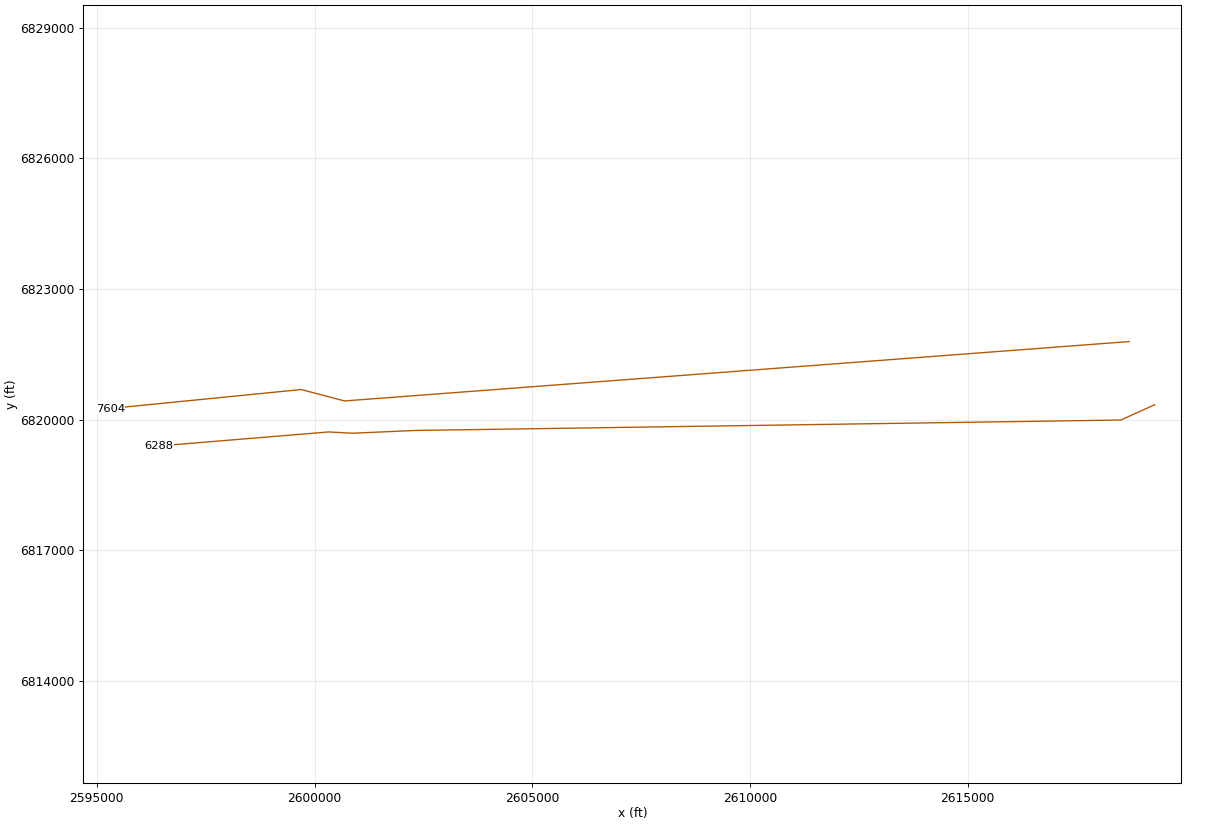
HEC-RAS study TR_FEMA.prj: Trinity_River_FEMA

--- TR_FEMA.g08 (geometry) --- (continued)

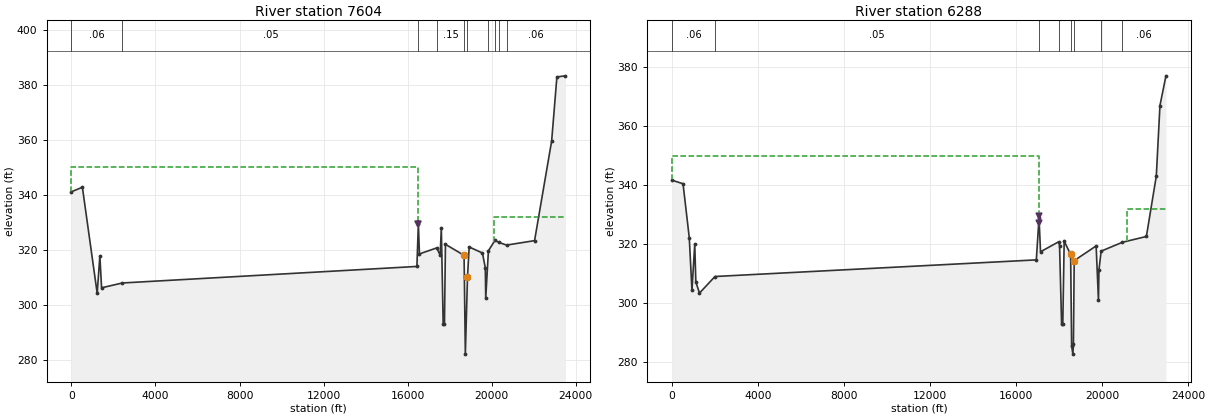
Type RM Length L Ch R = 1 ,7604    ,1109.26,1315.69,1024.77
BEGIN DESCRIPTION:
LOB - Kaufman LID1/Henderson LID1
END DESCRIPTION:
XS GIS Cut Line= 4
  2618706.625802  6821790.315041 2600688.1924188 6820426.8980209
  2599694.164641 6820689.1896876 2595306.2479743 6820253.2869098
#Sta/Elev= 30
       0  341.11  524.17  342.78 1228.28   304.3 1355.65  317.87 1437.33  306.28
 2425.82  308.0316439.61  314.0316509.06  329.6116559.86  318.5717380.66  320.75
17546.34  318.1217601.51  327.9817689.72  293.1217750.21  292.9817797.94  322.06
18683.77  318.0518744.51  282.2118846.83  310.2818926.93   321.119558.28   318.9
19694.32  313.4819714.03  302.4719842.43  319.7220153.77  323.4920349.21  322.72
20704.53  321.7822037.77  323.3922850.49  359.5523099.93   382.823507.45   383.2
#Mann= 10 ,-1 , 0
       0     .06       0 2425.82     .05       016509.06     .06       0
17380.66     .15       018683.77    .055       018846.83     .15       0
19842.43     .05       020153.77     .15       020349.21     .05       0
20704.53     .06       0
Levee=-1,16509.06,329.61,0,,,,
#XS Ineff= 2 , 0
       0   16509     35020091.76       0     332
Permanent Ineff=
       F       F
Bank Sta=18683.77,18846.83
XS Rating Curve= 0 ,0
Exp/Cntr=0.3,0.1

Type RM Length L Ch R = 1 ,6288    ,0,0,0
BEGIN DESCRIPTION:
LOB - Kaufman LID1/Henderson LID1
END DESCRIPTION:
XS GIS Cut Line= 6
2619293.73848072 6820341.02639792618516.223959626819988.94081597
2602318.95386082 6819749.15356592600866.164771656819685.79903381
2600323.704570476819714.953503062596424.624770226819393.00007872
#Sta/Elev= 30
       0  341.78   519.1  340.57   808.6  322.28  933.51  304.43 1063.51  320.15
  1113.5  307.29 1283.49  303.49 2003.45  309.1116938.12  314.7517063.12  328.99
17133.08   317.517972.71  320.8718017.69   319.618112.65  292.8618167.63  292.91
 18232.6  321.1118532.45  316.58 18578.5   285.518636.94  282.7918662.12  286.18
18698.05  314.4919717.65  319.4819825.78  300.99   19849  311.3819950.19  317.71
20936.78  320.7222052.49  322.6822513.65  343.1422683.49  367.0922962.33  377.16
#Mann= 8 ,-1 , 0
       0     .06       0 2003.45     .05       017063.12     .06       0
17972.71     .15       018532.45    .055       018698.05     .15       0
19950.19     .05       020936.78     .06       0
Levee=-1,17048.12,329.68,0,,,,
#XS Ineff= 2 , 0
       017048.58     350   21133       0     332
Permanent Ineff=
       F       F
Bank Sta=18532.45,18698.05
XS Rating Curve= 0 ,0
Exp/Cntr=0.3,0.1
Stream Node=Trinity River   ,                , 0 , 0 ,Upstream end
Stream Node=Trinity River   ,                , 0 , 1 ,Downstream end
LCMann Table=0

Chan Stop Cuts=-1
Use User Specified Reach Order=0
Composite Channel Slope=5

--- TR_FEMA.g01 (geometry) ---

Geom Title=Trinity_withLevee
Program Version=5.06
BEGIN GEOM DESCRIPTION:
With Levee
END GEOM DESCRIPTION:

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
River Reach=Trinity River   ,1

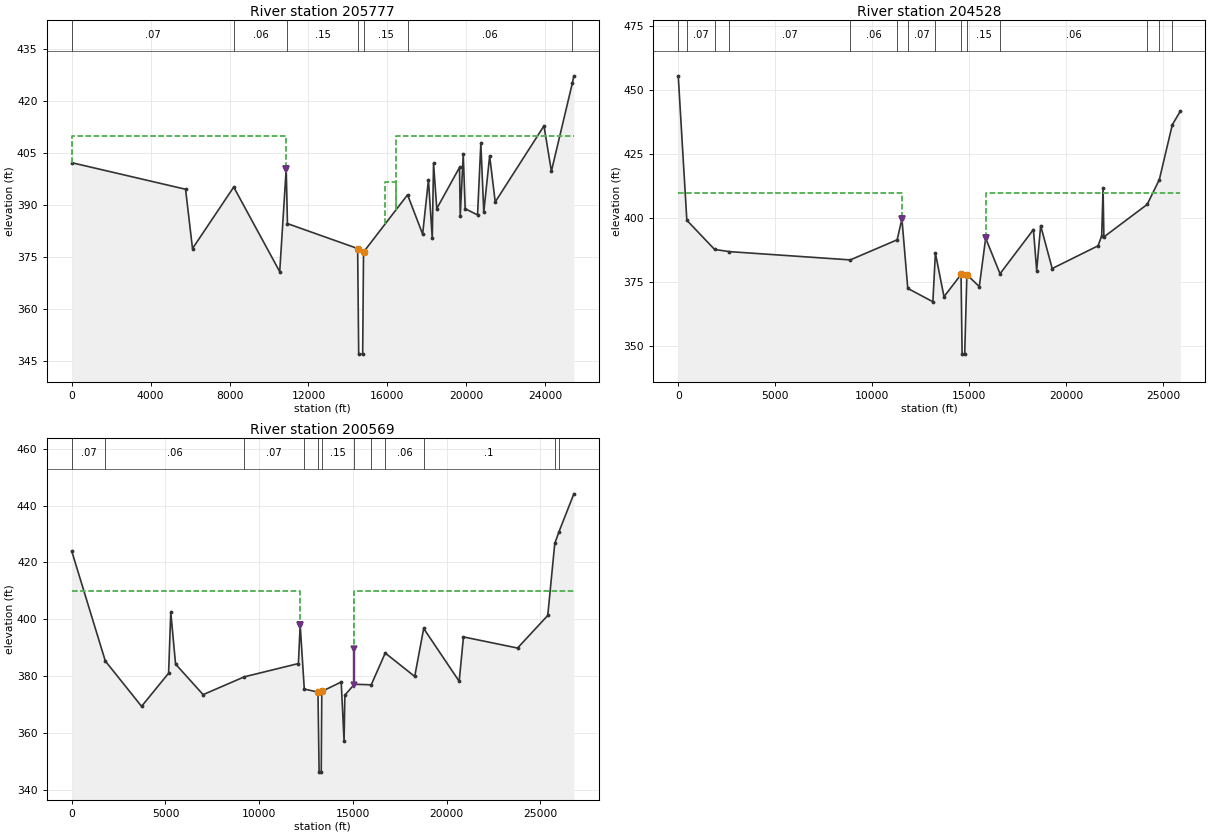
Type RM Length L Ch R = 1 ,205777  ,1262.75,1248.24,1229.51
BEGIN DESCRIPTION:
LOB - Southside WWTP
ROB IFA station 16416: flow contraction due to Dallas LID1/2 levee downstream
END DESCRIPTION:
XS GIS Cut Line= 6
2540980.83019298 6933539.73664742535497.477602626924208.30611411
2533614.000070366920921.000024692533600.635923866920903.28221235
 2529903.70565376914444.53364694 2528203.05241526911525.84775851
#Sta/Elev= 30
       0  402.32 5769.27  394.66 6121.02  377.55 8210.64  395.2910542.62  370.89
10870.96  400.54 10934.7  384.7514493.46  377.5614546.29   347.114748.07   347.1
14791.42  376.5417024.34  393.0617788.14  381.7118082.62  397.3718276.12  380.47
18341.35  402.1718504.74  389.0819659.18  400.9719693.92  387.0319847.13  404.74
19944.42  389.0520572.06  387.2620739.04  407.9220887.76  388.0721186.02  404.29
21468.32  390.9923940.48  412.9624316.52  399.8725381.49  425.37 25454.1  427.38
#Mann= 7 ,-1 , 0
       0     .07       0 8210.64     .06       0 10934.7     .15       0
14493.46    .055       014791.42     .15       017024.34     .06       0
25381.49     .08       0
Levee=-1,10870.96,400.54,0,,,,
#XS Ineff= 3 ,-1
       010870.96     41015871.74   16416  396.63   16416 25454.1     410
Permanent Ineff=
       F       F       F
Bank Sta=14493.46,14791.42
XS Rating Curve= 0 ,0
Exp/Cntr=0.3,0.1

Type RM Length L Ch R = 1 ,204528  ,2887.05,3959.05,2930.12
BEGIN DESCRIPTION:
LOB - Southside WWTP, ROB - Dallas LID1/2
END DESCRIPTION:
XS GIS Cut Line= 2
2542141.897480176933195.790666072529164.466924626910799.95733273
#Sta/Elev= 30
       0  455.63  443.94  399.25 1874.77  387.86 2636.03  387.01 8868.79  383.78
 11286.5  391.6211531.94  399.8111833.59  372.66   13128  367.4513257.32  386.45
13701.35  369.4114580.29  378.0914635.11     34714768.51     34714880.75  378.02
 15520.2  373.3515849.58  392.2716589.78  378.3818311.86  395.6418478.88  379.64
18685.27  397.1519279.01  380.4121641.73  389.2821830.52  393.1621901.42  411.66
21944.71  392.7524176.62  405.4324802.88  415.12 25470.9  436.52 25884.1  441.84
#Mann= 14 ,-1 , 0
       0     .06       0  443.94     .07       0 1874.77     .06       0
 2636.03     .07       0 8868.79     .06       0 11286.5     .07       0
11833.59     .07       013257.32     .15       014580.29    .055       0
14880.75     .15       016589.78     .06       024176.62      .1       0
24802.88     .08       0 25470.9     .06       0
Levee=-1,11531.94,399.81,-1,15849.58,392.27,,
#XS Ineff= 2 ,-1
       011531.94     41015849.58 25884.1     410
Permanent Ineff=
       F       F
Bank Sta=14580.29,14880.75
XS Rating Curve= 0 ,0
Exp/Cntr=0.3,0.1

Type RM Length L Ch R = 1 ,200569  ,2068.54,2056.32,2002.94
BEGIN DESCRIPTION:
LOB - Southside WWTP, ROB - Dallas LID1/2
END DESCRIPTION:
XS GIS Cut Line= 2
2544594.042023046931842.514654862531312.792023046908578.62576596
#Sta/Elev= 30
       0  423.94 1788.99  385.37 3724.12  369.43 5165.31  381.06  5282.7  402.49
 5537.92  384.29 7008.09  373.54 9204.36   379.8 12092.6  384.4712186.52  398.09
12405.92   375.513135.77  374.4413197.04   346.313309.94   346.313339.14  374.67
14376.03  377.98 14528.7  357.2114570.62  373.3715078.25  377.1915978.95     377
16723.98  388.1718297.74  379.9318776.03   396.820669.98  378.2320898.87  393.83
23784.09  389.9225396.01  401.3725770.55  426.6825998.04  430.8526788.13  444.13
#Mann= 12 ,-1 , 0
       0     .07       0 1788.99     .06       0 9204.36     .07       0
12405.92     .15       013135.77    .055       013339.14     .15       0
15078.25     .05       015978.95     .15       016723.98     .06       0
18776.03      .1       025770.55     .06       025998.04      .1       0
Levee=-1,12186.52,398.09,-1,15042.98,389.42,,
#XS Ineff= 2 , 0
       012186.52     41015042.98       0     410
Permanent Ineff=
       F       F
Bank Sta=13135.77,13339.14
XS Rating Curve= 0 ,0
Exp/Cntr=0.3,0.1