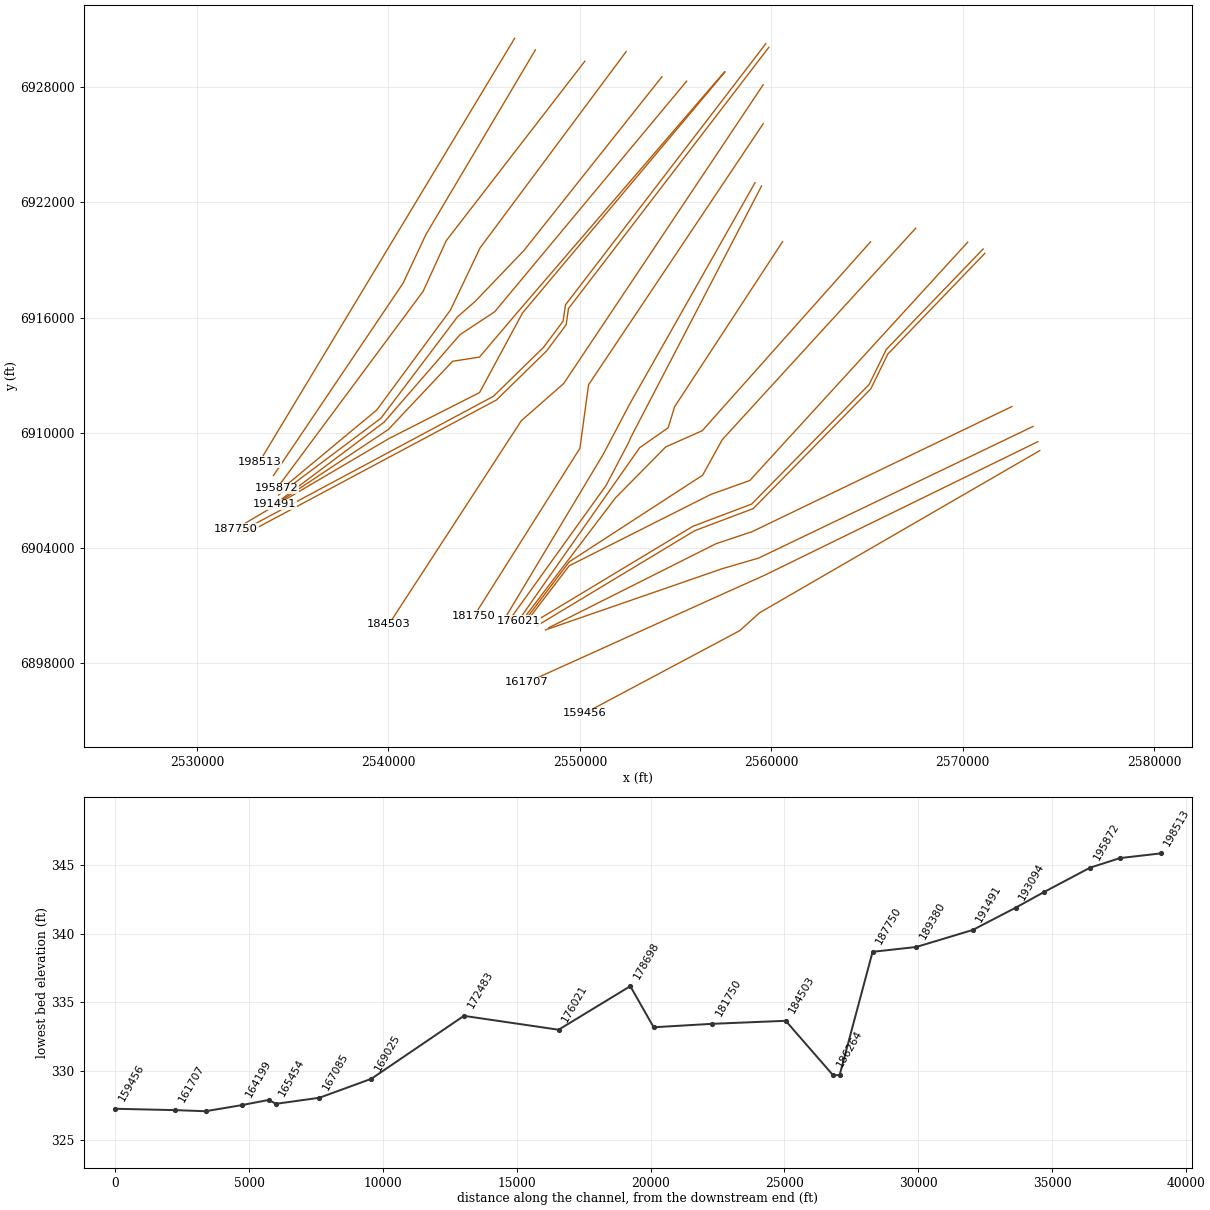
HEC-RAS study TR_FEMA.prj: Trinity_River_FEMA

--- TR_FEMA.g01 (geometry) --- (continued)

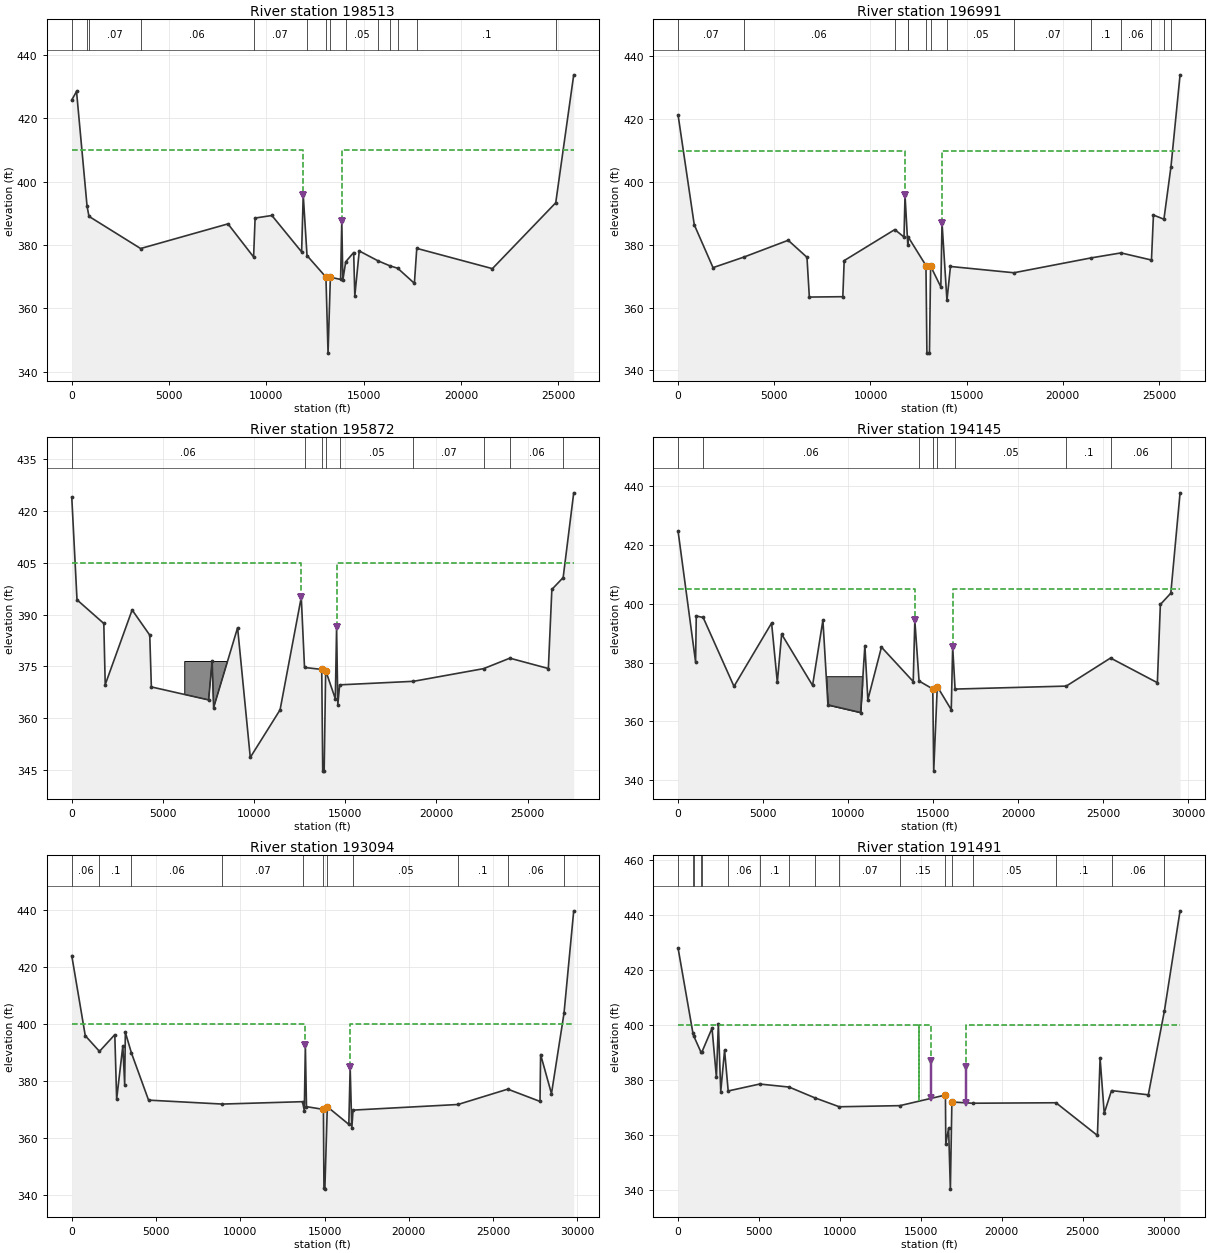
Type RM Length L Ch R = 1 ,198513  ,1460.65,1522.21,1546.82
BEGIN DESCRIPTION:
LOB - Southside WWTP, ROB - Dallas LID1/2
END DESCRIPTION:
XS GIS Cut Line= 2
2546593.000356376930554.320210412533259.667023046908470.98687708
#Sta/Elev= 30
       0  425.75  245.08  428.46  785.82  392.24  884.58  389.01 3538.59  378.86
  8028.9  386.64 9344.62  376.19 9422.44  388.4810284.69  389.2911812.69   377.8
11895.24  395.8312090.23  376.6313062.88  369.8413170.69  345.8413290.24  369.79
13815.75  369.1113876.77  387.6313931.21  368.8614077.49  374.6714487.86   377.6
14545.98  363.8614774.24  378.0915737.73  374.9816333.56  373.4416753.99  372.62
17607.92  367.8717730.47  378.9121616.22  372.5124872.14   393.325796.39  433.69
#Mann= 14 ,-1 , 0
       0     .07       0  785.82     .06       0  884.58     .07       0
 3538.59     .06       0 9344.62     .07       012090.23     .15       0
13062.88    .055       013290.24     .15       014077.49     .05       0
15737.73     .15       016333.56     .05       016753.99      .1       0
17730.47      .1       024872.14     .06       0
Levee=-1,11895.24,395.83,-1,13876.77,387.63,,
#XS Ineff= 2 , 0
       011895.24     41013876.77       0     410
Permanent Ineff=
       F       F
Bank Sta=13062.88,13290.24
XS Rating Curve= 0 ,0
Exp/Cntr=0.3,0.1

Type RM Length L Ch R = 1 ,196991  ,1114.91,1119.14,1044.18
BEGIN DESCRIPTION:
LOB - Southside WWTP, ROB - Dallas LID1/2
END DESCRIPTION:
XS GIS Cut Line= 4
2547677.578059796929952.10407455 2541957.4391709 6920324.0658801
2540764.383615346917785.437407882533997.022504236907764.60407454
#Sta/Elev= 30
       0  421.27  839.66  386.38 1815.93  372.72 3409.48  376.06 5723.11  381.43
 6699.35  376.02 6823.04  363.35 8563.77  363.47  8634.5  374.9611265.75  384.84
11744.94  382.4611797.07   395.811940.64  380.0711963.21  382.48 12885.5  373.39
12935.15   345.513068.07   345.513127.74   373.213659.69  366.5713720.65  387.01
13977.28  362.2714158.97  373.0917457.43  371.09 21480.1  375.8323024.23  377.41
24609.89  375.1424711.78  389.4725256.73  388.1325623.98  404.8926096.06  434.11
#Mann= 14 ,-1 , 0
       0     .07       0 3409.48     .06       011265.75     .07       0
11940.64     .06       011963.21     .15       0 12885.5    .055       0
13127.74     .15       013977.28     .05       017457.43     .07       0
 21480.1      .1       023024.23     .06       024609.89      .1       0
25256.73     .06       025623.98     .08       0
Levee=-1,11797.07,395.8,-1,13720.65,387.01,,
#XS Ineff= 2 , 0
       011797.07     41013720.65       0     410
Permanent Ineff=
       F       F
Bank Sta=12885.5,13127.74
XS Rating Curve= 0 ,0
Exp/Cntr=0.3,0.1

Type RM Length L Ch R = 1 ,195872  ,1736.76,1726.95,2123
BEGIN DESCRIPTION:
LOB - Southside WWTP, ROB - Dallas LID1/2
END DESCRIPTION:
XS GIS Cut Line= 4
2550259.667023046929359.875765962543024.453059796920010.14805602
2541811.258615346917361.536944912534173.275757926907095.38516339
#Sta/Elev= 30
       0  423.88  287.75  394.24 1757.09  387.42    1835  369.77 3310.85  391.32
 4278.01  384.05 4365.39   369.1 7505.83  365.35 7698.96  376.54    7781  363.13
 9095.51  386.19 9791.23  348.7511425.27  362.49   12588  394.9912765.73  374.72
13710.48  374.1513764.86   344.813843.92   344.813925.96  373.8214455.32  365.69
14525.15  386.3414592.48  363.9514693.44   369.718740.62  370.7222588.93  374.38
24027.44   377.426140.25  374.4126332.27  397.2426951.71  400.66 27531.3  425.12
#Mann= 9 ,-1 , 0
       0     .06       012765.73     .15       013710.48    .055       0
13925.96     .15       014693.44     .05       018740.62     .07       0
22588.93      .1       024027.44     .06       026951.71     .08       0
Levee=-1,12588,394.99,-1,14525.15,386.34,,
#XS Ineff= 2 , 0
       0   12588     40514525.15       0     405
Permanent Ineff=
       F       F
#Block Obstruct= 1 ,-1
 6197.83 8582.22  376.44
Bank Sta=13710.48,13925.96
XS Rating Curve= 0 ,0
Exp/Cntr=0.3,0.1

Type RM Length L Ch R = 1 ,194145  ,1483.79,1050.49,556.86
BEGIN DESCRIPTION:
LOB - Southside WWTP, ROB - Dallas LID1/2
END DESCRIPTION:
XS GIS Cut Line= 5
2552414.114273316929855.474110522544790.00861534 6919633.0184264
2543243.394032016916393.348287512539391.885627386911180.48068715
2534234.039646816906904.41294117
#Sta/Elev= 30
       0  424.67 1028.49  380.19 1068.58  395.85 1474.56  395.33 3287.19  371.88
 5499.11  393.44 5836.23  373.24 6089.75  389.65 7909.14   372.2 8517.13  394.42
 8812.55  365.5710733.65  362.9810985.54  385.7711161.06  367.3211960.74  385.24
13829.32  373.5213923.92  394.3114172.83   373.714979.29     37115034.01  343.02
 15243.9  371.8316066.48  363.9316149.17  385.3316290.69  370.9622830.01  371.97
 25434.8  381.53 28189.1  373.1328364.93  399.7628979.39  403.6129523.59  437.78
#Mann= 9 ,-1 , 0
       0     .07       0 1474.56     .06       014172.83     .15       0
14979.29    .055       0 15243.9     .15       016290.69     .05       0
22830.01      .1       0 25434.8     .06       028979.39     .08       0
Levee=-1,13923.92,394.31,-1,16149.17,385.33,,
#XS Ineff= 2 ,-1
       013923.92     40516149.1729523.59     405
Permanent Ineff=
       F       F
#Block Obstruct= 1 ,-1
 8647.3510836.41  375.33
Bank Sta=14979.29,15243.9
XS Rating Curve= 0 ,0
Exp/Cntr=0.3,0.1

Type RM Length L Ch R = 1 ,193094  ,1345.47,1602.93,571.88
BEGIN DESCRIPTION:
LOB - Bois D'Arc, ROB - Dallas LID1/2
END DESCRIPTION:
XS GIS Cut Line= 6
2554287.822272766928551.859861582547075.160235726919489.91541714
2544537.150976466916846.084398622543603.168337566916029.93509307
2539605.679296536910746.672576352534260.081313476906748.16294117
#Sta/Elev= 30
       0  423.87  802.13  395.77 1644.45  390.26 2553.75  396.14  2664.1  373.49
 3030.79  392.22 3140.18  378.62 3179.36  396.96 3542.33  389.68  4557.8  373.14
 8938.06  371.7613693.36   372.613800.43  369.4313862.06  392.4913928.82  370.85
14934.28  369.8914965.13  342.1215019.17  341.8915165.17  370.8216441.82  364.63
16521.31  384.7516617.88  363.1916691.96  369.6422916.42  371.6125874.64     377
27787.39  372.6927822.69  389.1528468.09  375.4129211.55  403.6529787.92  439.62
#Mann= 11 ,-1 , 0
       0     .06       0 1644.45      .1       0 3542.33     .06       0
 8938.06     .07       013693.36     .15       014934.28    .055       0
15165.17     .15       016691.96     .05       022916.42      .1       0
25874.64     .06       029211.55     .08       0
Levee=-1,13862.06,392.49,-1,16521.31,384.75,,
#XS Ineff= 2 ,-1
       013862.06     40016521.3129787.92     400
Permanent Ineff=
       F       F
Bank Sta=14934.28,15165.17
XS Rating Curve= 0 ,0
Exp/Cntr=0.3,0.1

Type RM Length L Ch R = 1 ,191491  ,988.29,2111.36,567.8
BEGIN DESCRIPTION:
LOB - Bois D'Arc, ROB - Dallas LID1/2
END DESCRIPTION:
XS GIS Cut Line= 5
2555578.266717196928321.341343082545553.422500736916302.54581884
2543740.689258426915107.066156172539778.685944756910550.30158257
 2534060.42853576906262.05183006
#Sta/Elev= 30
       0  427.89   914.4  397.07     958  396.09 1394.34  390.33 1462.77  390.03
 2095.76  398.81 2366.84  380.92 2487.11  400.45 2634.68  375.75  2870.8   390.8
 3094.27  375.98 5041.25   378.5 6856.41   377.4 8429.85  373.52 9956.04  370.23
13701.74  370.6416513.88  374.5116536.92  356.6116709.25  362.4516819.04  340.27
16912.14  371.9718190.28  371.5223342.01  371.6925903.58  359.7926067.98  387.88
26323.71  367.8826773.42  376.1229046.65  374.58 30044.5  405.21 31008.1  441.51
#Mann= 17 ,-1 , 0
       0     .08       0   914.4     .06       0     958     .08       0
 1394.34     .06       0 1462.77      .1       0 3094.27     .06       0
 5041.25      .1       0 6856.41     .06       0 8429.85      .1       0
 9956.04     .07       013701.74     .15       016513.88    .055       0
16912.14     .15       018190.28     .05       023342.01      .1       0
26773.42     .06       0 30044.5     .08       0
Levee=-1,15621.35,387.06,-1,17812.09,384.81,,
#XS Ineff= 3 ,-1
       0 14856.5     400 14856.515621.35     40017812.09 31008.1     400
Permanent Ineff=
       F       F       F
Bank Sta=16513.88,16912.14
XS Rating Curve= 0 ,0
Exp/Cntr=0.3,0.1

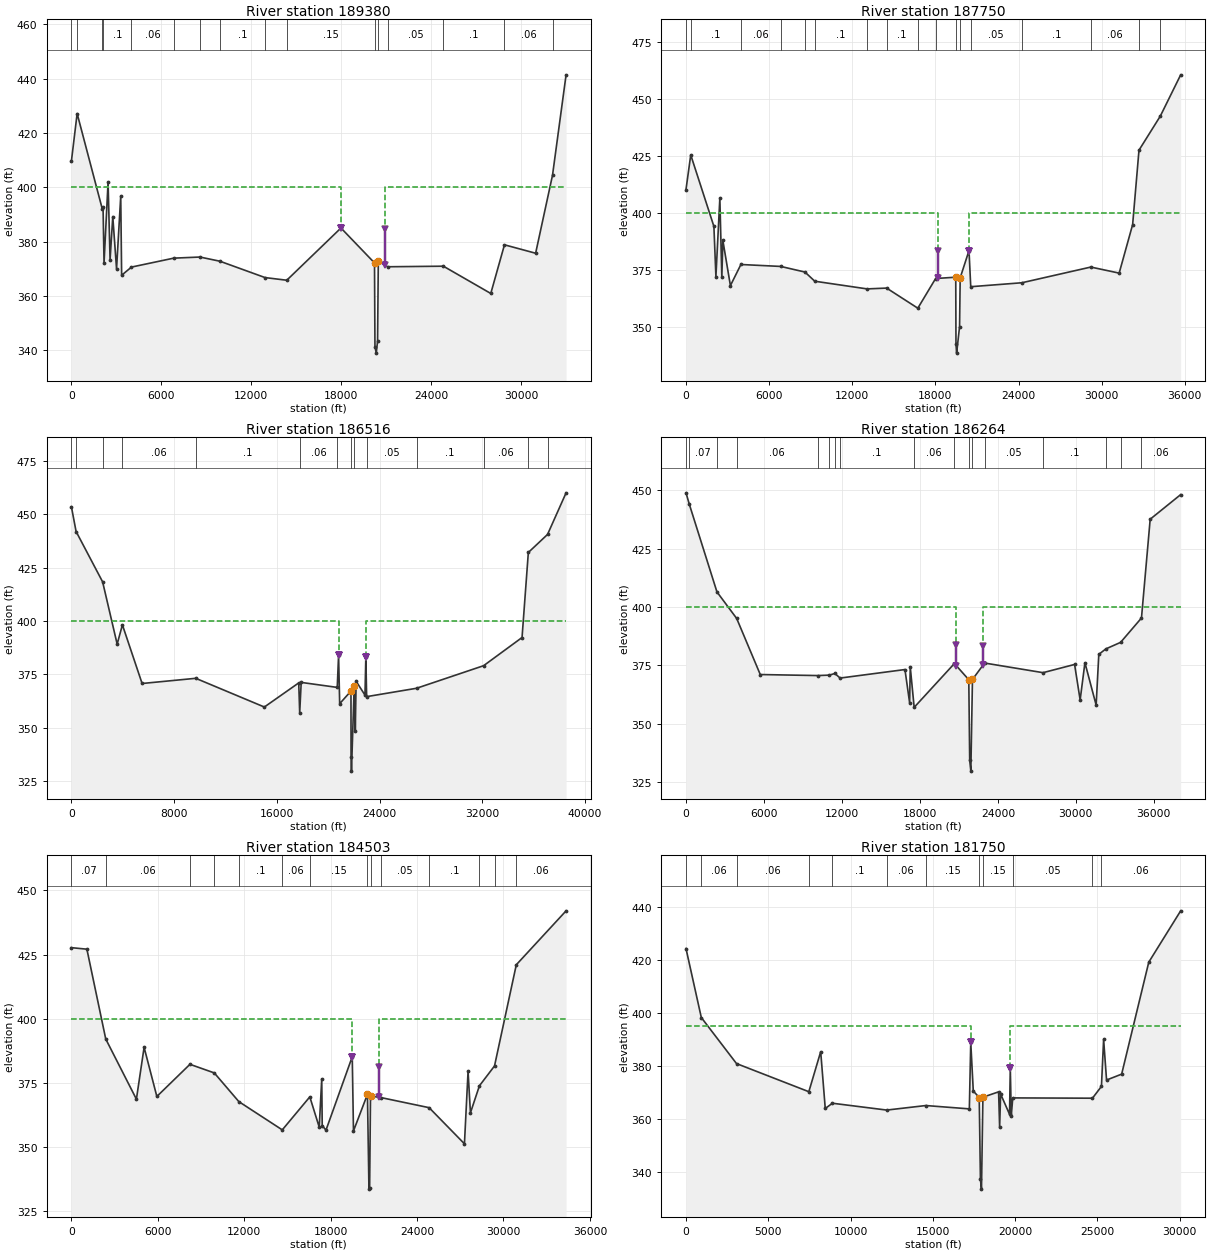
Type RM Length L Ch R = 1 ,189380  ,205.4,1630.38,1758.4
BEGIN DESCRIPTION:
LOB - Bois D'Arc, ROB - Dallas LID1/2
END DESCRIPTION:
XS GIS Cut Line= 6
  2557557.278625 6928809.5192494 2546769.9681061 6916304.8598616
  2544756.513245 6913938.4536116 2543350.9576894 6913718.6098616
 2539995.6050314 6910162.3039914 2534109.9081669 6906263.9017463
#Sta/Elev= 30
       0  409.66  382.37  427.22 2066.09  391.96 2111.19  392.75 2177.07  372.26
 2445.48  401.93 2579.32  373.42 2759.69   389.3 3011.42  370.03 3290.06  396.77
 3350.78  367.69 4004.94   370.7 6821.75  373.99 8574.54   374.4 9904.93  372.86
12916.52  366.8414364.36  365.8617978.65  385.0920215.37  372.2420245.75  341.42
20332.55  339.0320420.69  343.5120468.97   372.921083.89  370.8224809.52  371.03
27970.71  360.9928882.99   378.9   30962   375.832088.22  404.51 32993.3  441.47
#Mann= 16 ,-1 , 0
       0     .07       0  382.37      .1       0 2066.09     .08       0
 2111.19      .1       0 4004.94     .06       0 6821.75      .1       0
 8574.54     .06       0 9904.93      .1       012916.52     .07       0
14364.36     .15       020215.37    .055       020468.97     .15       0
21083.89     .05       024809.52      .1       028882.99     .06       0
32088.22     .08       0
Levee=-1,17978.65,385.09,-1,20921.35,384.68,,
#XS Ineff= 2 ,-1
       017978.65     40020921.35 32993.3     400
Permanent Ineff=
       F       F
Bank Sta=20215.37,20468.97
XS Rating Curve= 0 ,0
Exp/Cntr=0.3,0.1

Type RM Length L Ch R = 1 ,187750  ,1654.61,1233.35,710.34
BEGIN DESCRIPTION:
LOB - Bois D'Arc, ROB - Dallas LID1/2
END DESCRIPTION:
XS GIS Cut Line= 5
2557577.386206416928797.378293492547009.279724936916245.27181201
2544761.617613766912088.929152132540023.244450286909687.41087415
2532045.813894736904999.91087415
#Sta/Elev= 30
       0  410.26  342.82  425.39 2013.52  394.14 2158.93  372.18 2443.22  406.42
 2586.02  371.87 2660.15  387.99    3205  368.22  3962.1  377.46 6839.49  376.61
 8585.85  374.15  9293.2  370.1413071.24  366.7814477.86  367.14 16729.9  358.34
18015.08  371.3319466.71   371.919483.08  342.7219528.79  338.6819742.26  350.26
19786.89  371.6320423.79  383.5520548.26  367.7424238.57  369.4729214.57  376.34
31259.22  373.6932231.63  394.9232689.61  427.4734227.79  442.3835698.68  460.45
#Mann= 17 ,-1 , 0
       0     .07       0  342.82      .1       0  3962.1     .06       0
 6839.49      .1       0 8585.85     .06       0  9293.2      .1       0
13071.24     .07       014477.86      .1       0 16729.9     .06       0
18015.08     .15       019466.71    .055       019786.89     .15       0
20548.26     .05       024238.57      .1       029214.57     .06       0
32689.61     .08       034227.79     .06       0
Levee=-1,18193.79,383.19,-1,20423.79,383.55,,
#XS Ineff= 2 ,-1
       018193.79     40020423.7935698.68     400
Permanent Ineff=
       F       F
Bank Sta=19466.71,19786.89
XS Rating Curve= 0 ,0
Exp/Cntr=0.5,0.3

Type RM Length L Ch R = 1 ,186516  ,201.27,252.24,272.65
BEGIN DESCRIPTION:
US Bridge
LOB - Bois D'Arc, ROB - Dallas LID1/2
END DESCRIPTION:
XS GIS Cut Line= 6
2559712.908234356930276.007165022549247.630456586916657.95160946
2549126.428199636915812.501667332548110.369171856914455.29680621
2545486.671255186911894.532917332532205.312748246904802.37435251
#Sta/Elev= 30
       0  453.62  365.68  442.01 2431.77   418.4 3564.01  389.22 3972.03  398.26
 5505.96  370.77 9682.73   373.215027.22  359.7417703.92  371.05 17779.5  357.05
17897.26  371.2820703.97  368.9420807.66  383.9220893.23  361.3121773.35  367.22
21778.85 336.09421812.34 329.69622024.35  369.6822072.81  370.4222108.38  348.51
22174.81  371.7922863.36  365.3422930.59  383.1422993.09  364.61   26878  368.53
32104.46  379.1235096.33  392.3235586.17  432.1837082.52  440.6438526.05  460.14
#Mann= 14 ,-1 , 0
       0     .08       0  365.68     .07       0 2431.77      .1       0
 3972.03     .06       0 9682.73      .1       0 17779.5     .06       0
20703.97     .15       021773.35    .055       022024.35     .15       0
22993.09     .05       0   26878      .1       032104.46     .06       0
35586.17     .08       037082.52     .06       0
Levee=-1,20807.66,383.92,-1,22930.59,383.14,,
#XS Ineff= 2 ,-1
       020807.66     40022930.5938526.05     400
Permanent Ineff=
       F       F
Bank Sta=21773.35,22024.35
XS Rating Curve= 0 ,0
Exp/Cntr=0.5,0.3

Type RM Length L Ch R = 1 ,186264  ,1855.44,1760.58,2233.35
BEGIN DESCRIPTION:
DS Bridge
LOB - Bois D'Arc, ROB - Dallas LID1/2
END DESCRIPTION:
XS GIS Cut Line= 6
2559871.226754126930085.983048982549405.948976346916467.92749342
2549284.746719396915622.477551292548268.687691616914265.27269018
2545644.989774956911704.508801292532761.29377277 6904841.7347546
#Sta/Elev= 30
       0  448.92  256.68     444 2382.59  406.47 3900.85  395.11  5715.6  371.09
10141.44  370.6511031.58  370.8411457.67  371.5511859.16  369.5816849.34  373.23
17208.86  358.9817256.36  374.3717558.05  357.03 20653.4   375.821761.57  368.87
21831.52 334.34321919.58  329.7222043.92  368.9822975.62  376.0227475.03  371.89
29902.81  375.4130329.89  360.2330698.82  376.1531561.26  358.0231766.54  379.73
32307.07  382.0733443.98  384.8735049.96  395.3135720.62  437.6238066.94  448.16
#Mann= 17 ,-1 , 0
       0     .08       0  256.68     .07       0 2382.59      .1       0
 3900.85     .06       010141.44      .1       011031.58     .06       0
11457.67     .06       011859.16      .1       017558.05     .06       0
 20653.4     .15       021761.57    .055       022043.92     .15       0
22975.62     .05       027475.03      .1       032307.07     .06       0
33443.98     .05       035049.96     .06       0
Levee=-1,20792.77,383.68,-1,22865.83,383.32,,
#XS Ineff= 2 ,-1
       020792.77     40022865.8338066.94     400
Permanent Ineff=
       F       F
Bank Sta=21761.57,22043.92
XS Rating Curve= 0 ,0
Exp/Cntr=0.5,0.3

Type RM Length L Ch R = 1 ,184503  ,1141.76,2752.93,3502.22
BEGIN DESCRIPTION:
LOB - Bois D'Arc, ROB - Dallas LID1/2
END DESCRIPTION:
XS GIS Cut Line= 4
2559572.852699236928131.371101242549158.807805166912562.74643566
2546939.363360716910618.301991212540024.241588126900006.37110124
#Sta/Elev= 30
       0  427.72 1075.28  427.13 2384.82  392.14 4513.55   368.7 5048.05  388.89
 5933.32  369.75 8231.53  382.28 9920.58  378.9311625.88  367.7514641.38  356.74
16553.76   369.617207.45   357.8 17381.7  376.6117415.02  358.4217676.22  356.63
19500.41  385.2519585.37  356.3320555.35  370.5920659.95  333.6620707.16  334.17
20767.44  369.9621487.21  369.3324838.63  365.3927289.81  351.3227541.37  379.56
27706.21  363.3828329.32  373.9129377.92  381.64 30890.8  421.0634347.37  442.07
#Mann= 14 ,-1 , 0
       0     .07       0 2384.82     .06       0 8231.53     .06       0
 9920.58     .06       011625.88      .1       014641.38     .06       0
16553.76     .15       020555.35    .055       020767.44     .15       0
21487.21     .05       024838.63      .1       028329.32     .06       0
29377.92     .05       0 30890.8     .06       0
Levee=-1,19500.41,385.25,-1,21379.67,381.19,,
#XS Ineff= 2 ,-1
       019500.41     40021379.6734347.37     400
Permanent Ineff=
       F       F
Bank Sta=20555.35,20767.44
XS Rating Curve= 0 ,0
Exp/Cntr=0.3,0.1

Type RM Length L Ch R = 1 ,181750  ,2178.07,2178.36,1237.92
BEGIN DESCRIPTION:
LOB - Bois D'Arc, ROB - Dallas LID1/2
END DESCRIPTION:
XS GIS Cut Line= 4
2559575.33418071 6926100.72295312550454.46752738 6912496.2533801
2550002.664865346909181.624907882544471.167514056900441.00073088
#Sta/Elev= 30
       0  424.22  930.84  398.19 3070.86  380.81 7466.12   370.2 8187.52   385.3
 8464.59  363.87 8900.14  365.8512198.84  363.2714578.21  364.9817222.38  363.72
 17308.4  388.8417461.85  370.4717822.88  368.0117896.15  337.1317960.37  333.44
18047.38  368.1219001.08  370.1519063.98   356.819122.93  369.3519665.02  361.68
19711.52  379.2819771.51  361.0919861.27  367.8624706.16  367.7525251.92  372.21
25384.35  389.9225562.23   374.626480.27  376.8328128.73  419.0830068.09  438.45
#Mann= 12 ,-1 , 0
       0     .07       0  930.84     .06       0 3070.86     .06       0
 7466.12     .06       0 8900.14      .1       012198.84     .06       0
14578.21     .15       017822.88    .055       018047.38     .15       0
19861.27     .05       024706.16      .1       025251.92     .06       0
Levee=-1,17308.4,388.84,-1,19711.52,379.28,,
#XS Ineff= 2 ,-1
       0 17308.4     39519711.5230068.09     395
Permanent Ineff=
       F       F
Bank Sta=17822.88,18047.38
XS Rating Curve= 0 ,0
Exp/Cntr=0.3,0.1

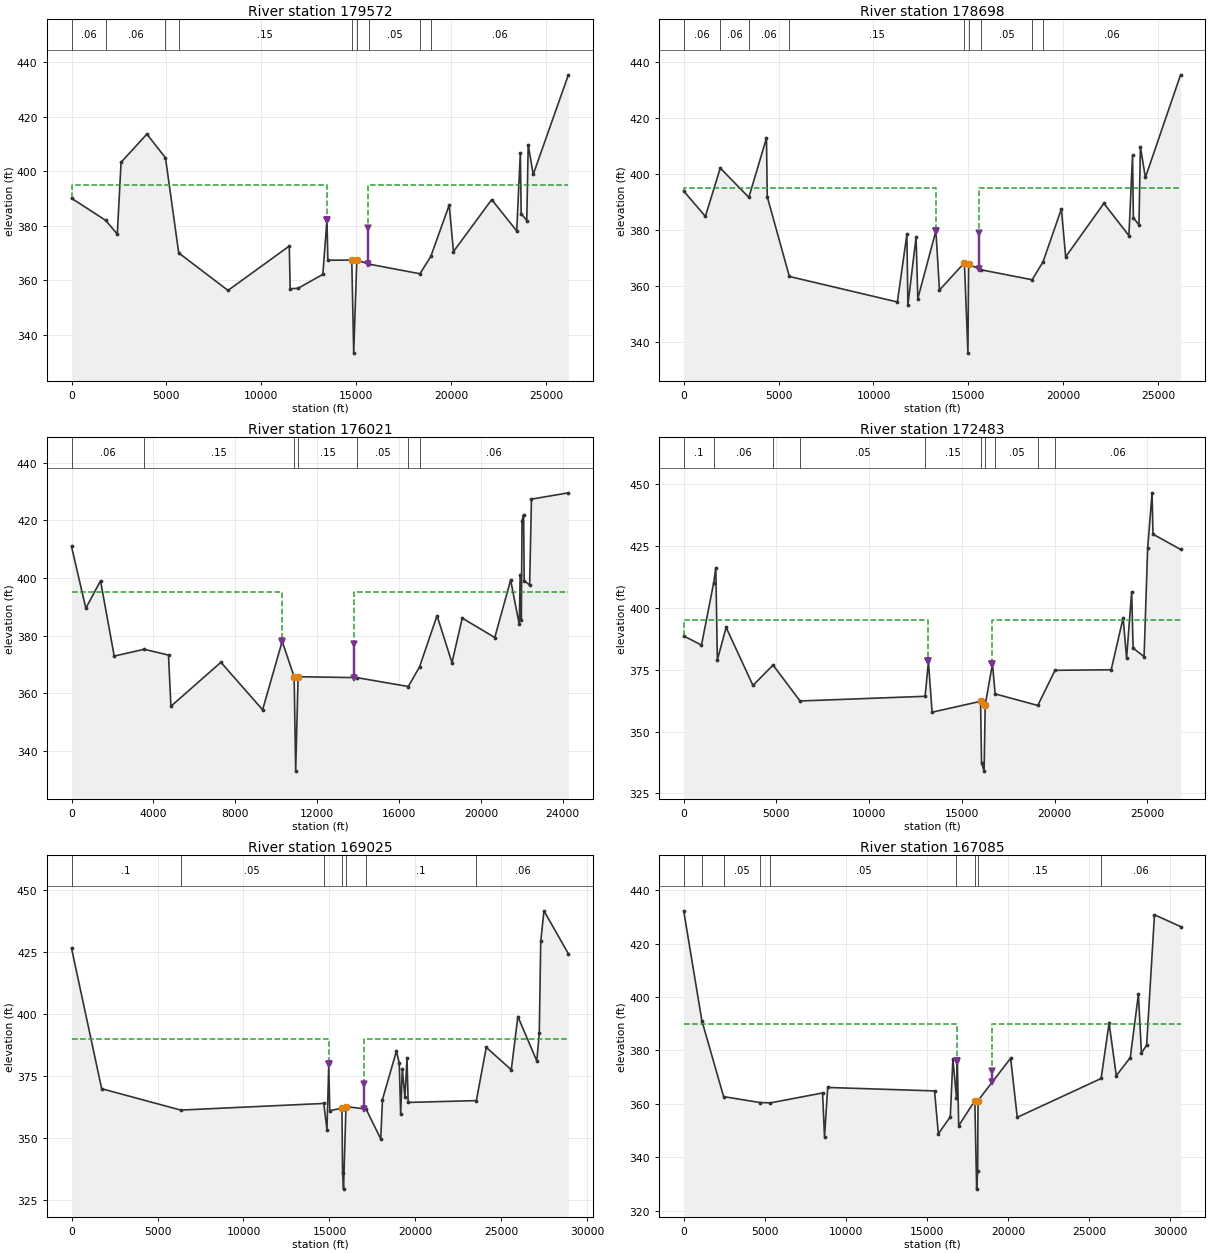
Type RM Length L Ch R = 1 ,179572  ,766.97,874.08,934.72
BEGIN DESCRIPTION:
LOB - Bois D'Arc, ROB - Dallas LID1/2
END DESCRIPTION:
XS GIS Cut Line= 4
2559148.762421456923029.18128644 2552593.20686596911473.62573088
2551232.095754796908890.29239755 2546093.20686596900334.73684199
#Sta/Elev= 30
       0  390.02 1798.58  381.93 2413.01  376.87 2611.82  403.22  3971.5  413.57
 4951.44  404.86 5649.14  369.95 8245.78   356.211476.02  372.4911520.72  356.82
 11935.7  356.9813243.16  362.0813460.08  382.12 13508.2  367.2814767.13  367.34
14869.71  333.1915033.64  367.3215676.41  365.8518360.13  362.3218932.91  368.69
19901.66  387.5420125.82  370.4622140.59  389.5323458.89  378.0423649.71  406.69
23694.22  384.41   23989  381.8524063.88   409.724327.84  398.75 26181.2  435.32
#Mann= 9 ,-1 , 0
       0     .06       0 1798.58     .06       0 4951.44     .06       0
 5649.14     .15       014767.13    .055       015033.64     .15       0
15676.41     .05       018360.13      .1       018932.91     .06       0
Levee=-1,13460.08,382.12,-1,15617.55,378.97,,
#XS Ineff= 2 ,-1
       013460.08     39515617.55 26181.2     395
Permanent Ineff=
       F       F
Bank Sta=14767.13,15033.64
XS Rating Curve= 0 ,0
Exp/Cntr=0.3,0.1

Type RM Length L Ch R = 1 ,178698  ,1580.48,2677.02,409.08
BEGIN DESCRIPTION:
LOB - Bois D'Arc, ROB - Dallas LID1/2
END DESCRIPTION:
XS GIS Cut Line= 5
2559490.928754236922857.666574542552647.425477186909725.03967755
2552552.475919656909494.523410582551369.969250626907246.30085465
2546356.22769924  6900280.049342
#Sta/Elev= 30
       0  393.92 1141.95   384.9 1926.79  402.09 3431.82  391.67 4360.95  412.76
 4402.37  391.92 5567.51  363.4911258.94   354.411761.14   378.511812.03  353.22
12245.06  377.5412336.06   355.613289.19  379.7313476.76  358.6514791.64  368.36
 14976.7  336.1815012.84  367.8315676.41  365.8518360.13  362.3218932.91  368.69
19901.66  387.5420125.82  370.4622140.59  389.5323458.89  378.0423649.71  406.69
23694.22  384.41   23989  381.8524063.88   409.724327.84  398.75 26181.2  435.32
#Mann= 9 ,-1 , 0
       0     .06       0 1926.79     .06       0 3431.82     .06       0
 5567.51     .15       014791.64    .055       015012.84     .15       0
15676.41     .05       018360.13      .1       018932.91     .06       0
Levee=-1,13289.19,379.73,-1,15534.78,379,,
#XS Ineff= 2 ,-1
       013289.19     39515534.56 26181.2     395
Permanent Ineff=
       F       F
Bank Sta=14791.64,15012.84
XS Rating Curve= 0 ,0
Exp/Cntr=0.3,0.1

Type RM Length L Ch R = 1 ,176021  ,2531.23,3537.5,700.82
BEGIN DESCRIPTION:
LOB - Bois D'Arc, ROB - Dallas LID1/2
END DESCRIPTION:
XS GIS Cut Line= 5
2560588.416356656919955.471795722554947.803754236911347.82861158
2554613.081532016910254.773056032553119.24968998 6909210.7495735
2546787.65131034 6900195.8479531
#Sta/Elev= 30
       0   410.9   699.4  389.49 1417.12     399 2086.31   372.9 3545.85  375.25
 4738.33  373.25 4855.57  355.49 7298.32  370.75 9335.43  354.28 10291.1     378
10875.75  365.7410950.68  333.0111069.77  365.7513947.64  365.4216453.32  362.35
17004.74  369.21 17856.7  386.9118586.62   370.619087.61  386.0720677.71  379.33
21452.25  399.2821873.21  383.8621917.79  401.1421974.12  385.3622008.61  419.78
22084.37  421.9722114.88  399.0922380.36   397.522468.47  427.3124273.08   429.5
#Mann= 7 ,-1 , 0
       0     .06       0 3545.85     .15       010875.75    .055       0
11069.77     .15       013947.64     .05       016453.32      .1       0
17004.74     .06       0
Levee=-1,10296.09,378,-1,13805.69,376.97,,
#XS Ineff= 2 ,-1
       010296.09     39513805.6924273.08     395
Permanent Ineff=
       F       F
Bank Sta=10875.75,11069.77
XS Rating Curve= 0 ,0
Exp/Cntr=0.3,0.1

Type RM Length L Ch R = 1 ,172483  ,1181.15,3458.81,1936.55
BEGIN DESCRIPTION:
LOB - Bois D'Arc, ROB - Dallas LID1/2
END DESCRIPTION:
XS GIS Cut Line= 5
2565182.616588126919946.716008662556391.389458526910099.22201427
2554487.454273346909257.208125382551870.984643686906612.51461977
2547148.762421456900418.07017533
#Sta/Elev= 30
       0  388.58  959.04   384.9 1619.23  410.13  1731.1  416.16 1815.83  378.93
 2287.92  392.01 3734.32  368.61 4818.85  376.83 6272.44  362.33 13018.8  364.22
13195.63  378.2713393.67   357.8 16009.4   362.216059.69  337.3716197.71  334.02
16257.81  360.7516649.41  377.3216794.36  365.1919091.59  360.5320022.87  374.71
23050.08  374.9323695.19  395.8623880.43  379.5724155.03  406.4524233.05  383.67
24823.93  380.2325016.31  423.9125255.74  446.3425304.65  429.6626791.89  423.49
#Mann= 10 ,-1 , 0
       0      .1       0 1619.23     .06       0 4818.85      .1       0
 6272.44     .05       0 13018.8     .15       0 16009.4    .055       0
16257.81     .15       016794.36     .05       019091.59      .1       0
20022.87     .06       0
Levee=-1,13195.63,378.27,-1,16649.41,377.32,,
#XS Ineff= 2 ,-1
       013195.63     39516649.4126791.89     395
Permanent Ineff=
       F       F
Bank Sta=16009.4,16257.81
XS Rating Curve= 0 ,0
Exp/Cntr=0.3,0.1

Type RM Length L Ch R = 1 ,169025  ,2540.16,1939.9,813.21
BEGIN DESCRIPTION:
LOB - Bois D'Arc, ROB - Dallas LID1/2
END DESCRIPTION:
XS GIS Cut Line= 5
2567543.277467766920656.860684622557438.775976456909634.40268566
2556412.387087566907779.541574552549440.672143686903262.27156422
2547322.616588126900463.66045311
#Sta/Elev= 30
       0  426.44 1754.32  369.86 6351.27  361.2614668.24  363.9414853.24  353.36
14957.67  379.6315017.11  361.02 15723.6  362.0415760.87  336.0915816.71  329.44
 15958.5  362.68 17127.3  361.6617979.41  349.6518080.67  365.5218889.65  384.95
19055.78  380.2919138.18  359.6719233.91  377.7519385.28  366.4119506.69  382.12
19574.07  364.3423539.21  365.0824114.59  386.5125569.27  377.4925952.78  398.93
27051.51  381.0927197.13  392.1327283.32  429.2327470.32  441.4828889.98  424.18
#Mann= 7 ,-1 , 0
       0      .1       0 6351.27     .05       014668.24     .15       0
 15723.6    .055       0 15958.5     .15       0 17127.3      .1       0
23539.21     .06       0
Levee=-1,14957.67,379.63,-1,17013.93,371.76,,
#XS Ineff= 2 ,-1
       014957.67     39017013.9328889.98     390
Permanent Ineff=
       F       F
Bank Sta=15723.6,15958.5
XS Rating Curve= 0 ,0
Exp/Cntr=0.3,0.1

Type RM Length L Ch R = 1 ,167085  ,1087.43,1630.75,1236.82
BEGIN DESCRIPTION:
LOB - Bois D'Arc, ROB - Dallas LID1/2
END DESCRIPTION:
XS GIS Cut Line= 5
2570255.574362936919925.554734122558876.389719376907504.55343791
2556828.766274576906773.46139785 2549444.14436596903060.88267533
 2547409.58254826900405.39565756
#Sta/Elev= 30
       0  432.25 1118.92  391.17 2460.13   362.7 4683.68  360.49 5344.28  360.35
 8561.69  364.06 8679.91  347.56 8876.83  366.1215463.17  364.8315699.37  348.77
16434.24  355.1416595.36  376.8116816.95  362.1816867.19  375.9816952.58  351.81
17946.58  361.1718059.61  328.0618122.12  334.7618143.76  361.2220154.42  377.07
20563.17  354.9525732.03  369.4826224.28  390.22 26668.4  370.5427530.81  377.32
28030.26  400.9828217.71  379.07 28536.5  381.8929022.37  430.7830630.34  426.35
#Mann= 9 ,-1 , 0
       0     .07       0 1118.92      .1       0 2460.13     .05       0
 4683.68      .1       0 5344.28     .05       016816.95     .15       0
17946.58    .055       018143.76     .15       025732.03     .06       0
Levee=-1,16867.19,375.98,-1,19010.01,372.34,,
#XS Ineff= 2 ,-1
       016867.19     39019010.0130630.34     390
Permanent Ineff=
       F       F
Bank Sta=17946.58,18143.76
XS Rating Curve= 0 ,0
Exp/Cntr=0.5,0.3

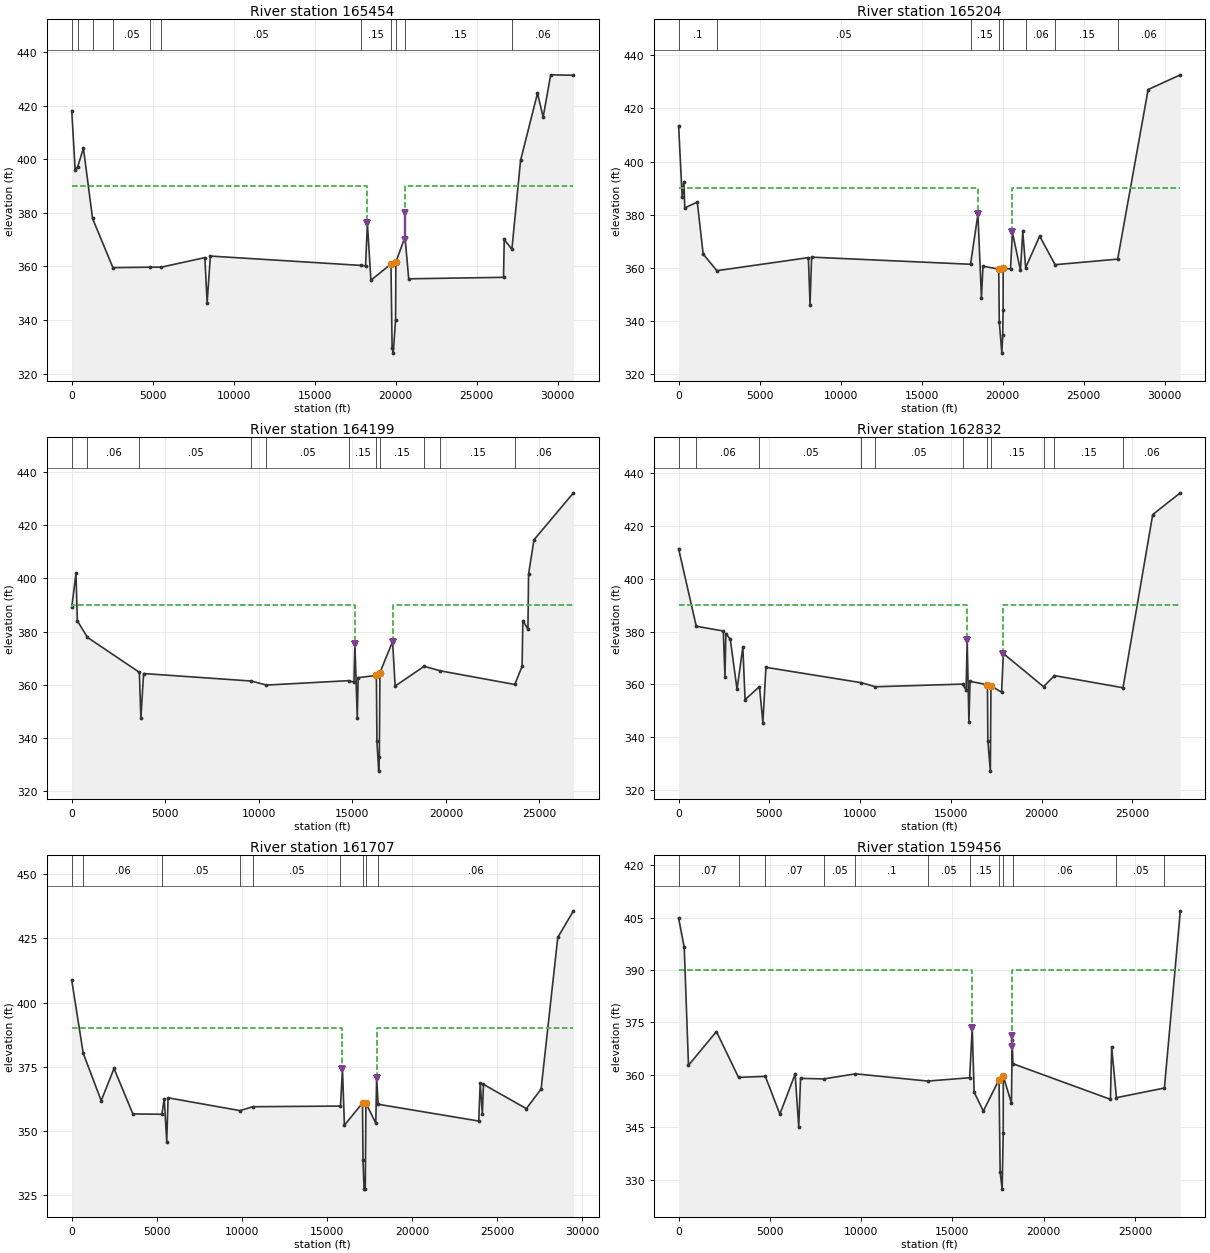
Type RM Length L Ch R = 1 ,165454  ,224.76,250.22,261.43
BEGIN DESCRIPTION:
US Bridge
LOB - Bois D'Arc, ROB - Dallas LID1/2
END DESCRIPTION:
XS GIS Cut Line= 6
2571064.517439086919575.161277432566003.753550186914334.01544409
2565110.003550176912511.793221862558975.281327946906277.24461073
2555912.086883486905121.68905517 2547692.46882796900176.72377738
#Sta/Elev= 30
       0  418.17  211.42  395.93  370.27  397.26  720.46  404.15 1284.49  377.89
 2541.58  359.53 4832.33  359.715517.479  359.718214.539  363.28 8355.23  346.47
 8555.71  363.8617874.37  360.36 18132.3  360.19 18246.3  376.0918463.09  354.82
19701.56   360.9 19770.9 329.645 19839.7 327.61719985.68  340.0420003.09  361.65
20568.99  370.9820795.05  355.3726647.99  355.9326690.77  370.0627164.25  366.42
   27700  399.6128744.54  424.6729092.81  415.7529559.32  431.5430964.49  431.37
#Mann= 11 ,-1 , 0
       0      .1       0  370.27     .07       0 1284.49      .1       0
 2541.58     .05       0 4832.33      .1       05517.479     .05       0
17874.37     .15       019701.56    .055       020003.09     .15       0
20568.99     .15       027164.25     .06       0
Levee=-1,18246.3,376.09,-1,20585.91,380,,
#XS Ineff= 2 ,-1
       0 18246.3     39020585.9130964.49     390
Permanent Ineff=
       F       F
Bank Sta=19701.56,20003.09
XS Rating Curve= 0 ,0
Exp/Cntr=0.5,0.3

Type RM Length L Ch R = 1 ,165204  ,2833.82,1004.45,1013.94
BEGIN DESCRIPTION:
DS Bridge
LOB - Bois D'Arc, ROB - Dallas LID1/2
END DESCRIPTION:
XS GIS Cut Line= 6
2571148.471632786919340.467399712566087.707743886914099.32156637
2565193.957743886912277.099344142559059.235521646906042.55073301
2555996.041077196904886.995177452547776.423021616899942.02989966
#Sta/Elev= 30
       0  413.48  221.23  386.66  325.28  392.45  381.49  382.53 1152.41  384.78
 1514.88  365.17 2364.41  358.93 8009.12  363.85 8110.32  346.16 8208.18  364.03
18015.71  361.3518473.14  380.1618689.36  348.7918785.87   360.619757.48  359.53
19790.41   339.7 19948.8 327.90720003.44 334.86320025.39  344.1720031.36  359.91
20484.38  359.5520599.72  373.3721096.56  359.0721240.92  373.6921417.91   360.1
   22285  371.9423235.21  361.1927098.06  363.2828976.79   427.1 30964.4  432.64
#Mann= 8 ,-1 , 0
       0      .1       0 2364.41     .05       018015.71     .15       0
19757.48    .055       020031.36     .15       021417.91     .06       0
23235.21     .15       027098.06     .06       0
Levee=-1,18473.14,380.16,-1,20599.72,373.37,,
#XS Ineff= 2 ,-1
       018473.14     39020599.72 30964.4     390
Permanent Ineff=
       F       F
Bank Sta=19757.48,20031.36
XS Rating Curve= 0 ,0
Exp/Cntr=0.5,0.3

Type RM Length L Ch R = 1 ,164199  ,1428.2,1367.21,1058.58
BEGIN DESCRIPTION:
LOB - Bois D'Arc, ROB - Dallas LID1/2
END DESCRIPTION:
XS GIS Cut Line= 4
2572565.59443196 6911360.62073692559008.077070836904842.65198688
2557098.354848616904203.763097992548372.084459926899827.39656934
#Sta/Elev= 30
       0  389.12  224.44  401.91   299.2  384.07  838.45  377.86 3614.19   364.7
 3694.54   347.4 3840.79  364.24 9599.25  361.4210407.14   359.914797.07  361.56
15084.37     36115135.94  375.3115261.81  347.5815310.66  362.6816284.31  363.55
16312.96  338.6816407.93  327.5316441.75  332.9916473.03  364.6117150.04  376.29
17287.03  359.5318838.98  366.9719705.71  365.2523681.46  360.1224072.29  366.94
24113.22  384.1624385.24  380.9324418.55  401.6124708.18  414.55 26818.9  432.22
#Mann= 11 ,-1 , 0
       0     .07       0  838.45     .06       0 3614.19     .05       0
 9599.25      .1       010407.14     .05       014797.07     .15       0
16284.31    .055       016473.03     .15       018838.98     .06       0
19705.71     .15       023681.46     .06       0
Levee=-1,15135.94,375.31,-1,17150.04,376.29,,
#XS Ineff= 2 ,-1
       015135.94     39017150.04 26818.9     390
Permanent Ineff=
       F       F
Bank Sta=16284.31,16473.03
XS Rating Curve= 0 ,0
Exp/Cntr=0.3,0.1

Type RM Length L Ch R = 1 ,162832  ,930.2,1125.12,1407.97
BEGIN DESCRIPTION:
LOB - Bois D'Arc, ROB - Dallas LID1/2
END DESCRIPTION:
XS GIS Cut Line= 4
2573672.057226476910324.489491232559342.144032026903463.29157455
2557416.102365356902900.791574552548203.307226456899716.85060233
#Sta/Elev= 30
       0  411.45  972.85  382.03 2460.75  380.24 2553.94  362.85 2600.63  379.25
 2848.45  377.07 3218.18  358.12 3539.16   374.1 3661.86  354.22 4454.66  359.13
 4643.12  345.45 4809.96  366.4510064.97  360.6210841.67  359.0815640.54  360.09
 15836.7  357.9115899.03  376.7915994.62  345.6716055.16  361.1517016.16  359.83
17037.44  338.4917175.73  327.0817207.69  359.4217793.92  357.0317892.38  371.69
20104.77  359.1220707.46  363.3224483.67   358.726120.06   424.427641.74  432.64
#Mann= 11 ,-1 , 0
       0     .07       0  972.85     .06       0 4454.66     .05       0
10064.97      .1       010841.67     .05       015640.54     .15       0
17016.16    .055       017207.69     .15       020104.77     .06       0
20707.46     .15       024483.67     .06       0
Levee=-1,15899.03,376.79,-1,17892.38,371.69,,
#XS Ineff= 2 ,-1
       015899.03     39017892.3827641.74     390
Permanent Ineff=
       F       F
Bank Sta=17016.16,17207.69
XS Rating Curve= 0 ,0
Exp/Cntr=0.3,0.1

Type RM Length L Ch R = 1 ,161707  ,1287.44,2251.17,2226.65
BEGIN DESCRIPTION:
LOB - Bois D'Arc, ROB - Dallas LID1/2
END DESCRIPTION:
XS GIS Cut Line= 4
 2573919.27944876909528.308935682559622.057226476902553.30893567
2557775.182226466901729.35060234 2547235.25167096896976.22560234
#Sta/Elev= 30
       0  408.66  673.33  380.22 1730.72  361.68 2484.87  374.25 3593.53   356.5
  5294.1  356.39 5435.28  362.36 5583.78  345.73 5662.01  362.81 9889.96   357.8
10646.13  359.3315796.61  359.5815913.21  374.1116027.77  352.1317091.24  360.75
17121.09  338.5217183.35  327.1617253.35  327.1617293.04  360.6817871.87  352.93
17921.79  370.6318010.71  360.2923925.79  353.7324009.32  368.6724137.73  356.47
24200.98  368.0426724.05  358.5927590.31  366.2428570.23  425.41 29492.4  435.79
#Mann= 9 ,-1 , 0
       0     .07       0  673.33     .06       0  5294.1     .05       0
 9889.96      .1       010646.13     .05       015796.61     .15       0
17091.24    .055       017293.04     .15       018010.71     .06       0
Levee=-1,15913.21,374.11,-1,17921.79,370.63,,
#XS Ineff= 2 ,-1
       015913.21     39017921.79 29492.4     390
Permanent Ineff=
       F       F
Bank Sta=17091.24,17293.04
XS Rating Curve= 0 ,0
Exp/Cntr=0.3,0.1

Type RM Length L Ch R = 1 ,159456  ,1796.97,2111.7,856.13
BEGIN DESCRIPTION:
LOB - Bois D'Arc, ROB - Dallas LID1/2
END DESCRIPTION:
XS GIS Cut Line= 4
2574022.578059816909063.899213462559391.791022766900614.24643568
2558348.966948696899676.746435672550237.855837576895365.98254678
#Sta/Elev= 30
       0  404.85   307.8  396.52  540.76  362.74 2072.69   372.4  3282.1  359.26
 4750.08  359.57  5546.9  348.75 6383.02  360.23 6580.04  345.05  6680.2  358.99
  7953.6  358.83 9688.69  360.2913642.18  358.2115942.82  359.1716083.73  373.43
16189.08  355.0216691.93  349.6317550.99  358.5817613.52  332.1917722.64  327.26
17780.74  343.2917786.32  359.6118232.31  351.8818272.77  369.9518310.25  363.19
23654.16  352.9823722.66  367.87 23983.2  353.4626610.13  356.2227483.23  406.98
#Mann= 12 ,-1 , 0
       0     .07       0  3282.1     .06       0 4750.08     .07       0
  7953.6     .05       0 9688.69      .1       013642.18     .05       0
15942.82     .15       017550.99    .055       017786.32     .15       0
18310.25     .06       0 23983.2     .05       026610.13     .06       0
Levee=-1,16083.73,373.43,-1,18283.99,371.07,,
#XS Ineff= 2 ,-1
       016083.73     39018283.9927483.23     390
Permanent Ineff=
       F       F
Bank Sta=17550.99,17786.32
XS Rating Curve= 0 ,0
Exp/Cntr=0.3,0.1