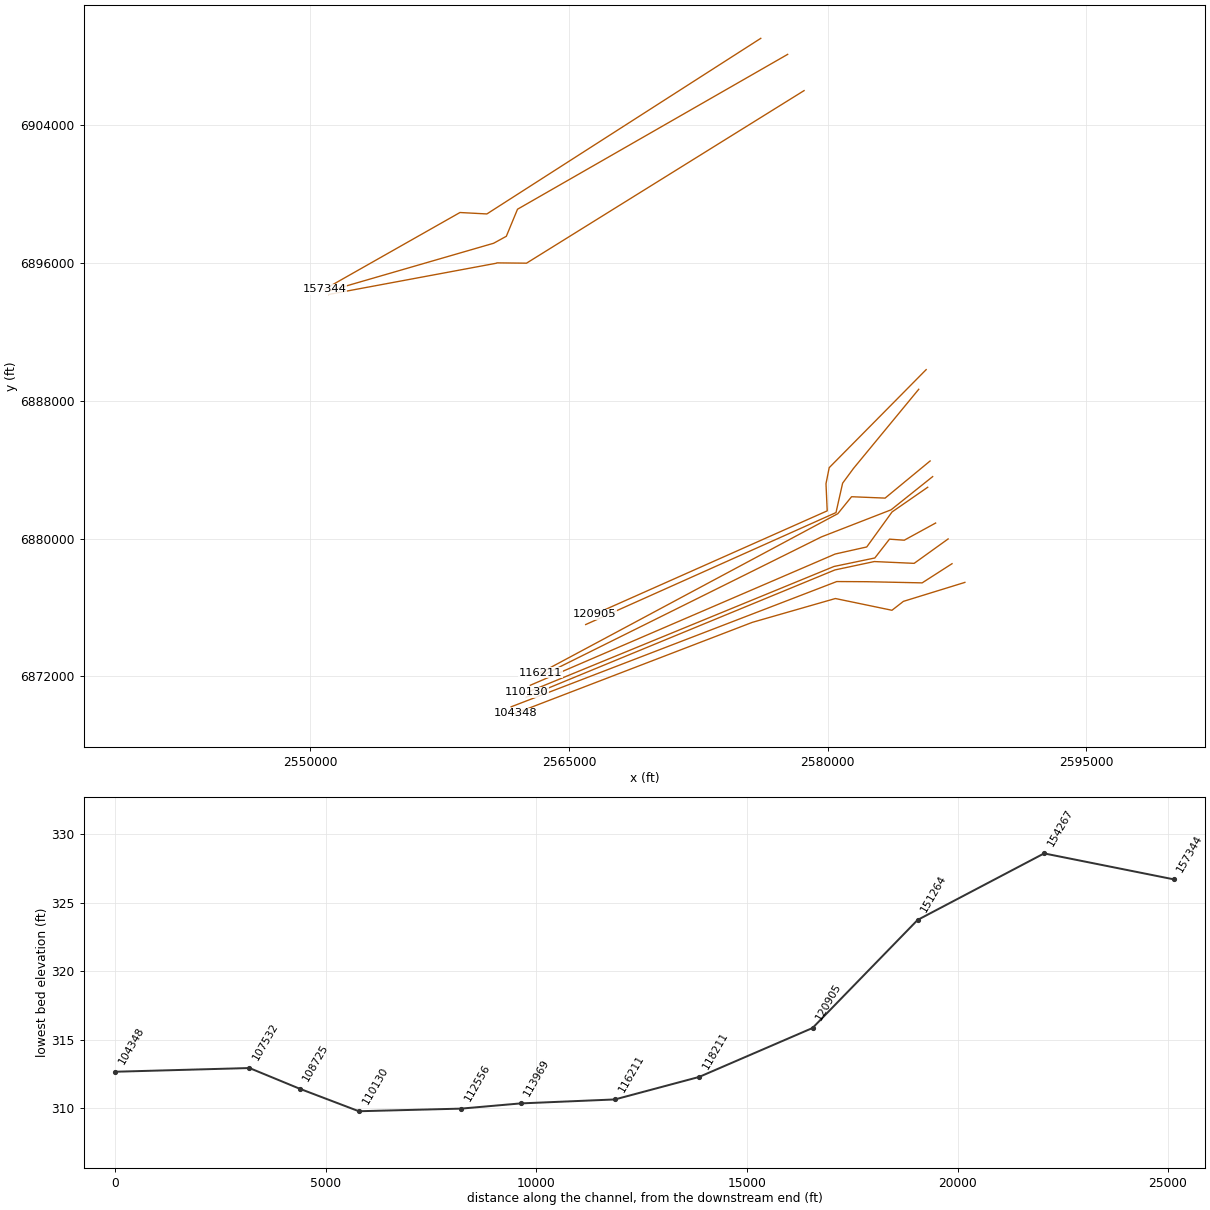
HEC-RAS study TR_FEMA.prj: Trinity_River_FEMA

--- TR_FEMA.g01 (geometry) --- (continued)

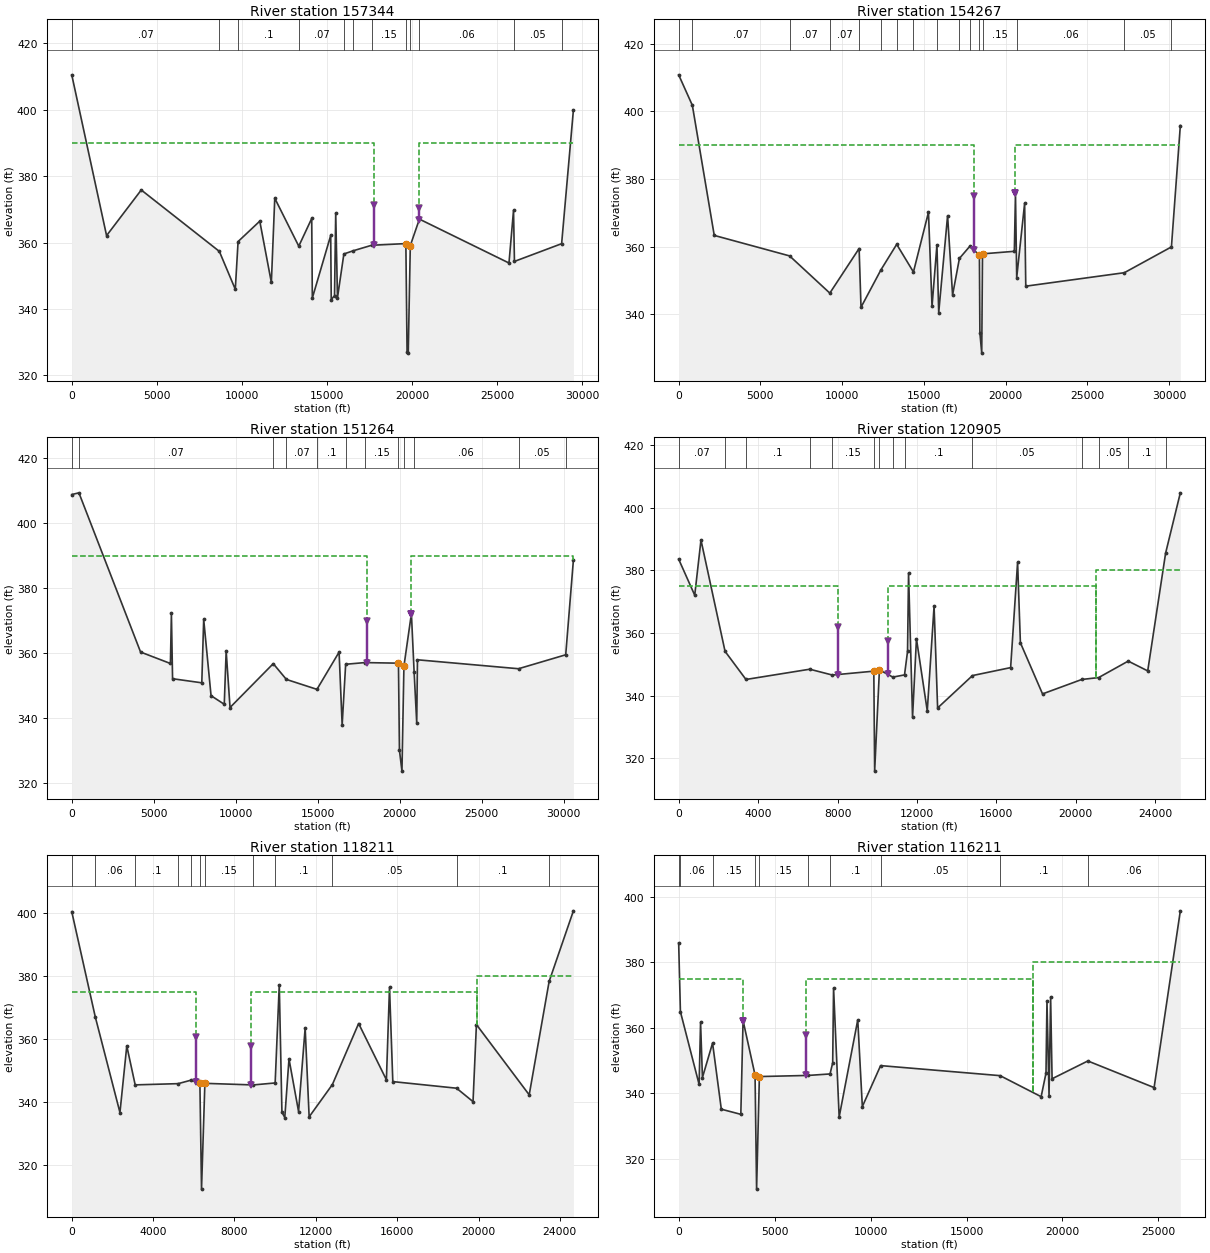
Type RM Length L Ch R = 1 ,157344  ,948.05,3077.14,2486.59
BEGIN DESCRIPTION:
LOB - Bois D'Arc, ROB - Dallas LID1/2
END DESCRIPTION:
XS GIS Cut Line= 4
2576124.256300566909043.413102352560240.402133886898849.66310234
2558682.068800546898932.996435672550808.120060356894467.16161053
#Sta/Elev= 30
       0  410.53 2046.93  362.09 4085.18  375.84 8675.15  357.34 9612.65  345.92
 9776.27   360.311051.82  366.4511732.16  347.9811932.42  373.3613343.42  358.91
14104.43  367.2614140.35  343.2815220.16  362.1415252.47  342.7815444.82  344.04
   15515   368.915619.05  343.3915994.19  356.5616544.95  357.5317624.69  359.18
19638.15  359.6919708.99  327.0119777.38  326.6919898.87  359.0920434.58  367.06
 25698.6  353.8425966.05  369.68 26020.1  354.3228793.51  359.66 29486.2  399.98
#Mann= 12 ,-1 , 0
       0     .07       0 8675.15     .07       0 9776.27      .1       0
13343.42     .07       015994.19     .05       016544.95     .07       0
17624.69     .15       019638.15    .055       019898.87     .15       0
20434.58     .06       0 26020.1     .05       028793.51     .06       0
Levee=-1,17774.12,371.28,-1,20414.93,370.51,,
#XS Ineff= 2 ,-1
       017774.15     39020414.93 29486.2     390
Permanent Ineff=
       F       F
Bank Sta=19638.15,19898.87
XS Rating Curve= 0 ,0
Exp/Cntr=0.3,0.1

Type RM Length L Ch R = 1 ,154267  ,2928.63,3003.32,1020.6
BEGIN DESCRIPTION:
LOB - Bois D'Arc, ROB - Dallas LID1/2
END DESCRIPTION:
XS GIS Cut Line= 5
2577683.119930486908112.994882482562017.311695226899122.99645831
2561369.395340146897553.204650392560632.806918296897148.53059098
2550948.498531046894340.13036789
#Sta/Elev= 30
       0   410.8  837.14  401.79 2176.36  363.36 6785.31   357.3 9245.48  346.31
11036.79  359.4911152.87  342.1312375.82  353.2213335.26  360.7214359.38  352.55
15278.67  370.1915496.36  342.3815796.75  360.5815905.35  340.5616448.28  369.19
 16753.2  345.7617172.32  356.5717799.81   360.118394.04  357.59 18423.7  334.59
18536.48  328.5818584.13  357.9120530.15  358.6620600.43  375.7620675.41  350.89
21160.32  372.8521230.31  348.3627259.18  352.3430138.64  359.9630683.54  395.82
#Mann= 16 ,-1 , 0
       0     .07       0  837.14     .07       0 6785.31     .07       0
 9245.48     .07       011036.79      .1       012375.82     .07       0
13335.26      .1       014359.38     .07       015796.75      .1       0
17172.32     .07       017799.81     .15       018394.04    .055       0
18584.13     .15       020675.41     .06       027259.18     .05       0
30138.64     .06       0
Levee=-1,18057.04,375.03,-1,20600.43,375.76,,
#XS Ineff= 2 ,-1
       018057.04     39020600.4330683.54     390
Permanent Ineff=
       F       F
Bank Sta=18394.04,18584.13
XS Rating Curve= 0 ,0
Exp/Cntr=0.3,0.1

Type RM Length L Ch R = 1 ,151264  ,621.55,2495.98,3306.68
BEGIN DESCRIPTION:
LOB - Bois D'Arc, ROB - Dallas LID1/2
END DESCRIPTION:
XS GIS Cut Line= 5
 2578634.50910386906008.828159062562540.853627156895992.51026523
2560824.186784896896009.176898552560782.641592386895987.49255873
2551073.515013316894178.02144015
#Sta/Elev= 30
       0  408.76  437.28  409.29 4197.57  360.34 6017.73  356.82 6077.77   372.2
 6148.51  352.14 7931.23  350.88 8046.75  370.36 8495.57  346.93  9301.6  344.28
 9417.25  360.68 9653.25  343.2912288.91  356.7713090.76  351.9214954.12  348.87
16304.17  360.3216491.45  337.9316705.35  356.5817869.34   357.119925.13  356.92
19985.24  330.1520138.63  323.7320258.42  355.9620714.75  372.1520879.38  354.32
21039.31  338.5921084.29  357.9627246.89  355.2130125.76   359.530595.58  388.68
#Mann= 12 ,-1 , 0
       0     .07       0  437.28     .07       012288.91      .1       0
13090.76     .07       014954.12      .1       016705.35     .07       0
17869.34     .15       019925.13    .055       020258.42     .15       0
20879.38     .06       027246.89     .05       030125.76     .06       0
Levee=-1,17986.26,369.76,-1,20714.75,372.15,,
#XS Ineff= 2 ,-1
       017986.26     39020714.7530595.58     390
Permanent Ineff=
       F       F
Bank Sta=19925.13,20258.42
XS Rating Curve= 0 ,0
Exp/Cntr=0.3,0.1

Type RM Length L Ch R = 1 ,120905  ,976.82,2694.7,313.19
BEGIN DESCRIPTION:
LOB - Bois D'Arc, ROB - Dallas LID14/Ellis LID3
ROB IFA station 21033: flow expansion due to natural high ground upstream
END DESCRIPTION:
XS GIS Cut Line= 5
2585714.392295936889812.555174092580091.614518156884120.88850743
2579906.058962596883189.013507422579976.886508896881615.51235001
2566509.960937216875623.12996538
#Sta/Elev= 30
       0  383.56  808.93  372.05 1123.59  389.67 2336.29  354.12 3389.41  345.13
 6601.08  348.41 7738.89  346.55 9828.58  347.79 9870.55  315.8510110.79   348.2
10786.36  345.8911374.55  346.5911527.09   354.111578.13  379.0811778.86  333.04
11975.94  358.1412520.65  335.1112863.31  368.5313041.78  336.0314797.73  346.38
16718.92  348.9217069.88  382.5617210.52  356.8618325.61  340.5220301.79  345.13
 21151.2  345.7422641.51     35123623.41  347.87 24524.3  385.4925265.88  404.76
#Mann= 14 ,-1 , 0
       0     .07       0 2336.29     .06       0 3389.41      .1       0
 6601.08     .06       0 7738.89     .15       0 9828.58    .055       0
10110.79     .15       010786.36     .05       011374.55      .1       0
14797.73     .05       020301.79      .1       0 21151.2     .05       0
22641.51      .1       0 24524.3     .06       0
Levee=-1,8005.69,361.93,-1,10526.72,357.49,,
#XS Ineff= 3 ,-1
       0 8005.69     37510526.72   21033     375   2103325265.88     380
Permanent Ineff=
       F       F       F
Bank Sta=9828.58,10110.79
XS Rating Curve= 0 ,0
Exp/Cntr=0.3,0.1

Type RM Length L Ch R = 1 ,118211  ,2761.13,1999.76,334.75
BEGIN DESCRIPTION:
LOB - Bois D'Arc, ROB - Dallas LID14/Ellis LID3
ROB IFA station 19915: flow expansion due to natural high ground upstream
END DESCRIPTION:
XS GIS Cut Line= 5
2585283.489518156888671.588738912581496.568221856884073.32485001
2580869.947851486883221.472998162580486.151555196881514.99151668
2565971.766492776875015.49107649
#Sta/Elev= 30
       0  400.54 1155.44   367.1 2369.85  336.65 2705.98  357.83 3119.07  345.44
  5232.5  345.83    5850  346.91 6300.75  345.99 6380.81  312.28 6546.02  345.93
 8921.03  345.42 10001.1  346.0510203.83  377.2710334.41  336.7610474.72  335.05
10681.82   353.711152.35  336.9611476.65  363.5511672.77  335.2712815.94  345.55
14105.39  364.9615471.42  347.0615624.14  376.4715786.65  346.4818921.67  344.38
19730.73  340.11 19897.3  364.6322492.53  342.2723472.56  378.3424666.69   400.8
#Mann= 12 ,-1 , 0
       0     .07       0 1155.44     .06       0 3119.07      .1       0
  5232.5     .06       0    5850     .15       0 6300.75    .055       0
 6546.02     .15       0 8921.03     .05       0 10001.1      .1       0
12815.94     .05       018921.67      .1       023472.56     .06       0
Levee=-1,6113.49,360.77,-1,8803.29,357.77,,
#XS Ineff= 3 ,-1
       0 6090.96     375 8803.29   19915     375   1991524666.69     380
Permanent Ineff=
       F       F       F
Bank Sta=6300.75,6546.02
XS Rating Curve= 0 ,0
Exp/Cntr=0.3,0.1

Type RM Length L Ch R = 1 ,116211  ,785.21,2241.73,739.29
BEGIN DESCRIPTION:
LOB - Bois D'Arc, ROB - Dallas LID14/Ellis LID3
ROB IFA station 18461: flow expansion due to natural high ground upstream
END DESCRIPTION:
XS GIS Cut Line= 5
     2585944.032     6884510.862     2583333.374     6882355.269
     2581389.228     6882435.162     2580590.329     6881450.457
       2563367.6     6872220.352
#Sta/Elev= 30
       0  385.96   91.21  364.89 1065.04  342.66 1141.18  361.61 1238.75  344.76
 1766.31   355.3 2221.93  335.08 3238.73  333.51  3355.6  362.19 3980.32  345.52
 4060.59  310.64 4205.73  345.06    6757  345.41  7887.7  345.86 8025.89  349.25
 8071.31  372.13 8363.02   332.7 9331.79   362.4 9570.76  335.8810522.81  348.41
   16749  345.3418887.42  338.9119140.57   346.119191.16  368.1219299.06  339.21
19381.64  369.3819457.52  344.3921321.25  349.8324773.52  341.6926140.52  395.74
#Mann= 10 ,-1 , 0
       0     .06       0   91.21     .06       0 1766.31     .15       0
 3980.32    .055       0 4205.73     .15       0    6757     .05       0
  7887.7      .1       010522.81     .05       0   16749      .1       0
21321.25     .06       0
Levee=-1,3355.6,362.19,-1,6627.08,357.69,,
#XS Ineff= 3 ,-1
       0  3355.6     375 6627.09   18461     375   1846126140.52     380
Permanent Ineff=
       F       F       F
Bank Sta=3980.32,4205.73
XS Rating Curve= 0 ,0
Exp/Cntr=0.3,0.1

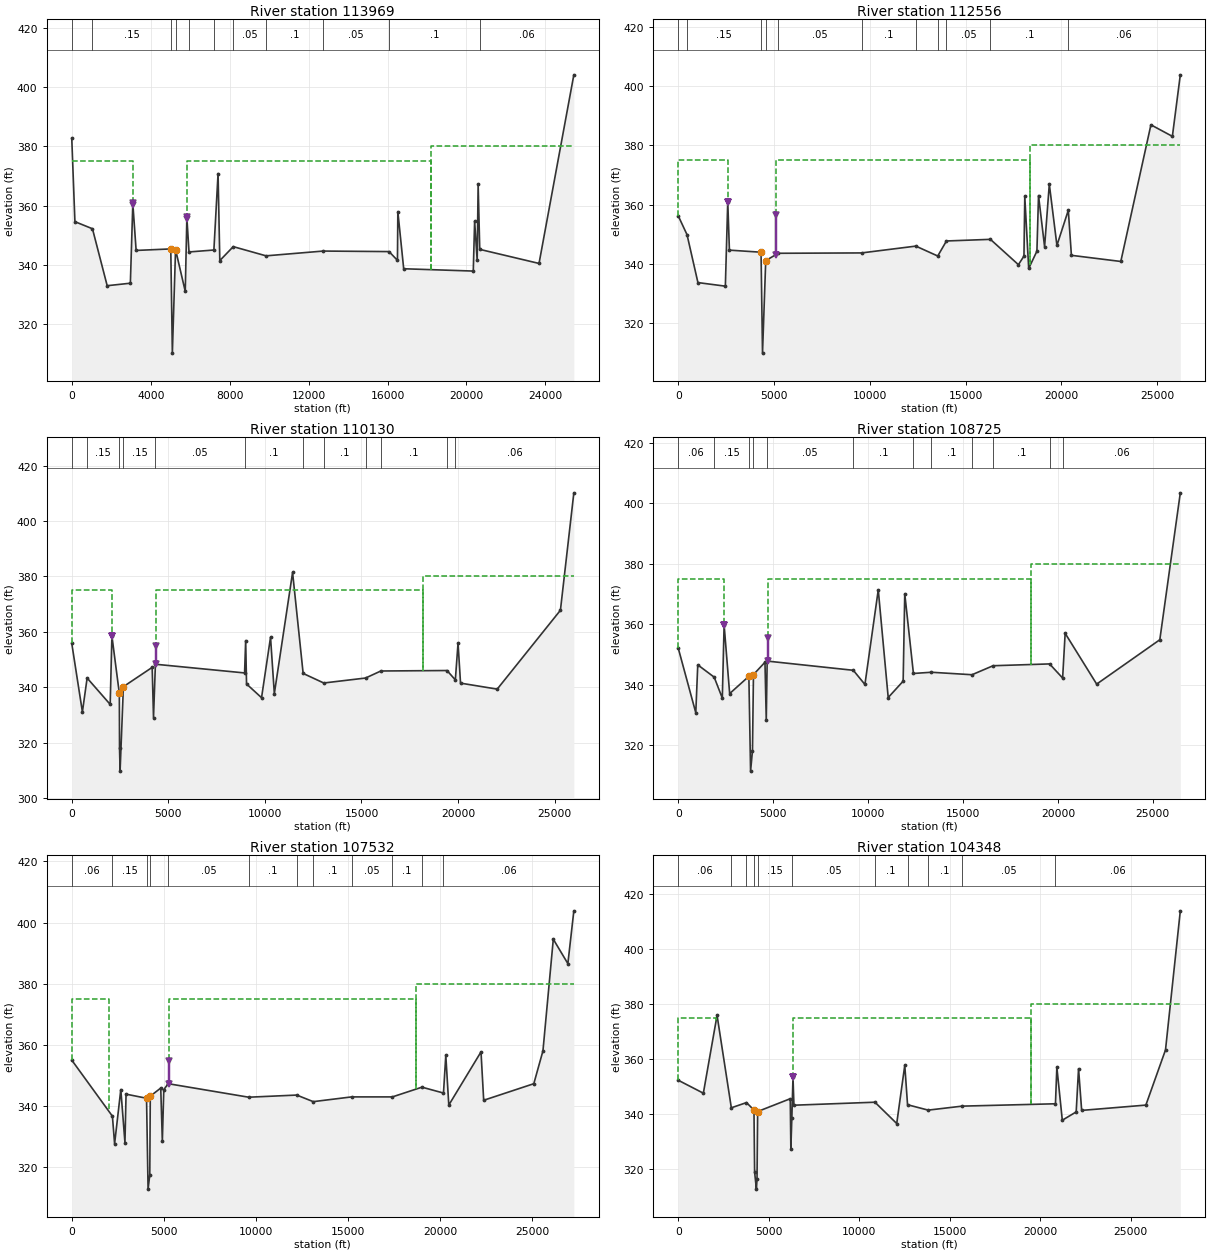
Type RM Length L Ch R = 1 ,113969  ,147.93,1413.33,1346.26
BEGIN DESCRIPTION:
LOB - Bois D'Arc, ROB - Dallas LID14/Ellis LID3
ROB IFA station 18189: flow expansion due to natural high ground upstream
END DESCRIPTION:
XS GIS Cut Line= 4
     2586091.755     6883602.693      2583678.94     6881674.698
     2579642.858     6880103.664     2563506.489     6872081.463
#Sta/Elev= 30
       0  382.66   159.6  354.63  1048.5  352.24 1794.21  333.06 2969.13   333.9
  3093.5  360.77 3261.33  344.94 5016.81  345.45 5096.83  310.35 5258.88  345.24
 5750.62  331.14 5831.83  356.07  5940.4  344.43 7201.38  345.08 7412.86  370.84
 7501.14  341.52 8182.78  346.22 9844.37  343.1212740.14  344.7316078.38  344.55
16502.85   341.616522.41  358.0216819.29  338.7720344.84  337.9920413.57  354.79
 20542.7   341.620591.31  367.2820672.55   345.323676.91  340.5625440.86  404.09
#Mann= 11 ,-1 , 0
       0     .06       0  1048.5     .15       0 5016.81    .055       0
 5258.88     .15       0  5940.4     .05       0 7201.38      .1       0
 8182.78     .05       0 9844.37      .1       012740.14     .05       0
16078.38      .1       020672.55     .06       0
Levee=-1,3098.5,360.77,-1,5836.82,356.19,,
#XS Ineff= 3 ,-1
       0  3098.5     375 5837.07   18189     375   1818925440.86     380
Permanent Ineff=
       F       F       F
Bank Sta=5016.81,5258.88
XS Rating Curve= 0 ,0
Exp/Cntr=0.3,0.1

Type RM Length L Ch R = 1 ,112556  ,1808.05,2425.98,739.38
BEGIN DESCRIPTION:
LOB - Bois D'Arc, ROB - Dallas LID14/Ellis LID3
ROB IFA station 18373: flow expansion due to natural high ground upstream
END DESCRIPTION:
XS GIS Cut Line= 5
       2585804.9     6882984.953     2583737.924     6881552.473
     2582268.896     6879518.792     2580440.598     6879109.695
     2562759.961     6871491.186
#Sta/Elev= 30
       0  356.27   458.5  349.92 1027.81  333.76 2459.89  332.55 2584.82  361.08
 2671.59   344.7 4322.59     344 4399.32  309.97 4567.55  341.17 5218.84  343.64
 9568.96  343.7612403.64  346.0613546.54  342.7214001.42  347.7916296.95  348.34
17757.01   339.818047.48  342.6918090.18  362.7918294.91  338.5318723.42  344.35
18807.48  363.1219124.28  345.8519370.51  366.9519768.17  346.2920362.28  358.15
20523.92  342.9523102.89  340.8824674.92  386.9625794.75  383.0726209.19  403.82
#Mann= 11 ,-1 , 0
       0     .06       0   458.5     .15       0 4322.59    .055       0
 4567.55     .15       0 5218.84     .05       0 9568.96      .1       0
12403.64     .05       013546.54      .1       014001.42     .05       0
16296.95      .1       020362.28     .06       0
Levee=-1,2584.82,361.08,-1,5083.59,356.56,,
#XS Ineff= 3 ,-1
       0 2584.82     375 5083.57   18373     375   1837326209.19     380
Permanent Ineff=
       F       F       F
Bank Sta=4322.59,4567.55
XS Rating Curve= 0 ,0
Exp/Cntr=0.3,0.1

Type RM Length L Ch R = 1 ,110130  ,1466.65,1404.73,264.23
BEGIN DESCRIPTION:
LOB - Bois D'Arc, ROB - Dallas LID14/Ellis LID3
ROB IFA station 18172: flow expansion due to natural high ground upstream
END DESCRIPTION:
XS GIS Cut Line= 6
     2586262.889     6880907.974     2584444.605     6879911.516
     2583586.604     6879971.917     2582737.646     6878879.903
      2580370.91       6878386.5     2562568.989     6871074.519
#Sta/Elev= 30
       0  355.84  550.58  331.14  795.01  343.36 1988.81  333.85 2078.42   358.5
 2462.45  337.85 2472.91  318.02 2501.58  309.78 2673.18  340.25 4162.76   347.2
 4231.97   329.1 4330.13  348.34 8947.24   345.2 9003.47  356.86 9048.75  341.22
 9825.57  336.2710290.49  358.0610487.69  337.7411432.32  381.4411979.33  345.02
13046.22  341.5715210.35  343.3616001.13   345.919427.69  346.0719858.94  342.69
19999.03  355.9420127.81  341.5222026.83  339.3625299.58  367.8125994.54  410.17
#Mann= 12 ,-1 , 0
       0     .06       0  795.01     .15       0 2462.45    .055       0
 2673.18     .15       0 4330.13     .05       0 8947.24      .1       0
11979.33     .05       013046.22      .1       015210.35     .05       0
16001.13      .1       019427.69     .05       019858.94     .06       0
Levee=-1,2078.42,358.5,-1,4345.46,354.96,,
#XS Ineff= 3 ,-1
       0 2078.42     375 4345.07   18172     375   1817225994.54     380
Permanent Ineff=
       F       F       F
Bank Sta=2462.45,2673.18
XS Rating Curve= 0 ,0
Exp/Cntr=0.3,0.1

Type RM Length L Ch R = 1 ,108725  ,1186.89,1193.33,695.83
BEGIN DESCRIPTION:
LOB - Bois D'Arc, ROB - Dallas LID14/Ellis LID3
ROB IFA station 18591: flow expansion due to natural high ground upstream
END DESCRIPTION:
XS GIS Cut Line= 5
     2586988.651     6879984.728     2585018.827      6878567.75
     2582706.327     6878671.917     2580424.382     6878185.459
     2562516.905     6870796.741
#Sta/Elev= 30
       0  352.13  924.84  330.74 1028.29  346.59 1893.33  342.52    2322  335.58
 2416.54  359.83  2708.8  337.08 3721.05  342.79  3811.2  311.42 3911.73  318.19
 3962.76  343.37 4569.42  347.46 4637.55  328.23 4684.98  347.84 9222.72  344.79
 9834.86   340.110537.58  371.4111061.39  335.7811848.95  341.1911932.97  370.14
 12390.1  343.7413336.15  344.1415477.19  343.3216586.04   346.319563.45   346.9
20250.32  342.2220382.85  357.0322043.72  340.2225369.97   354.926449.92  403.52
#Mann= 12 ,-1 , 0
       0     .06       0 1893.33     .15       0 3721.05    .055       0
 3962.76     .15       0 4684.98     .05       0 9222.72      .1       0
 12390.1     .05       013336.15      .1       015477.19     .05       0
16586.04      .1       019563.45     .05       020250.32     .06       0
Levee=-1,2416.54,359.83,-1,4719.96,355.32,,
#XS Ineff= 3 ,-1
       0 2416.54     375 4720.04   18591     375   1859126449.92     380
Permanent Ineff=
       F       F       F
Bank Sta=3721.05,3962.76
XS Rating Curve= 0 ,0
Exp/Cntr=0.3,0.1

Type RM Length L Ch R = 1 ,107532  ,1037.27,3183.75,659.24
BEGIN DESCRIPTION:
ROB - Dallas LID14/Ellis LID3
LOB IFA station 2008: flow expansion due to Bois D'Arc levee upstream
ROB IFA station 18676: flow expansion due to natural high ground upstream
END DESCRIPTION:
XS GIS Cut Line= 5
     2587214.015     6878546.995     2585482.484     6877434.648
     2582272.183     6877502.519     2580529.243     6877510.806
      2561648.85     6870241.186
#Sta/Elev= 30
       0  355.06  2206.6  336.75 2324.95  327.73 2661.98  345.45 2886.92  328.11
 2946.88  343.95 4058.67  342.61 4141.97  312.93 4234.63  317.57 4262.58  343.29
 4830.06  345.94 4916.76   328.6  4995.3  345.38 5229.58  347.37 9602.06  342.95
12212.69  343.6513108.48   341.515191.19  343.0517405.58  343.05 19010.2  346.23
20178.41  344.3120304.07  356.6320466.76  340.3822215.42  357.75 22361.1  341.95
25081.37  347.3625577.96  358.0826139.72  394.5526930.64  386.5827255.17  403.82
#Mann= 12 ,-1 , 0
       0     .06       0  2206.6     .15       0 4058.67    .055       0
 4262.58     .15       0 5229.58     .05       0 9602.06      .1       0
12212.69     .05       013108.48      .1       015191.19     .05       0
17405.58      .1       0 19010.2     .05       020178.41     .06       0
Levee=0,,,-1,5263.36,354.63,,
#XS Ineff= 3 ,-1
       0    2008     375 5263.37   18676     375   1867627255.17     380
Permanent Ineff=
       F       F       F
Bank Sta=4058.67,4262.58
XS Rating Curve= 0 ,0
Exp/Cntr=0.3,0.1

Type RM Length L Ch R = 1 ,104348  ,1720.81,8083.46,4276.21
BEGIN DESCRIPTION:
ROB - Dallas LID14/Ellis LID3
LOB IFA station 2091: flow blocked at natural high ground
ROB IFA station 19491: flow expansion due to natural high ground upstream
END DESCRIPTION:
XS GIS Cut Line= 6
     2587959.751      6877462.12     2584395.378     6876361.093
      2583731.07     6875844.172     2580450.933     6876525.908
      2575638.85     6875144.808     2561891.905     6869859.241
#Sta/Elev= 30
       0  352.26 1387.58  347.55 2144.66  375.87 2932.52  342.24 3769.51  344.13
  4183.4  341.42 4218.77  318.86 4317.71  312.66 4351.15  316.23 4386.78  340.88
 6187.54  345.54 6220.33  327.42 6275.76  338.64 6339.09  353.48 6389.68  343.18
 10865.3  344.2712068.66  336.5212513.24   357.712666.27  343.3513806.08  341.39
15676.84  342.8420836.46   343.720913.16  356.9821214.51  337.7221981.43  340.74
22111.55  356.4622284.05  341.2925829.78  343.2226914.69  363.28 27732.7  413.87
#Mann= 11 ,-1 , 0
       0     .06       0 2932.52     .06       0 3769.51     .15       0
  4183.4    .055       0 4386.78     .15       0 6275.76     .05       0
 10865.3      .1       012666.27     .05       013806.08      .1       0
15676.84     .05       020836.46     .06       0
Levee=0,,,-1,6339.09,353.48,,
#XS Ineff= 3 ,-1
       0    2091     375 6338.03   19491     375   19491 27732.7     380
Permanent Ineff=
       F       F       F
Bank Sta=4183.4,4386.78
XS Rating Curve= 0 ,0
Exp/Cntr=0.3,0.1