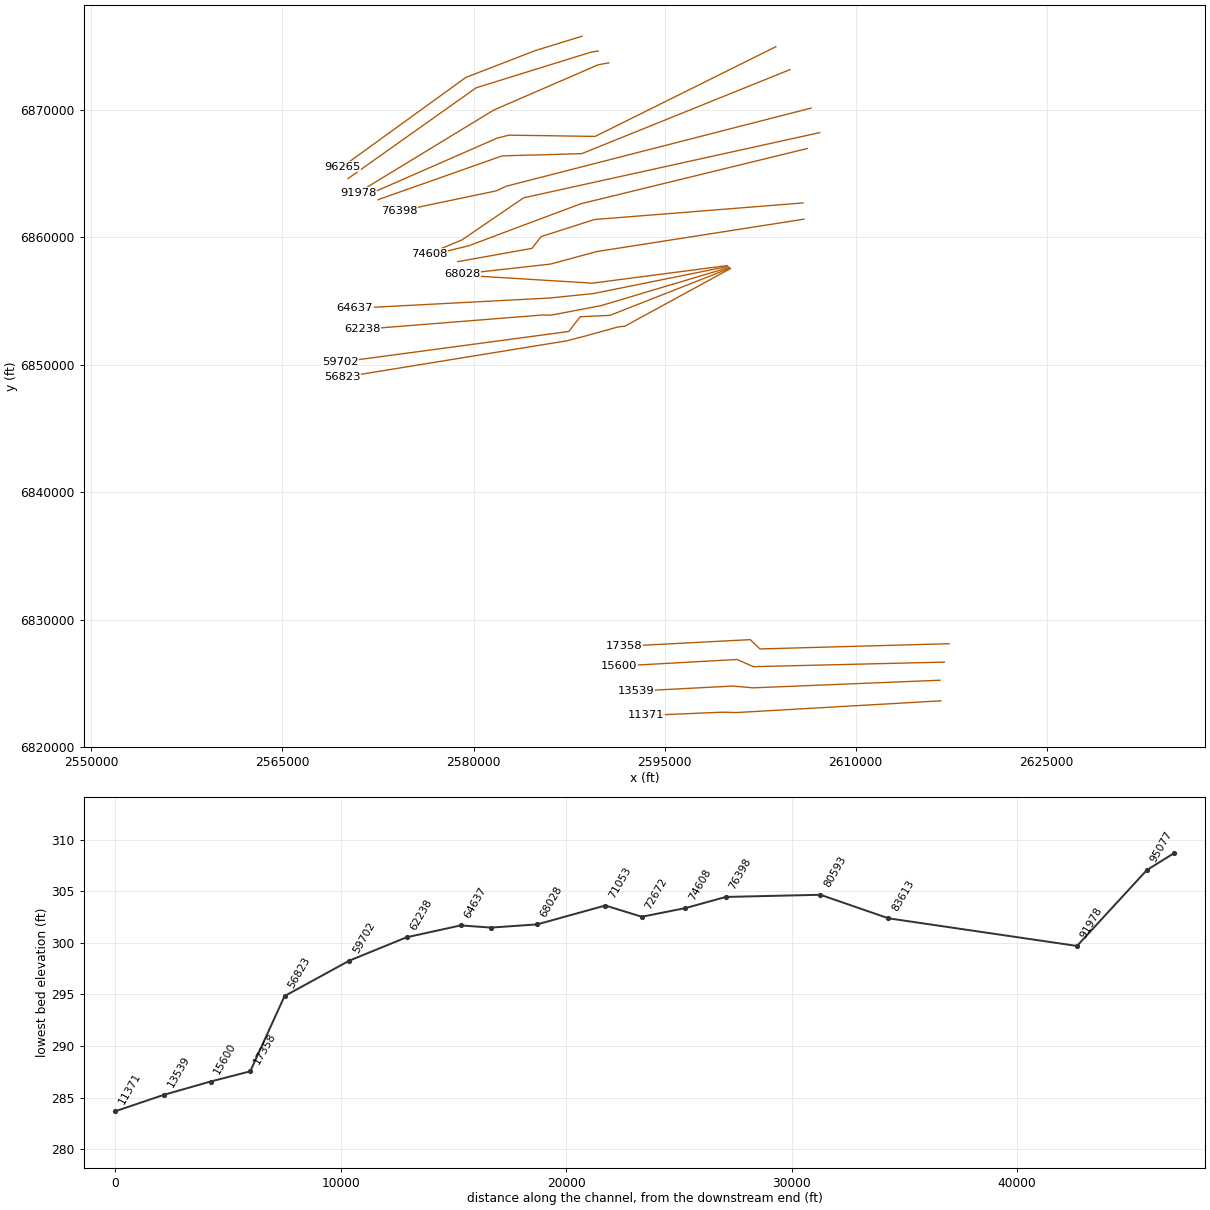
HEC-RAS study TR_FEMA.prj: Trinity_River_FEMA

--- TR_FEMA.g01 (geometry) --- (continued)

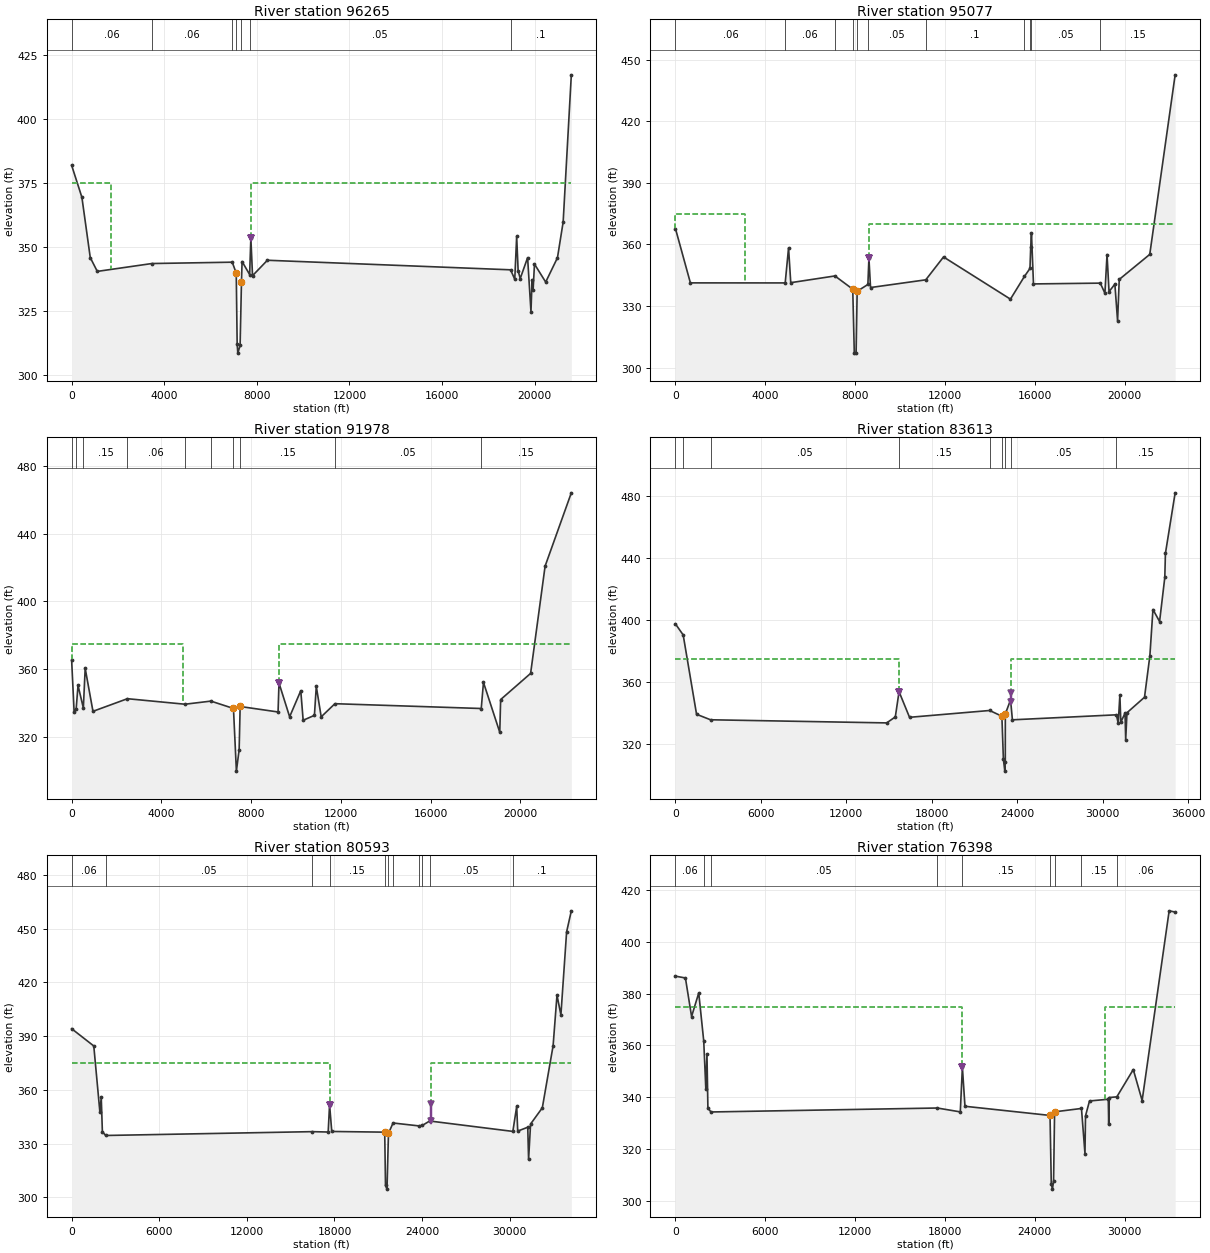
Type RM Length L Ch R = 1 ,96265   ,1483.83,1188.02,1196.23
BEGIN DESCRIPTION:
ROB - Dallas LID14/Ellis LID3
LOB IFA station 1717: flow expansion due to natural high ground upstream
END DESCRIPTION:
XS GIS Cut Line= 4
     2588505.007     6875781.772     2584879.573     6874669.972
     2579399.972     6872554.087     2569704.405     6865536.324
#Sta/Elev= 30
       0  381.97  442.56   369.5  803.83  345.96 1107.88  340.57 3464.47  343.64
 6936.88  344.17  7109.5  339.88 7148.95  312.28 7177.18  308.66 7276.27  311.65
 7335.69  336.59  7361.7  344.42 7687.49  339.35 7740.77  353.59  7812.9  338.89
 8454.78  344.9218958.26  341.1919139.77  337.5119221.88   354.219285.88  340.82
19375.95  337.7819694.72  345.9419839.85  324.8419888.09  337.3519931.03  333.18
19991.59  343.4320475.66   336.420983.95   345.921230.28  359.8721582.92  417.32
#Mann= 7 ,-1 , 0
       0     .06       0 3464.47     .06       0 6936.88     .15       0
  7109.5    .055       0 7335.69     .15       0 7687.49     .05       0
18958.26      .1       0
Levee=0,,,-1,7740.77,353.59,,
#XS Ineff= 2 , 0
       0    1717     375 7740.21       0     375
Permanent Ineff=
       F       F
Bank Sta=7109.5,7335.69
XS Rating Curve= 0 ,0
Exp/Cntr=0.3,0.1

Type RM Length L Ch R = 1 ,95077   ,1759.01,3098.93,2125.14
BEGIN DESCRIPTION:
ROB - Dallas LID14/Ellis LID3
LOB IFA station 3088: flow expansion due to natural high ground upstream
END DESCRIPTION:
XS GIS Cut Line= 4
     2589788.177     6874622.495     2589245.262     6874544.293
     2580213.774     6871740.284     2570155.794     6864616.186
#Sta/Elev= 30
       0  367.72  664.27  341.29 4886.42  341.27 5036.25  358.35 5134.01  341.39
 7101.49  344.67 7895.14  338.22 7964.34  307.05 8044.15  307.05 8091.33   337.2
 8569.44  340.51 8615.35  353.33 8687.44  339.0211147.39  342.7811938.23  353.93
 14917.9  333.3615544.08  344.4915787.85  348.3215821.34  358.8615854.25  365.51
15944.49  340.7818919.48  341.1719125.61  336.2519219.92  355.1219309.16  337.01
19569.22  340.6919689.88  322.75 19763.6  342.9721122.58  355.1722253.59   442.7
#Mann= 11 ,-1 , 0
       0     .06       0 4886.42     .06       0 7101.49     .15       0
 7895.14    .055       0 8091.33     .15       0 8569.44     .05       0
11147.39      .1       015544.08     .05       015787.85     .15       0
15821.34     .05       018919.48     .15       0
Levee=0,,,-1,8615.35,353.33,,
#XS Ineff= 2 , 0
       0    3088     375 8614.84       0     370
Permanent Ineff=
       F       F
Bank Sta=7895.14,8091.33
XS Rating Curve= 0 ,0
Exp/Cntr=0.3,0.1

Type RM Length L Ch R = 1 ,91978   ,4138.76,8364.88,1686.69
BEGIN DESCRIPTION:
ROB - Dallas LID14/Ellis LID3
LOB IFA station 3088: flow expansion due to natural high ground upstream
END DESCRIPTION:
XS GIS Cut Line= 4
     2590625.798     6873699.699     2589782.682     6873544.148
     2581579.557      6869985.12     2570937.044     6863505.074
#Sta/Elev= 30
       0  365.13  109.35  334.88  201.58  336.47  284.32  350.34  521.47  336.98
  603.74  360.39  950.43  335.01 2486.36  342.47 5052.56  339.21 6207.56  341.05
 7214.87  336.71  7345.3  299.69 7468.33  312.42 7512.83  337.87 9203.08  334.63
 9244.69  351.73 9718.85   331.810215.64  347.19 10322.3  329.7310824.22  332.64
10907.49  349.7411126.28  331.7611738.14  339.5218262.54  336.6818361.42   352.1
 19088.2  322.63 19127.3  341.9620463.34  357.4121109.56  420.7822278.61  464.08
#Mann= 10 ,-1 , 0
       0      .1       0  201.58     .06       0  521.47     .15       0
 2486.36     .06       0 5052.56     .15       0 6207.56     .15       0
 7214.87    .055       0 7512.83     .15       011738.14     .05       0
18262.54     .15       0
Levee=0,,,-1,9244.69,351.73,,
#XS Ineff= 2 , 0
       0    4947     375 9245.09       0     375
Permanent Ineff=
       F       F
Bank Sta=7214.87,7512.83
XS Rating Curve= 0 ,0
Exp/Cntr=0.3,0.1

Type RM Length L Ch R = 1 ,83613   ,1518.94,3020.05,1285.42
BEGIN DESCRIPTION:
LOB - Kaufman MUD1, ROB - Dallas LID14/Ellis LID3
END DESCRIPTION:
XS GIS Cut Line= 5
 2603730.71705116874962.430372162589554.058159446867922.78274316
2582787.478298336868020.815150572581851.714409446867784.70403946
2571296.158853886863163.17626168
#Sta/Elev= 30
       0  397.32  540.81  390.23 1480.71  339.04 2461.87   335.514828.84  333.48
15435.57  337.3415698.16  353.6316433.92  337.09 22060.2  341.4922918.43  337.78
23023.94  310.1423124.06  302.3723156.99  308.27 23160.3  339.2523528.43  348.36
23656.09  335.47 30958.4   338.7 31086.6  333.2431202.91   351.431269.87  333.96
31565.77  339.7931610.92  322.4731700.83  340.0332932.54  350.0433309.22  376.78
33524.86  406.6433991.07  398.8934357.37  427.3634400.71   442.835083.67  481.91
#Mann= 9 ,-1 , 0
       0     .05       0  540.81     .06       0 2461.87     .05       0
15698.16     .15       0 22060.2     .15       022918.43    .055       0
 23160.3     .15       023528.43     .05       0 30958.4     .15       0
Levee=-1,15698.16,353.63,-1,23541.78,353,,
#XS Ineff= 2 , 0
       015698.94     37523541.72       0     375
Permanent Ineff=
       F       F
Bank Sta=22918.43,23160.3
XS Rating Curve= 0 ,0
Exp/Cntr=0.3,0.1

Type RM Length L Ch R = 1 ,80593   ,1304.95,4194.89,2623.31
BEGIN DESCRIPTION:
LOB - Kaufman MUD1, ROB - Dallas LID14/Ellis LID3
END DESCRIPTION:
XS GIS Cut Line= 6
2604850.392977026873169.60629808 2588498.97540486866569.52707184
2584746.024015916866460.15207184 2584447.41290486866460.15207184
2582244.114293696866392.443738512572504.492187216862954.84292834
#Sta/Elev= 30
       0  394.15  1516.1  384.52 1932.41  347.79  2026.7   355.8 2104.64   336.7
 2330.28  334.5816478.23  336.7217568.33  336.5117663.45  351.74 17813.6  336.82
 21439.5  336.4421493.62   306.721595.69  304.6521696.77  335.7322009.81  341.55
23755.07  339.9524019.96  340.2224517.68  342.6630214.87  336.8530477.93  350.79
30547.66  337.0131235.09  339.1931292.71  321.24 31428.5  340.9732233.27  350.02
 32971.5  384.6633237.13  412.85 33505.8  401.8833895.88  448.14 34219.2  459.92
#Mann= 11 ,-1 , 0
       0     .06       0 2330.28     .05       016478.23     .15       0
17663.45     .15       0 21439.5    .055       021696.77     .15       0
22009.81     .06       023755.07     .15       024019.96     .06       0
24517.68     .05       030214.87      .1       0
Levee=-1,17663.45,351.74,-1,24580.11,352,,
#XS Ineff= 2 , 0
       017663.57     37524580.11       0     375
Permanent Ineff=
       F       F
Bank Sta=21439.5,21696.77
XS Rating Curve= 0 ,0
Exp/Cntr=0.3,0.1

Type RM Length L Ch R = 1 ,76398   ,1366.66,1790.14,1812.24
BEGIN DESCRIPTION:
LOB - Kaufman MUD1
ROB IFA station 28654: flow expansion due to Dallas LID14/Ellis LID3 levee upstream
END DESCRIPTION:
XS GIS Cut Line= 4
2606496.303529836870144.903692242582555.794270566864008.95461815
2581795.377603896863650.621284822574149.081307596862047.68147001
#Sta/Elev= 30
       0  386.75  664.16  386.05 1075.59  371.15 1553.77  380.26 1887.39  361.67
 2028.38     343 2102.55  356.67 2165.46  335.77 2369.57  334.26 17484.7  335.79
19019.32  334.2919159.68  351.5219332.29  336.4625011.92  332.9225095.98  306.48
25173.32  304.4425249.32   307.725316.97  334.3127111.45  335.6227346.03  318.15
27381.17  332.7527648.06  338.5128902.27  339.1828930.64  329.4228969.84  339.84
29472.69  340.1130572.04  350.6631162.57  338.6932967.12     41233367.44  411.53
#Mann= 9 ,-1 , 0
       0     .06       0 1887.39      .1       0 2369.57     .05       0
 17484.7     .15       019159.68     .15       025011.92    .055       0
25316.97     .06       027111.45     .15       029472.69     .06       0
Levee=-1,19159.68,351.52,0,,,,
#XS Ineff= 2 , 0
       019160.35     375   28654       0     375
Permanent Ineff=
       F       F
Bank Sta=25011.92,25316.97
XS Rating Curve= 0 ,0
Exp/Cntr=0.3,0.1

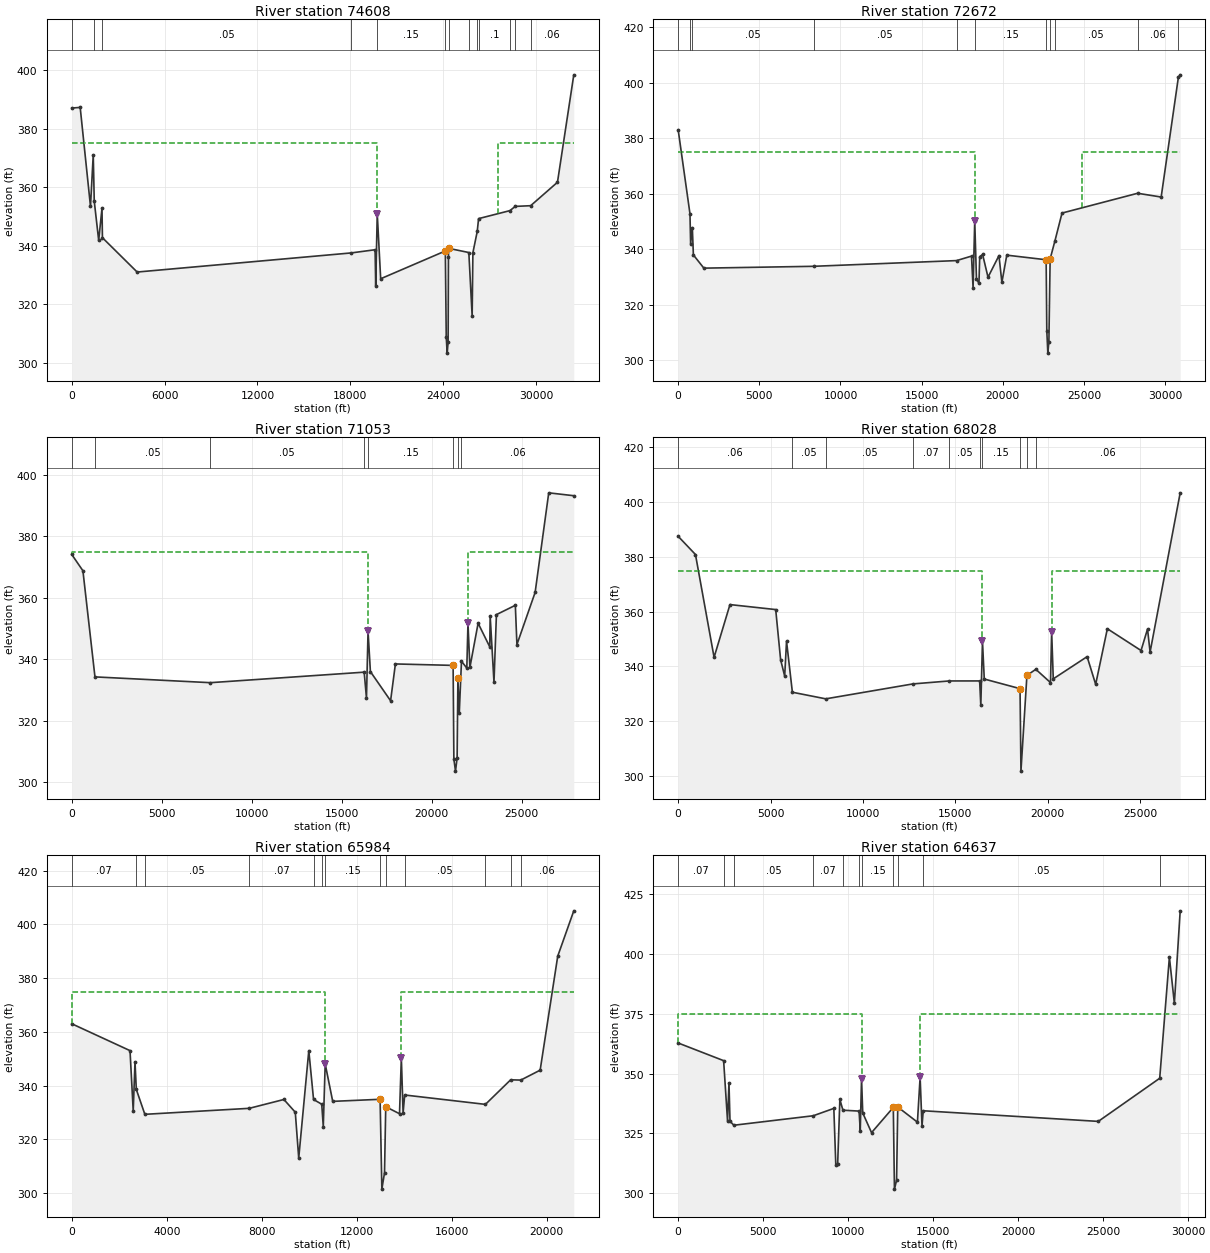
Type RM Length L Ch R = 1 ,74608   ,1431.86,1935.4,1883.95
BEGIN DESCRIPTION:
LOB - Kaufman MUD1
ROB IFA station 27520: flow contraction due to Ellis LID2 levee downstream
END DESCRIPTION:
XS GIS Cut Line= 4
2607172.70399279 6868220.89906262583937.460937236863102.84350704
2579097.669270566859799.892118152576528.224826116858723.50322926
#Sta/Elev= 30
       0  386.99  544.02  387.21 1209.35  353.46 1387.84  371.06  1453.2   355.2
 1739.91  341.83 1952.79   352.8 1981.77  342.74 4224.41  331.0318049.59  337.55
19598.54  338.6419639.09  326.3419738.14  350.9919959.74  328.7424137.05  338.22
24196.64  308.8824256.73  303.3624317.16  307.0724337.97  336.15 24351.3  339.12
25656.08  337.6925870.55  315.9925918.44  337.6326199.21  344.8826285.54  349.26
28312.69  351.9928652.85  353.4329650.73  353.6731383.55  361.6732437.45  398.33
#Mann= 13 ,-1 , 0
       0     .06       0  1453.2      .1       0 1981.77     .05       0
18049.59     .15       019738.14     .15       024137.05    .055       0
 24351.3     .06       025656.08     .15       026199.21     .06       0
26285.54      .1       028312.69     .06       028652.85     .05       0
29650.73     .06       0
Levee=-1,19738.14,350.99,0,,,,
#XS Ineff= 2 , 0
       019738.01     375   27520       0     375
Permanent Ineff=
       F       F
Bank Sta=24137.05,24351.3
XS Rating Curve= 0 ,0
Exp/Cntr=0.3,0.1

Type RM Length L Ch R = 1 ,72672   ,1501.06,1619.39,1672.71
BEGIN DESCRIPTION:
LOB - Kaufman MUD1
ROB IFA station 24899: flow contraction due to Ellis LID2 levee downstream
END DESCRIPTION:
XS GIS Cut Line= 5
2606198.363715026866971.767118162588441.419270566862638.43378482
2583873.020374556860934.26640181  2579635.8637156859339.82267371
2576476.141492786858575.93378482
#Sta/Elev= 30
       0  383.01   727.2  352.74  766.89  341.94  871.99  347.76  937.51  337.91
 1582.58  333.15 8340.55  333.8117154.88  335.8718074.57  337.4918170.86  326.06
18272.61  350.1918379.52  329.3318533.11  327.6518579.39  337.2818758.24  338.07
19091.29  329.8819765.68  337.6719945.51  328.0220247.72  337.8322673.05  336.17
22712.98  310.65 22777.3  302.5222842.09  306.6622918.57  336.4623219.55   343.1
23651.49     353 28308.2  360.1329760.24  358.7830818.87  401.8830931.89  402.82
#Mann= 11 ,-1 , 0
       0     .06       0   727.2      .1       0  871.99     .05       0
 8340.55     .05       017154.88     .15       018272.61     .15       0
22673.05    .055       022918.57     .15       023219.55     .05       0
 28308.2     .06       030818.87     .06       0
Levee=-1,18272.61,350.19,0,,,,
#XS Ineff= 2 , 0
       018272.99     375   24899       0     375
Permanent Ineff=
       F       F
Bank Sta=22673.05,22918.57
XS Rating Curve= 0 ,0
Exp/Cntr=0.3,0.1

Type RM Length L Ch R = 1 ,71053   ,2459.34,3024.49,2512.9
BEGIN DESCRIPTION:
LOB - Kaufman MUD1, ROB - Ellis LID2
END DESCRIPTION:
XS GIS Cut Line= 5
2605863.33767335 6862699.80531262589491.809895566861397.72197927
2585316.462673346860060.916423712584586.601562236859133.13864593
2578762.64322889 6858090.4303126
#Sta/Elev= 30
       0  374.05  619.76  368.76 1289.43  334.25 7702.91  332.3716253.83  335.79
16381.42  327.3416468.21  349.1416598.92  335.9817721.62  326.4917989.07  338.46
21197.53  337.9921239.12  307.5521329.45  303.6121420.01  307.87 21462.5  333.79
21539.34  322.4721661.53  339.3521958.48  337.1222022.37  351.7122131.22  337.35
22586.16   351.723233.27  344.0223256.45  354.0823468.82   332.5 23604.2   354.5
24655.53  357.5324743.94  344.7825755.54  361.7126512.19   394.127904.46  393.16
#Mann= 8 ,-1 , 0
       0     .06       0 1289.43     .05       0 7702.91     .05       0
16253.83     .15       016468.21     .15       021197.53    .055       0
 21462.5     .15       021661.53     .06       0
Levee=-1,16468.21,349.14,-1,22022.37,351.71,,
#XS Ineff= 2 , 0
       016467.63     37522022.37       0     375
Permanent Ineff=
       F       F
Bank Sta=21197.53,21462.5
XS Rating Curve= 0 ,0
Exp/Cntr=0.3,0.1

Type RM Length L Ch R = 1 ,68028   ,2550.09,2044.38,1660.23
BEGIN DESCRIPTION:
LOB - Kaufman MUD1, ROB - Ellis LID2
END DESCRIPTION:
XS GIS Cut Line= 4
2605931.785011316861423.225451462589668.590566876858881.67452554
2586047.062789096857900.771747762579138.035011316857129.47545146
#Sta/Elev= 30
       0   387.5  935.94  380.86 1943.46  343.33 2802.54  362.58 5277.51  360.76
 5543.05  342.47  5763.6  336.46 5863.55  349.23 6180.16  330.58 7986.68  328.17
12702.35  333.6214668.17   334.716313.76  334.7116376.19  325.7416466.15  349.24
16563.36   335.418498.82  331.8918547.94  301.7818871.39  336.7219352.53  338.95
20145.87  334.1120209.69   352.620296.95  335.4722128.28  343.5722591.26  333.46
23223.39  353.76 25046.8  345.81 25397.3  353.6525536.06  345.2527164.56  403.38
#Mann= 10 ,-1 , 0
       0     .06       0 6180.16     .05       0 7986.68     .05       0
12702.35     .07       014668.17     .05       016313.76     .15       0
16466.15     .15       018498.82    .055       018871.39     .15       0
19352.53     .06       0
Levee=-1,16466.15,349.24,-1,20209.69,352.6,,
#XS Ineff= 2 ,-1
       016467.39     37520209.7127164.56     375
Permanent Ineff=
       F       F
Bank Sta=18498.82,18871.39
XS Rating Curve= 0 ,0
Exp/Cntr=0.3,0.1

Type RM Length L Ch R = 1 ,65984   ,761.4,1346.66,1829.69
BEGIN DESCRIPTION:
LOB - Kaufman MUD1, ROB - Ellis LID2
END DESCRIPTION:
XS GIS Cut Line= 4
2599899.674578646857782.477761572589338.451606636856402.66982564
2586149.562643236856597.114318642578859.972563656857045.02648056
#Sta/Elev= 30
       0  363.01 2454.07  353.01 2589.02  330.55 2663.99  348.86 2718.96  338.58
 3078.82  329.31 7477.09  331.54 8936.51  334.83 9416.33  330.09 9561.27  313.02
  9986.1  353.0310186.02  334.8310530.89  333.0710595.86  324.7510676.33  348.07
10993.27  334.1312989.66   334.913063.81  301.4713175.51  307.5413227.37  332.13
13807.24  329.5313884.37  350.3313958.72  329.8914025.36   336.517427.05  333.01
18489.29  342.1518916.26  342.0519732.17  345.7420473.26  388.1821149.13  405.04
#Mann= 13 ,-1 , 0
       0     .07       0 2718.96     .06       0 3078.82     .05       0
 7477.09     .07       010186.02     .05       010530.89     .15       0
10676.33     .15       012989.66    .055       013227.37     .06       0
14025.36     .05       017427.05     .06       018489.29     .05       0
18916.26     .06       0
Levee=-1,10676.33,348.07,-1,13884.37,350.33,,
#XS Ineff= 2 ,-1
       010675.66     37513884.3221149.13     375
Permanent Ineff=
       F       F
Bank Sta=12989.66,13227.37
XS Rating Curve= 0 ,0
Exp/Cntr=0.3,0.1

Type RM Length L Ch R = 1 ,64637   ,1009.07,2399.06,1604.33
BEGIN DESCRIPTION:
LOB - Kaufman MUD1, ROB - Ellis LID2
END DESCRIPTION:
XS GIS Cut Line= 4
2599965.936913316857716.215426892589427.340536486855588.78103347
2585969.007230046855236.003195732570686.948883476854434.65768556
#Sta/Elev= 30
       0  362.84 2674.05  355.45 2903.96  330.26 2988.93  346.18 3048.91  330.12
 3273.83  328.42 7947.17  332.39 9156.71  335.47 9271.66  311.98 9381.62  312.13
 9511.57  339.22  9691.5  334.7110641.13  334.34 10711.1  326.1910786.73  347.98
10856.94  333.5711375.03  325.32 12655.1  335.8812722.57  301.6812847.47  305.35
12917.21  336.05   14074  329.7114232.38  348.5214343.15  328.1414416.02  334.48
24712.42  330.0328326.19  348.0828895.17  398.7729188.35  379.4529530.52  418.16
#Mann= 11 ,-1 , 0
       0     .07       0 2674.05     .06       0 3273.83     .05       0
 7947.17     .07       0  9691.5     .05       010641.13     .15       0
10786.73     .15       0 12655.1    .055       012917.21     .06       0
14416.02     .05       028326.19     .06       0
Levee=-1,10786.76,347.98,-1,14232.38,348.52,,
#XS Ineff= 2 ,-1
       010787.51     37514233.2229530.52     375
Permanent Ineff=
       F       F
Bank Sta=12655.1,12917.21
XS Rating Curve= 0 ,0
Exp/Cntr=0.3,0.1

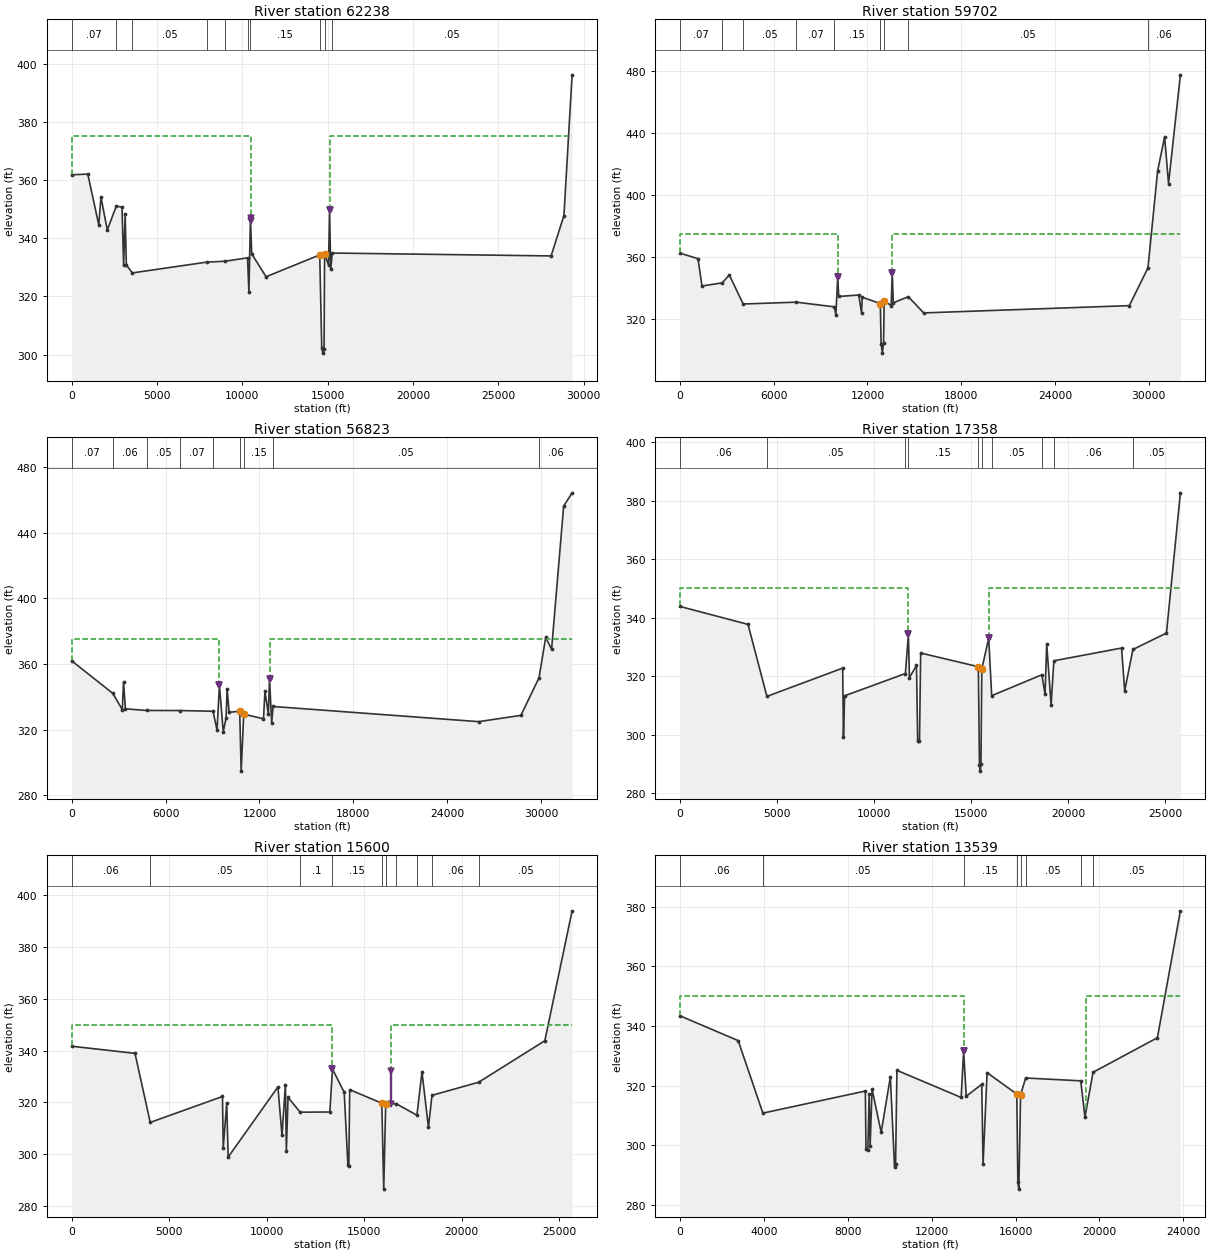
Type RM Length L Ch R = 1 ,62238   ,934.88,2536.56,1721.21
BEGIN DESCRIPTION:
LOB - Kaufman MUD1, ROB - Ellis LID2
END DESCRIPTION:
XS GIS Cut Line= 5
 2600070.0630174 6857640.48723192589996.437823476854635.30885907
2586090.592944896853892.311001232585441.287484976853906.20008107
2571292.502462396852779.63737357
#Sta/Elev= 30
       0   361.8  944.76  362.01  1589.6   344.5 1714.56  354.18 2084.47  342.84
 2619.34  351.08 2949.25  350.62 3044.23  330.72 3134.21  348.27 3204.19  330.77
  3559.1  328.08 7917.97  331.79 8987.74  332.0910307.48  333.2710387.47  321.62
10477.67  346.8610552.87  334.6311392.43  326.76   14538  334.2714657.47  302.21
14722.48  300.5314793.15  301.8814821.85  334.5615054.51  330.8615115.79  349.72
15180.49  329.3515272.27  334.9128099.84  333.9228850.59  347.7729331.23  396.12
#Mann= 10 ,-1 , 0
       0     .07       0 2619.34     .06       0  3559.1     .05       0
 7917.97     .07       0 8987.74     .05       010307.48     .15       0
10477.67     .15       0   14538    .055       014821.85     .06       0
15272.27     .05       0
Levee=-1,10482.67,346.86,-1,15115.79,349.72,,
#XS Ineff= 2 ,-1
       0 10483.4     37515115.5229331.23     375
Permanent Ineff=
       F       F
Bank Sta=14538,14821.85
XS Rating Curve= 0 ,0
Exp/Cntr=0.3,0.1

Type RM Length L Ch R = 1 ,59702   ,1056.97,2878.56,838.01
BEGIN DESCRIPTION:
LOB - Kaufman MUD1, ROB - Ellis LID2
END DESCRIPTION:
XS GIS Cut Line= 5
 2600117.39330336857574.224897222590721.588932226853876.65125564
2588378.092963076853766.616698822587474.751265796852609.13804264
2569517.328847386850204.46371815
#Sta/Elev= 30
       0  362.63 1154.68  359.07 1409.61  341.48 2704.25   343.5 3159.13  348.59
 4043.89   329.9 7452.94  331.07 9882.27  328.06 9977.25  322.8510099.32  347.32
10159.24  334.7711445.83  335.6411621.68  324.0511661.96  334.2612824.23   330.2
12873.03  304.45 12951.6  298.2713031.31  304.8513070.14  332.0213518.94  328.85
13585.21  350.0913652.52  330.6514614.64   334.6   15599  324.1628757.88  328.84
29952.04   353.130574.18  415.67 31020.4  437.5131270.17  407.4132029.23  477.42
#Mann= 9 ,-1 , 0
       0     .07       0 2704.25     .06       0 4043.89     .05       0
 7452.94     .07       0 9882.27     .15       012824.23    .055       0
13070.14     .15       014614.64     .05       029952.04     .06       0
Levee=-1,10099.32,347.32,-1,13585.21,350.09,,
#XS Ineff= 2 ,-1
       010100.35     37513584.9632029.23     375
Permanent Ineff=
       F       F
Bank Sta=12824.23,13070.14
XS Rating Curve= 0 ,0
Exp/Cntr=0.3,0.1

Type RM Length L Ch R = 1 ,56823   ,1814.93,1520.67,905.82
BEGIN DESCRIPTION:
LOB - Kaufman MUD1, ROB - Ellis LID2
END DESCRIPTION:
XS GIS Cut Line= 6
2600164.723589216857545.826660072591868.659144646853018.84982164
2591375.143071296852974.125173552588772.712580656852253.63908173
2587328.241060146851877.223824052569716.981663326849015.22790764
#Sta/Elev= 30
       0  362.01 2628.83  342.19 3233.56  332.27 3313.52  349.09 3433.47  332.78
 4782.89  331.77    6952  331.73 9031.16  331.28 9291.06  319.89 9441.28  347.18
 9686.46  318.71 9869.48  327.38 9931.25  344.8610063.92  330.6410737.48  331.34
10830.73  294.8310995.67  329.5612257.78  326.6612349.83  343.4212568.44  329.76
12644.66  351.0612780.08  324.0812869.66   334.226003.58  324.9628707.25  328.77
29865.42  351.6430294.22  376.3130669.65  369.0431440.07   456.2 31981.7  464.31
#Mann= 9 ,-1 , 0
       0     .07       0 2628.83     .06       0 4782.89     .05       0
    6952     .07       0 9031.16     .15       010737.48    .055       0
10995.67     .15       012869.66     .05       029865.42     .06       0
Levee=-1,9441.28,347.18,-1,12644.66,351.06,,
#XS Ineff= 2 ,-1
       0 9440.25     375 12642.8 31981.7     375
Permanent Ineff=
       F       F
Bank Sta=10737.48,10995.67
XS Rating Curve= 0 ,0
Exp/Cntr=0.3,0.1

Type RM Length L Ch R = 1 ,17358   ,1420.5,1758.18,1573.47
BEGIN DESCRIPTION:
LOB - Kaufman LID1/Henderson LID1, ROB - Ellis LID2
END DESCRIPTION:
XS GIS Cut Line= 4
  2617325.027619   6828100.30077 2602483.9771289 6827689.9468975
 2601723.6513308 6828420.8407292 2591844.9203689 6827903.9698543
#Sta/Elev= 30
       0  343.84 3507.69   337.7 4481.58  313.09 8386.33  322.75 8426.59  299.28
 8486.79  313.2911618.63   320.911773.99  334.3111826.98  319.5112191.52  323.65
12251.93   297.812345.92  297.7512406.34  327.9115379.45  323.2415438.49  289.48
15479.56  287.5415513.17  289.8515557.89  322.4215913.33  332.9516067.94  313.33
18652.41  320.4818817.39  313.8418902.67  330.9619130.18   310.219271.54  325.26
22761.06  329.6222921.87  314.9723345.55  329.1225074.75  334.7425793.57  382.68
#Mann= 10 ,-1 , 0
       0     .06       0 4481.58     .05       011618.63      .1       0
11773.99     .15       015379.45    .055       015557.89     .15       0
16067.94     .05       018652.41     .15       019271.54     .06       0
23345.55     .05       0
Levee=-1,11773.99,334.31,-1,15913.33,332.95,,
#XS Ineff= 2 , 0
       011775.13     35015913.35       0     350
Permanent Ineff=
       F       F
Bank Sta=15379.45,15557.89
XS Rating Curve= 0 ,0
Exp/Cntr=0.3,0.1

Type RM Length L Ch R = 1 ,15600   ,1608.95,2060.49,2106.04
BEGIN DESCRIPTION:
LOB - Kaufman LID1/Henderson LID1, ROB - Ellis LID2
END DESCRIPTION:
XS GIS Cut Line= 4
  2616953.851988 6826656.8399823 2601977.2145359 6826298.6985631
 2600689.1096641  6826862.618507 2591425.2169149 6826347.5269563
#Sta/Elev= 30
       0  341.69 3247.39  338.93 4027.84  312.29  7734.2  322.29 7771.73  302.44
 7951.05  319.79 8024.98   298.910576.64  325.9810785.35  307.3210961.44  326.86
11009.95   301.311095.96  321.9211718.38  316.2413238.98  316.3113375.88  332.87
13977.19  323.8714166.39  295.6914213.29  295.57 14257.6  324.9315904.39  319.71
 16003.8  286.5516103.74 319.47616648.49  319.4717706.17  315.07 17965.2  331.78
18296.69  310.3718477.35  322.7420873.65   327.824265.14   343.825665.24  393.93
#Mann= 10 ,-1 , 0
       0     .06       0 4027.84     .05       011718.38      .1       0
13375.88     .15       015904.39    .055       016103.74     .15       0
16648.49     .05       017706.17     .15       018477.35     .06       0
20873.65     .05       0
Levee=-1,13375.88,332.87,-1,16378.11,332.03,,
#XS Ineff= 2 , 0
       013375.87     35016378.11       0     350
Permanent Ineff=
       F       F
Bank Sta=15904.39,16103.74
XS Rating Curve= 0 ,0
Exp/Cntr=0.3,0.1

Type RM Length L Ch R = 1 ,13539   ,1853.81,2167.97,2021.98
BEGIN DESCRIPTION:
LOB - Kaufman LID1/Henderson LID1
ROB IFA station 19377: flow expansion due to Ellis LID2 levee upstream
END DESCRIPTION:
XS GIS Cut Line= 4
  2616623.918094  6825234.000063 2601962.4806649 6824635.9948795
 2600358.5541085 6824776.2990626 2592791.3708253 6824383.1898411
#Sta/Elev= 30
       0  343.39 2775.84  335.06 3953.71  310.76 8841.22  318.16 8867.95  298.84
 8957.82  298.42 9020.78  317.01 9066.89  299.69 9158.91  318.78 9594.84   304.3
10031.85  322.8710230.43   292.8 10280.7  293.5710345.09   325.113408.84     316
13525.78  331.5113649.38  316.4214390.17  320.4114452.01  293.6114644.67  324.32
16060.18  317.1416110.86  287.5716157.83  285.2716241.02 316.86316481.97  322.53
 19109.8  321.58 19310.9  309.4119695.51  324.4422765.08  336.0323861.07  378.58
#Mann= 8 ,-1 , 0
       0     .06       0 3953.71     .05       013525.78     .15       0
16060.18    .055       016241.02     .15       016481.97     .05       0
 19109.8     .15       019695.51     .05       0
Levee=-1,13525.78,331.51,0,,,,
#XS Ineff= 2 , 0
       013521.13     350   19377       0     350
Permanent Ineff=
       F       F
Bank Sta=16060.18,16241.02
XS Rating Curve= 0 ,0
Exp/Cntr=0.3,0.1

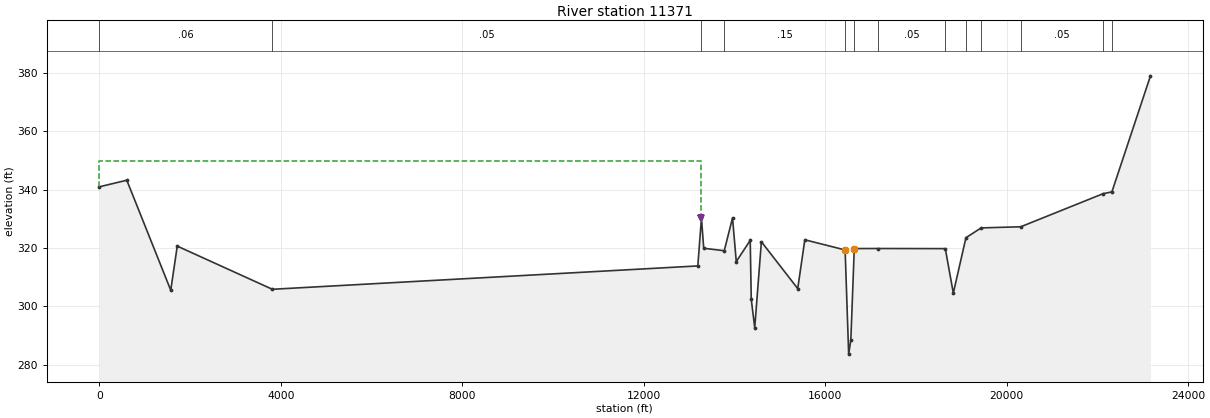
Type RM Length L Ch R = 1 ,11371   ,1126.53,1866.67,1035.01
BEGIN DESCRIPTION:
LOB - Kaufman LID1/Henderson LID1
END DESCRIPTION:
XS GIS Cut Line= 4
  2616678.549045 6823617.0750931 2600683.9868244 6822697.6332504
 2599525.4779132 6822724.6510036 2593543.1323784 6822471.2417597
#Sta/Elev= 30
       0  341.02  607.45  343.29 1576.29  305.58 1719.57   320.7 3815.42   305.9
13191.75  313.9113271.83  330.3413321.82  319.9713774.15319.1138 13956.7  330.37
14039.04   315.414346.56  322.6814369.23  302.4814446.18  292.7314592.49   322.2
15393.52  306.1415549.96  322.8716438.22  319.3816516.24  283.6716564.05  288.58
16639.64  319.8617168.75  319.8818645.72  319.84 18822.4  304.5919100.58  323.58
19435.75  326.9420308.26  327.3322124.54  338.6822317.14  339.2923167.53  379.08
#Mann= 13 ,-1 , 0
       0     .06       0 3815.42     .05       013271.83     .06       0
13774.15     .15       016438.22    .055       016639.64     .15       0
17168.75     .05       018645.72     .15       019100.58     .05       0
19435.75     .06       020308.26     .05       022124.54     .06       0
22317.14     .05       0
Levee=-1,13271.83,330.34,0,,,,
#XS Ineff= 2 , 0
       013271.81     350               0
Permanent Ineff=
       F       F
Bank Sta=16438.22,16639.64
XS Rating Curve= 0 ,0
Exp/Cntr=0.3,0.1

--- TR_FEMA.g03 (geometry) ---

Geom Title=Trinity_NV_KaufLID1_HendLID1
Program Version=5.06
BEGIN GEOM DESCRIPTION:
Scenario A
END GEOM DESCRIPTION:

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
River Reach=Trinity River   ,1

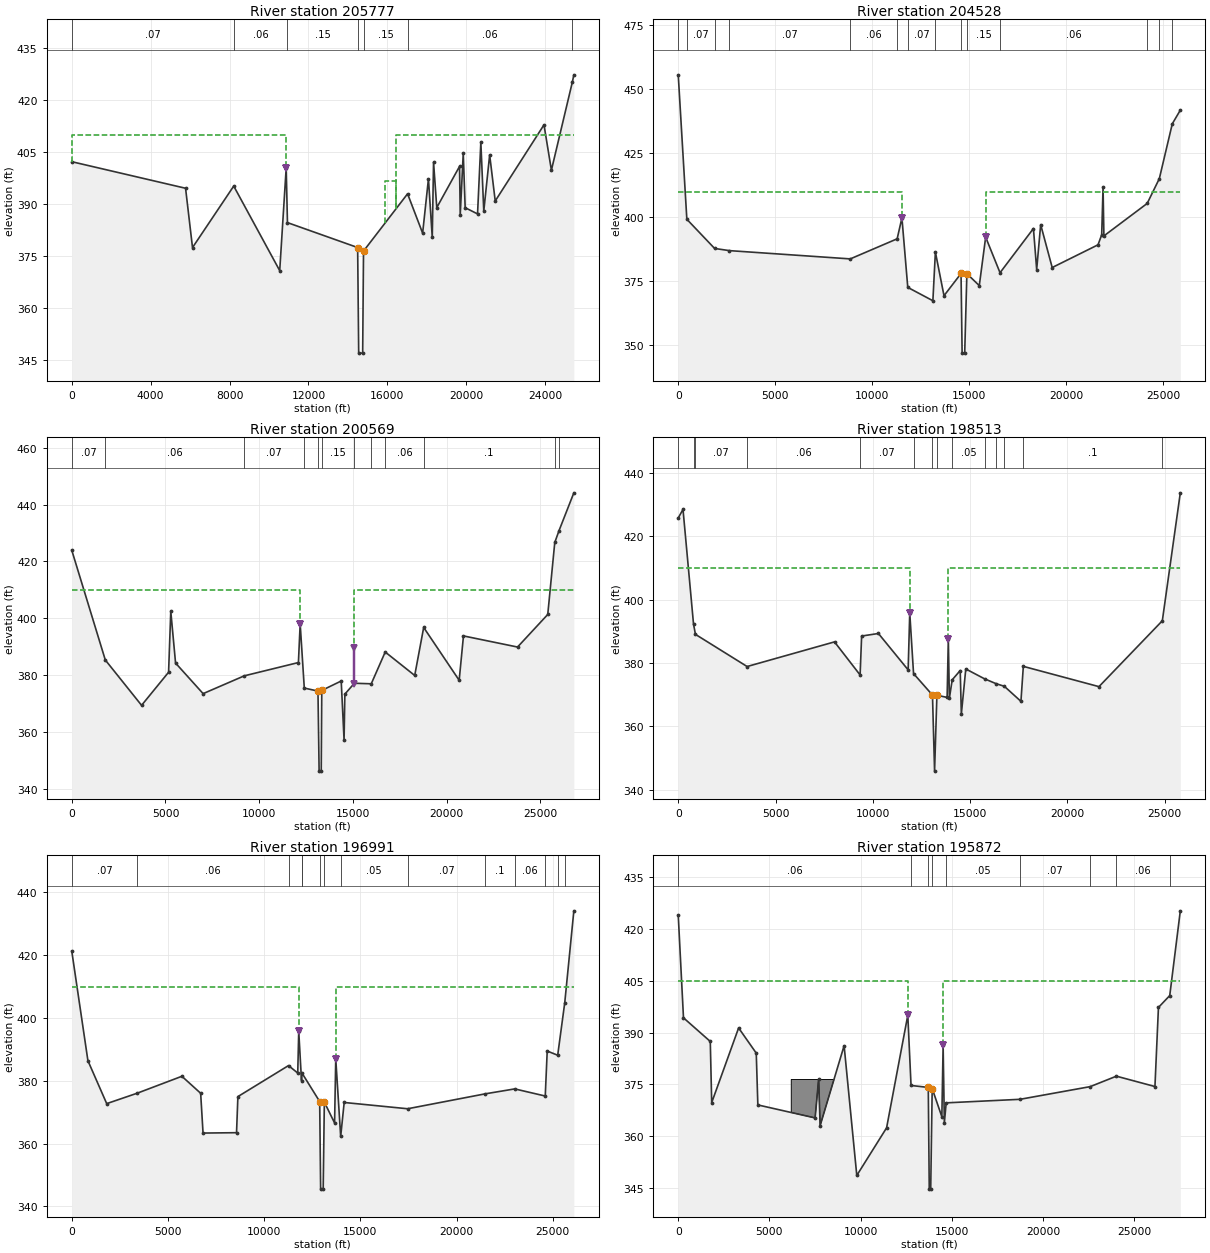
Type RM Length L Ch R = 1 ,205777  ,1262.75,1248.24,1229.51
BEGIN DESCRIPTION:
LOB - Southside WWTP
ROB IFA station 16416: flow contraction due to Dallas LID1/2 levee downstream
END DESCRIPTION:
XS GIS Cut Line= 6
2540980.83019298 6933539.73664742535497.477602626924208.30611411
2533614.000070366920921.000024692533600.635923866920903.28221235
 2529903.70565376914444.53364694 2528203.05241526911525.84775851
#Sta/Elev= 30
       0  402.32 5769.27  394.66 6121.02  377.55 8210.64  395.2910542.62  370.89
10870.96  400.54 10934.7  384.7514493.46  377.5614546.29   347.114748.07   347.1
14791.42  376.5417024.34  393.0617788.14  381.7118082.62  397.3718276.12  380.47
18341.35  402.1718504.74  389.0819659.18  400.9719693.92  387.0319847.13  404.74
19944.42  389.0520572.06  387.2620739.04  407.9220887.76  388.0721186.02  404.29
21468.32  390.9923940.48  412.9624316.52  399.8725381.49  425.37 25454.1  427.38
#Mann= 7 ,-1 , 0
       0     .07       0 8210.64     .06       0 10934.7     .15       0
14493.46    .055       014791.42     .15       017024.34     .06       0
25381.49     .08       0
Levee=-1,10870.96,400.54,0,,,,
#XS Ineff= 3 ,-1
       010870.96     41015871.74   16416  396.63   16416 25454.1     410
Permanent Ineff=
       F       F       F
Bank Sta=14493.46,14791.42
XS Rating Curve= 0 ,0
Exp/Cntr=0.3,0.1

Type RM Length L Ch R = 1 ,204528  ,2887.05,3959.05,2930.12
BEGIN DESCRIPTION:
LOB - Southside WWTP, ROB - Dallas LID1/2
END DESCRIPTION:
XS GIS Cut Line= 2
2542141.897480176933195.790666072529164.466924626910799.95733273
#Sta/Elev= 30
       0  455.63  443.94  399.25 1874.77  387.86 2636.03  387.01 8868.79  383.78
 11286.5  391.6211531.94  399.8111833.59  372.66   13128  367.4513257.32  386.45
13701.35  369.4114580.29  378.0914635.11     34714768.51     34714880.75  378.02
 15520.2  373.3515849.58  392.2716589.78  378.3818311.86  395.6418478.88  379.64
18685.27  397.1519279.01  380.4121641.73  389.2821830.52  393.1621901.42  411.66
21944.71  392.7524176.62  405.4324802.88  415.12 25470.9  436.52 25884.1  441.84
#Mann= 14 ,-1 , 0
       0     .06       0  443.94     .07       0 1874.77     .06       0
 2636.03     .07       0 8868.79     .06       0 11286.5     .07       0
11833.59     .07       013257.32     .15       014580.29    .055       0
14880.75     .15       016589.78     .06       024176.62      .1       0
24802.88     .08       0 25470.9     .06       0
Levee=-1,11531.94,399.81,-1,15849.58,392.27,,
#XS Ineff= 2 ,-1
       011531.94     41015849.58 25884.1     410
Permanent Ineff=
       F       F
Bank Sta=14580.29,14880.75
XS Rating Curve= 0 ,0
Exp/Cntr=0.3,0.1

Type RM Length L Ch R = 1 ,200569  ,2068.54,2056.32,2002.94
BEGIN DESCRIPTION:
LOB - Southside WWTP, ROB - Dallas LID1/2
END DESCRIPTION:
XS GIS Cut Line= 2
2544594.042023046931842.514654862531312.792023046908578.62576596
#Sta/Elev= 30
       0  423.94 1788.99  385.37 3724.12  369.43 5165.31  381.06  5282.7  402.49
 5537.92  384.29 7008.09  373.54 9204.36   379.8 12092.6  384.4712186.52  398.09
12405.92   375.513135.77  374.4413197.04   346.313309.94   346.313339.14  374.67
14376.03  377.98 14528.7  357.2114570.62  373.3715078.25  377.1915978.95     377
16723.98  388.1718297.74  379.9318776.03   396.820669.98  378.2320898.87  393.83
23784.09  389.9225396.01  401.3725770.55  426.6825998.04  430.8526788.13  444.13
#Mann= 12 ,-1 , 0
       0     .07       0 1788.99     .06       0 9204.36     .07       0
12405.92     .15       013135.77    .055       013339.14     .15       0
15078.25     .05       015978.95     .15       016723.98     .06       0
18776.03      .1       025770.55     .06       025998.04      .1       0
Levee=-1,12186.52,398.09,-1,15042.98,389.42,,
#XS Ineff= 2 , 0
       012186.52     41015042.98       0     410
Permanent Ineff=
       F       F
Bank Sta=13135.77,13339.14
XS Rating Curve= 0 ,0
Exp/Cntr=0.3,0.1

Type RM Length L Ch R = 1 ,198513  ,1460.65,1522.21,1546.82
BEGIN DESCRIPTION:
LOB - Southside WWTP, ROB - Dallas LID1/2
END DESCRIPTION:
XS GIS Cut Line= 2
2546593.000356376930554.320210412533259.667023046908470.98687708
#Sta/Elev= 30
       0  425.75  245.08  428.46  785.82  392.24  884.58  389.01 3538.59  378.86
  8028.9  386.64 9344.62  376.19 9422.44  388.4810284.69  389.2911812.69   377.8
11895.24  395.8312090.23  376.6313062.88  369.8413170.69  345.8413290.24  369.79
13815.75  369.1113876.77  387.6313931.21  368.8614077.49  374.6714487.86   377.6
14545.98  363.8614774.24  378.0915737.73  374.9816333.56  373.4416753.99  372.62
17607.92  367.8717730.47  378.9121616.22  372.5124872.14   393.325796.39  433.69
#Mann= 14 ,-1 , 0
       0     .07       0  785.82     .06       0  884.58     .07       0
 3538.59     .06       0 9344.62     .07       012090.23     .15       0
13062.88    .055       013290.24     .15       014077.49     .05       0
15737.73     .15       016333.56     .05       016753.99      .1       0
17730.47      .1       024872.14     .06       0
Levee=-1,11895.24,395.83,-1,13876.77,387.63,,
#XS Ineff= 2 , 0
       011895.24     41013876.77       0     410
Permanent Ineff=
       F       F
Bank Sta=13062.88,13290.24
XS Rating Curve= 0 ,0
Exp/Cntr=0.3,0.1

Type RM Length L Ch R = 1 ,196991  ,1114.91,1119.14,1044.18
BEGIN DESCRIPTION:
LOB - Southside WWTP, ROB - Dallas LID1/2
END DESCRIPTION:
XS GIS Cut Line= 4
2547677.578059796929952.10407455 2541957.4391709 6920324.0658801
2540764.383615346917785.437407882533997.022504236907764.60407454
#Sta/Elev= 30
       0  421.27  839.66  386.38 1815.93  372.72 3409.48  376.06 5723.11  381.43
 6699.35  376.02 6823.04  363.35 8563.77  363.47  8634.5  374.9611265.75  384.84
11744.94  382.4611797.07   395.811940.64  380.0711963.21  382.48 12885.5  373.39
12935.15   345.513068.07   345.513127.74   373.213659.69  366.5713720.65  387.01
13977.28  362.2714158.97  373.0917457.43  371.09 21480.1  375.8323024.23  377.41
24609.89  375.1424711.78  389.4725256.73  388.1325623.98  404.8926096.06  434.11
#Mann= 14 ,-1 , 0
       0     .07       0 3409.48     .06       011265.75     .07       0
11940.64     .06       011963.21     .15       0 12885.5    .055       0
13127.74     .15       013977.28     .05       017457.43     .07       0
 21480.1      .1       023024.23     .06       024609.89      .1       0
25256.73     .06       025623.98     .08       0
Levee=-1,11797.07,395.8,-1,13720.65,387.01,,
#XS Ineff= 2 , 0
       011797.07     41013720.65       0     410
Permanent Ineff=
       F       F
Bank Sta=12885.5,13127.74
XS Rating Curve= 0 ,0
Exp/Cntr=0.3,0.1

Type RM Length L Ch R = 1 ,195872  ,1736.76,1726.95,2123
BEGIN DESCRIPTION:
LOB - Southside WWTP, ROB - Dallas LID1/2
END DESCRIPTION:
XS GIS Cut Line= 4
2550259.667023046929359.875765962543024.453059796920010.14805602
2541811.258615346917361.536944912534173.275757926907095.38516339
#Sta/Elev= 30
       0  423.88  287.75  394.24 1757.09  387.42    1835  369.77 3310.85  391.32
 4278.01  384.05 4365.39   369.1 7505.83  365.35 7698.96  376.54    7781  363.13
 9095.51  386.19 9791.23  348.7511425.27  362.49   12588  394.9912765.73  374.72
13710.48  374.1513764.86   344.813843.92   344.813925.96  373.8214455.32  365.69
14525.15  386.3414592.48  363.9514693.44   369.718740.62  370.7222588.93  374.38
24027.44   377.426140.25  374.4126332.27  397.2426951.71  400.66 27531.3  425.12
#Mann= 9 ,-1 , 0
       0     .06       012765.73     .15       013710.48    .055       0
13925.96     .15       014693.44     .05       018740.62     .07       0
22588.93      .1       024027.44     .06       026951.71     .08       0
Levee=-1,12588,394.99,-1,14525.15,386.34,,
#XS Ineff= 2 , 0
       0   12588     40514525.15       0     405
Permanent Ineff=
       F       F
#Block Obstruct= 1 ,-1
 6197.83 8582.22  376.44
Bank Sta=13710.48,13925.96
XS Rating Curve= 0 ,0
Exp/Cntr=0.3,0.1