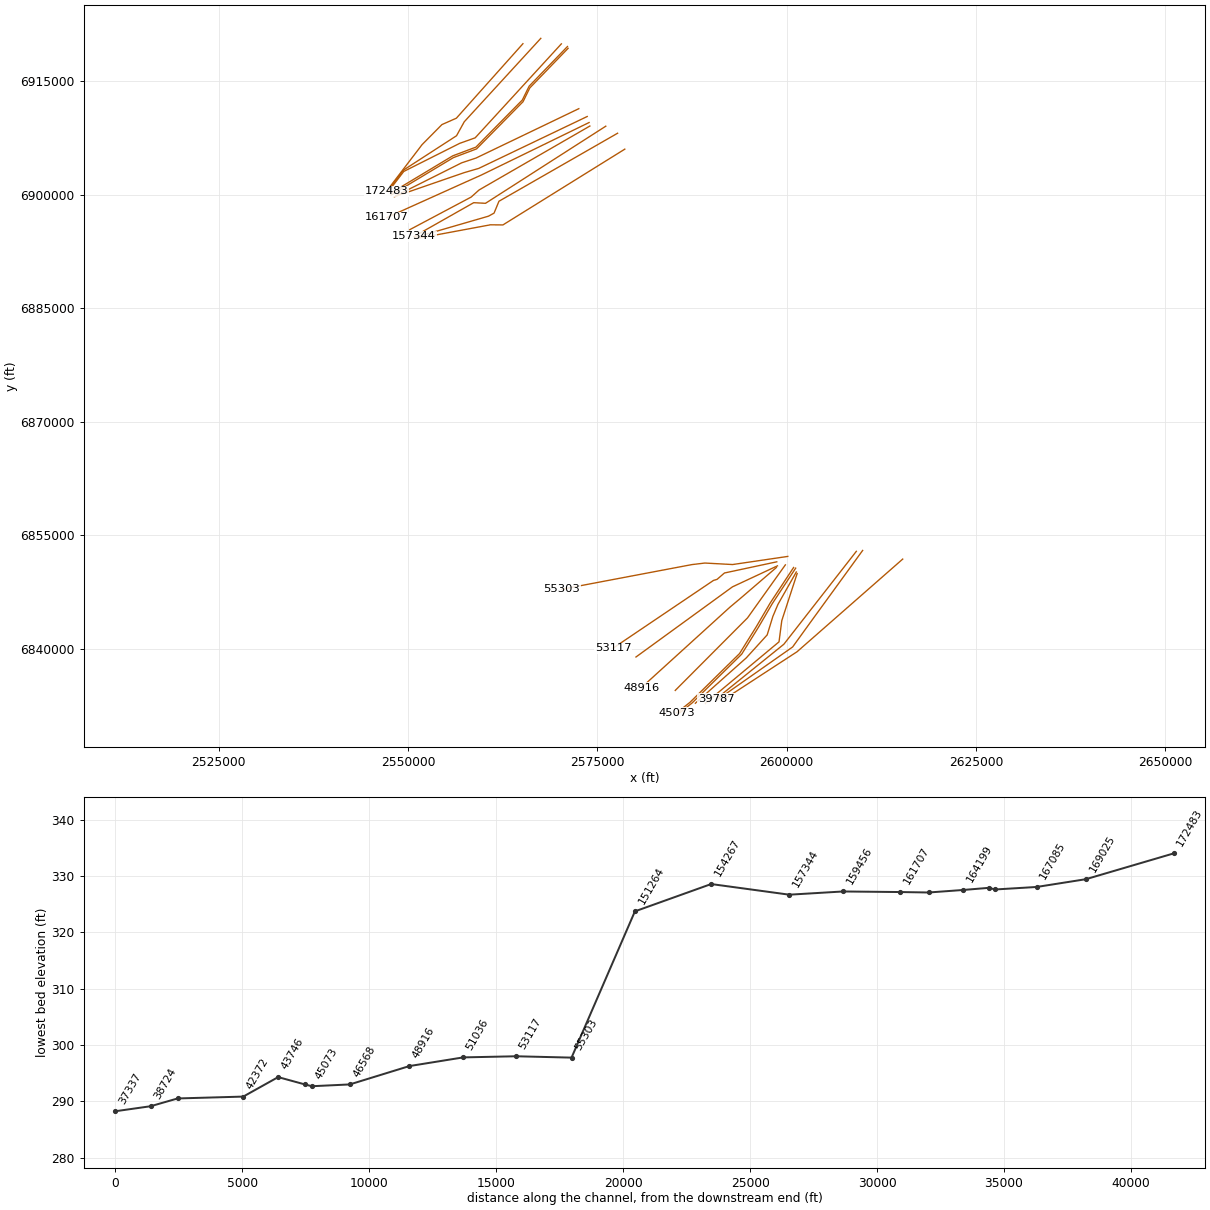
HEC-RAS study TR_FEMA.prj: Trinity_River_FEMA

--- TR_FEMA.g03 (geometry) --- (continued)

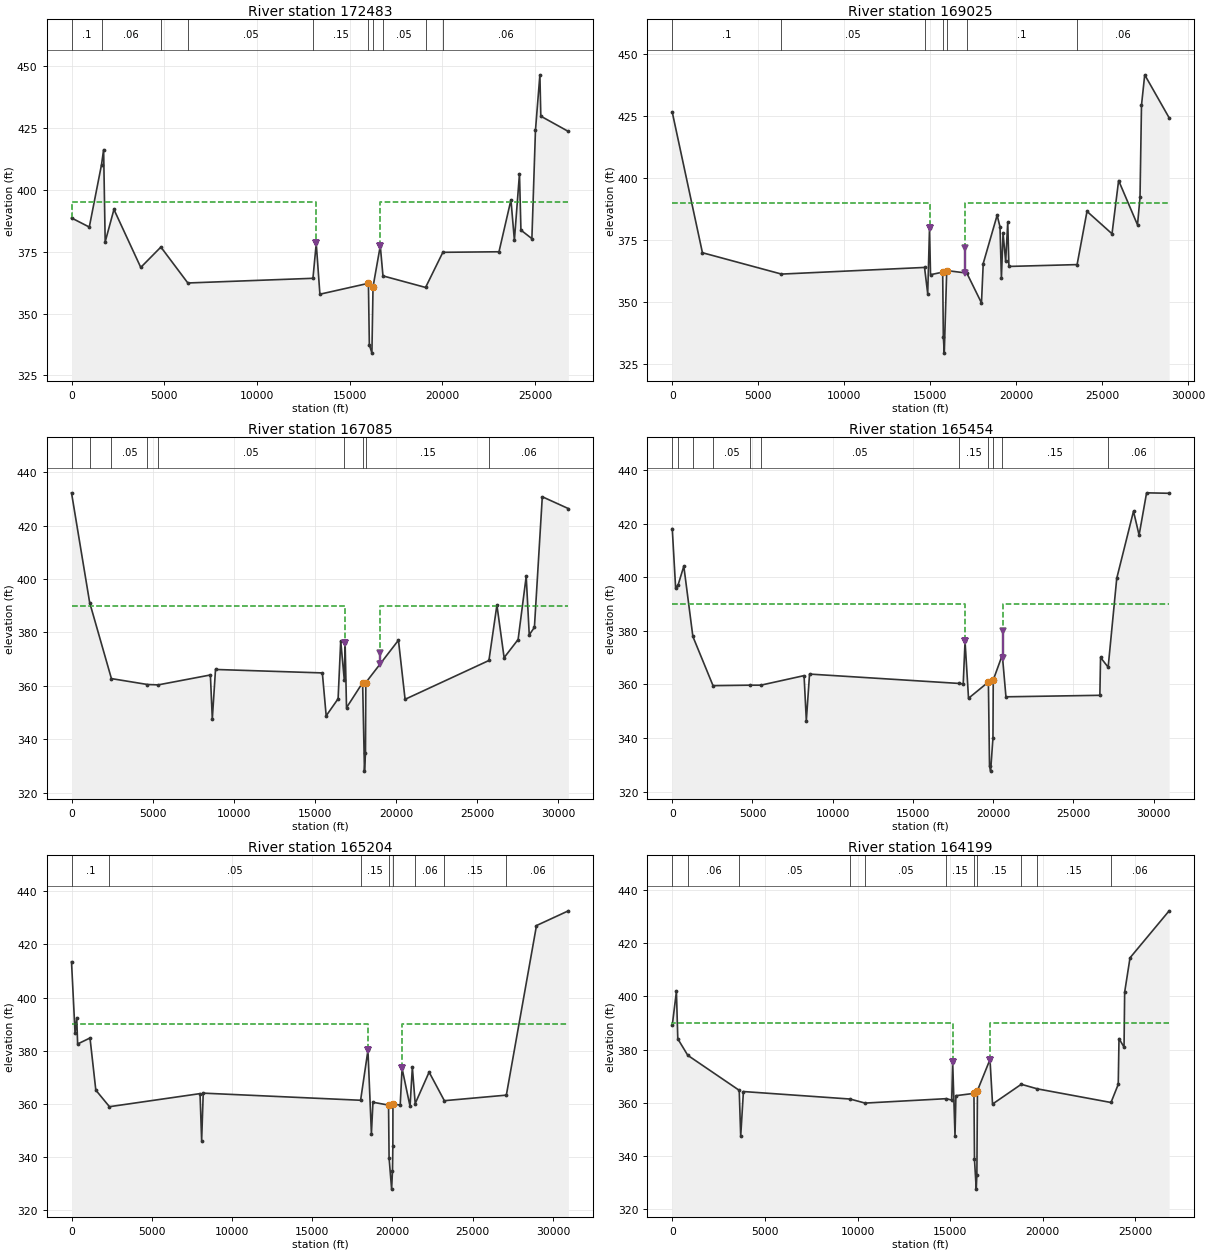
Type RM Length L Ch R = 1 ,172483  ,1181.15,3458.81,1936.55
BEGIN DESCRIPTION:
LOB - Bois D'Arc, ROB - Dallas LID1/2
END DESCRIPTION:
XS GIS Cut Line= 5
2565182.616588126919946.716008662556391.389458526910099.22201427
2554487.454273346909257.208125382551870.984643686906612.51461977
2547148.762421456900418.07017533
#Sta/Elev= 30
       0  388.58  959.04   384.9 1619.23  410.13  1731.1  416.16 1815.83  378.93
 2287.92  392.01 3734.32  368.61 4818.85  376.83 6272.44  362.33 13018.8  364.22
13195.63  378.2713393.67   357.8 16009.4   362.216059.69  337.3716197.71  334.02
16257.81  360.7516649.41  377.3216794.36  365.1919091.59  360.5320022.87  374.71
23050.08  374.9323695.19  395.8623880.43  379.5724155.03  406.4524233.05  383.67
24823.93  380.2325016.31  423.9125255.74  446.3425304.65  429.6626791.89  423.49
#Mann= 10 ,-1 , 0
       0      .1       0 1619.23     .06       0 4818.85      .1       0
 6272.44     .05       0 13018.8     .15       0 16009.4    .055       0
16257.81     .15       016794.36     .05       019091.59      .1       0
20022.87     .06       0
Levee=-1,13195.63,378.27,-1,16649.41,377.32,,
#XS Ineff= 2 ,-1
       013195.63     39516649.4126791.89     395
Permanent Ineff=
       F       F
Bank Sta=16009.4,16257.81
XS Rating Curve= 0 ,0
Exp/Cntr=0.3,0.1

Type RM Length L Ch R = 1 ,169025  ,2540.16,1939.9,813.21
BEGIN DESCRIPTION:
LOB - Bois D'Arc, ROB - Dallas LID1/2
END DESCRIPTION:
XS GIS Cut Line= 5
2567543.277467766920656.860684622557438.775976456909634.40268566
2556412.387087566907779.541574552549440.672143686903262.27156422
2547322.616588126900463.66045311
#Sta/Elev= 30
       0  426.44 1754.32  369.86 6351.27  361.2614668.24  363.9414853.24  353.36
14957.67  379.6315017.11  361.02 15723.6  362.0415760.87  336.0915816.71  329.44
 15958.5  362.68 17127.3  361.6617979.41  349.6518080.67  365.5218889.65  384.95
19055.78  380.2919138.18  359.6719233.91  377.7519385.28  366.4119506.69  382.12
19574.07  364.3423539.21  365.0824114.59  386.5125569.27  377.4925952.78  398.93
27051.51  381.0927197.13  392.1327283.32  429.2327470.32  441.4828889.98  424.18
#Mann= 7 ,-1 , 0
       0      .1       0 6351.27     .05       014668.24     .15       0
 15723.6    .055       0 15958.5     .15       0 17127.3      .1       0
23539.21     .06       0
Levee=-1,14957.67,379.63,-1,17013.93,371.76,,
#XS Ineff= 2 ,-1
       014957.67     39017013.9328889.98     390
Permanent Ineff=
       F       F
Bank Sta=15723.6,15958.5
XS Rating Curve= 0 ,0
Exp/Cntr=0.3,0.1

Type RM Length L Ch R = 1 ,167085  ,1087.43,1630.75,1236.82
BEGIN DESCRIPTION:
LOB - Bois D'Arc, ROB - Dallas LID1/2
END DESCRIPTION:
XS GIS Cut Line= 5
2570255.574362936919925.554734122558876.389719376907504.55343791
2556828.766274576906773.46139785 2549444.14436596903060.88267533
 2547409.58254826900405.39565756
#Sta/Elev= 30
       0  432.25 1118.92  391.17 2460.13   362.7 4683.68  360.49 5344.28  360.35
 8561.69  364.06 8679.91  347.56 8876.83  366.1215463.17  364.8315699.37  348.77
16434.24  355.1416595.36  376.8116816.95  362.1816867.19  375.9816952.58  351.81
17946.58  361.1718059.61  328.0618122.12  334.7618143.76  361.2220154.42  377.07
20563.17  354.9525732.03  369.4826224.28  390.22 26668.4  370.5427530.81  377.32
28030.26  400.9828217.71  379.07 28536.5  381.8929022.37  430.7830630.34  426.35
#Mann= 9 ,-1 , 0
       0     .07       0 1118.92      .1       0 2460.13     .05       0
 4683.68      .1       0 5344.28     .05       016816.95     .15       0
17946.58    .055       018143.76     .15       025732.03     .06       0
Levee=-1,16867.19,375.98,-1,19010.01,372.34,,
#XS Ineff= 2 ,-1
       016867.19     39019010.0130630.34     390
Permanent Ineff=
       F       F
Bank Sta=17946.58,18143.76
XS Rating Curve= 0 ,0
Exp/Cntr=0.5,0.3

Type RM Length L Ch R = 1 ,165454  ,224.76,250.22,261.43
BEGIN DESCRIPTION:
US Bridge
LOB - Bois D'Arc, ROB - Dallas LID1/2
END DESCRIPTION:
XS GIS Cut Line= 6
2571064.517439086919575.161277432566003.753550186914334.01544409
2565110.003550176912511.793221862558975.281327946906277.24461073
2555912.086883486905121.68905517 2547692.46882796900176.72377738
#Sta/Elev= 30
       0  418.17  211.42  395.93  370.27  397.26  720.46  404.15 1284.49  377.89
 2541.58  359.53 4832.33  359.715517.479  359.718214.539  363.28 8355.23  346.47
 8555.71  363.8617874.37  360.36 18132.3  360.19 18246.3  376.0918463.09  354.82
19701.56   360.9 19770.9 329.645 19839.7 327.61719985.68  340.0420003.09  361.65
20568.99  370.9820795.05  355.3726647.99  355.9326690.77  370.0627164.25  366.42
   27700  399.6128744.54  424.6729092.81  415.7529559.32  431.5430964.49  431.37
#Mann= 11 ,-1 , 0
       0      .1       0  370.27     .07       0 1284.49      .1       0
 2541.58     .05       0 4832.33      .1       05517.479     .05       0
17874.37     .15       019701.56    .055       020003.09     .15       0
20568.99     .15       027164.25     .06       0
Levee=-1,18246.3,376.09,-1,20585.91,380,,
#XS Ineff= 2 ,-1
       0 18246.3     39020585.9130964.49     390
Permanent Ineff=
       F       F
Bank Sta=19701.56,20003.09
XS Rating Curve= 0 ,0
Exp/Cntr=0.5,0.3

Type RM Length L Ch R = 1 ,165204  ,2833.82,1004.45,1013.94
BEGIN DESCRIPTION:
DS Bridge
LOB - Bois D'Arc, ROB - Dallas LID1/2
END DESCRIPTION:
XS GIS Cut Line= 6
2571148.471632786919340.467399712566087.707743886914099.32156637
2565193.957743886912277.099344142559059.235521646906042.55073301
2555996.041077196904886.995177452547776.423021616899942.02989966
#Sta/Elev= 30
       0  413.48  221.23  386.66  325.28  392.45  381.49  382.53 1152.41  384.78
 1514.88  365.17 2364.41  358.93 8009.12  363.85 8110.32  346.16 8208.18  364.03
18015.71  361.3518473.14  380.1618689.36  348.7918785.87   360.619757.48  359.53
19790.41   339.7 19948.8 327.90720003.44 334.86320025.39  344.1720031.36  359.91
20484.38  359.5520599.72  373.3721096.56  359.0721240.92  373.6921417.91   360.1
   22285  371.9423235.21  361.1927098.06  363.2828976.79   427.1 30964.4  432.64
#Mann= 8 ,-1 , 0
       0      .1       0 2364.41     .05       018015.71     .15       0
19757.48    .055       020031.36     .15       021417.91     .06       0
23235.21     .15       027098.06     .06       0
Levee=-1,18473.14,380.16,-1,20599.72,373.37,,
#XS Ineff= 2 ,-1
       018473.14     39020599.72 30964.4     390
Permanent Ineff=
       F       F
Bank Sta=19757.48,20031.36
XS Rating Curve= 0 ,0
Exp/Cntr=0.5,0.3

Type RM Length L Ch R = 1 ,164199  ,1428.2,1367.21,1058.58
BEGIN DESCRIPTION:
LOB - Bois D'Arc, ROB - Dallas LID1/2
END DESCRIPTION:
XS GIS Cut Line= 4
2572565.59443196 6911360.62073692559008.077070836904842.65198688
2557098.354848616904203.763097992548372.084459926899827.39656934
#Sta/Elev= 30
       0  389.12  224.44  401.91   299.2  384.07  838.45  377.86 3614.19   364.7
 3694.54   347.4 3840.79  364.24 9599.25  361.4210407.14   359.914797.07  361.56
15084.37     36115135.94  375.3115261.81  347.5815310.66  362.6816284.31  363.55
16312.96  338.6816407.93  327.5316441.75  332.9916473.03  364.6117150.04  376.29
17287.03  359.5318838.98  366.9719705.71  365.2523681.46  360.1224072.29  366.94
24113.22  384.1624385.24  380.9324418.55  401.6124708.18  414.55 26818.9  432.22
#Mann= 11 ,-1 , 0
       0     .07       0  838.45     .06       0 3614.19     .05       0
 9599.25      .1       010407.14     .05       014797.07     .15       0
16284.31    .055       016473.03     .15       018838.98     .06       0
19705.71     .15       023681.46     .06       0
Levee=-1,15135.94,375.31,-1,17150.04,376.29,,
#XS Ineff= 2 ,-1
       015135.94     39017150.04 26818.9     390
Permanent Ineff=
       F       F
Bank Sta=16284.31,16473.03
XS Rating Curve= 0 ,0
Exp/Cntr=0.3,0.1

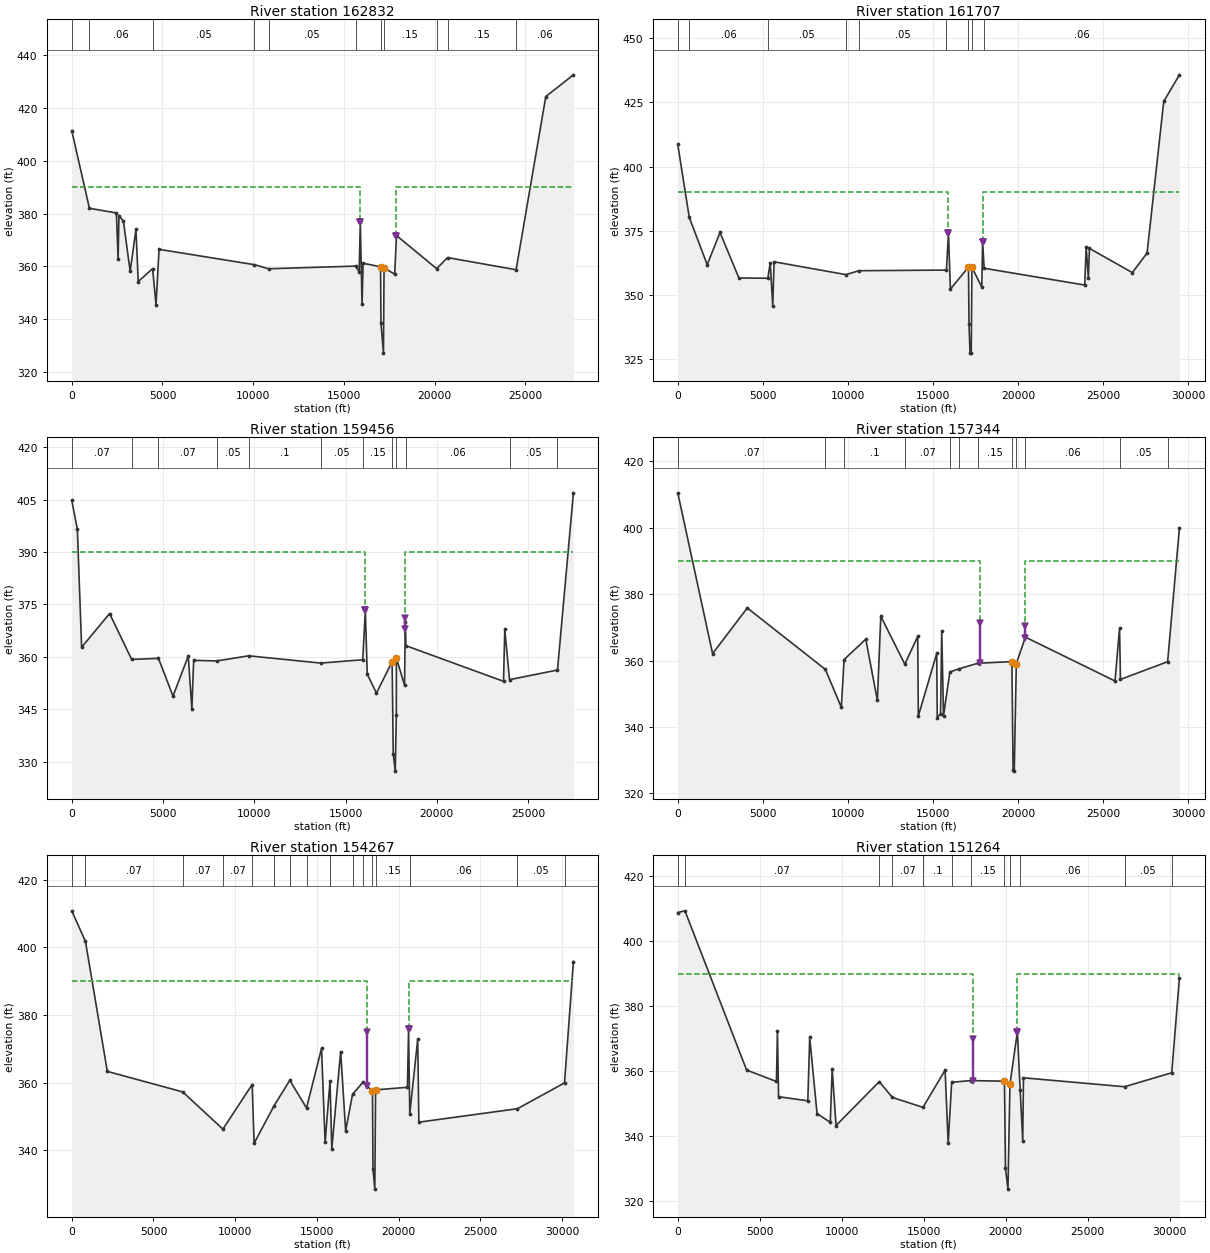
Type RM Length L Ch R = 1 ,162832  ,930.2,1125.12,1407.97
BEGIN DESCRIPTION:
LOB - Bois D'Arc, ROB - Dallas LID1/2
END DESCRIPTION:
XS GIS Cut Line= 4
2573672.057226476910324.489491232559342.144032026903463.29157455
2557416.102365356902900.791574552548203.307226456899716.85060233
#Sta/Elev= 30
       0  411.45  972.85  382.03 2460.75  380.24 2553.94  362.85 2600.63  379.25
 2848.45  377.07 3218.18  358.12 3539.16   374.1 3661.86  354.22 4454.66  359.13
 4643.12  345.45 4809.96  366.4510064.97  360.6210841.67  359.0815640.54  360.09
 15836.7  357.9115899.03  376.7915994.62  345.6716055.16  361.1517016.16  359.83
17037.44  338.4917175.73  327.0817207.69  359.4217793.92  357.0317892.38  371.69
20104.77  359.1220707.46  363.3224483.67   358.726120.06   424.427641.74  432.64
#Mann= 11 ,-1 , 0
       0     .07       0  972.85     .06       0 4454.66     .05       0
10064.97      .1       010841.67     .05       015640.54     .15       0
17016.16    .055       017207.69     .15       020104.77     .06       0
20707.46     .15       024483.67     .06       0
Levee=-1,15899.03,376.79,-1,17892.38,371.69,,
#XS Ineff= 2 ,-1
       015899.03     39017892.3827641.74     390
Permanent Ineff=
       F       F
Bank Sta=17016.16,17207.69
XS Rating Curve= 0 ,0
Exp/Cntr=0.3,0.1

Type RM Length L Ch R = 1 ,161707  ,1287.44,2251.17,2226.65
BEGIN DESCRIPTION:
LOB - Bois D'Arc, ROB - Dallas LID1/2
END DESCRIPTION:
XS GIS Cut Line= 4
 2573919.27944876909528.308935682559622.057226476902553.30893567
2557775.182226466901729.35060234 2547235.25167096896976.22560234
#Sta/Elev= 30
       0  408.66  673.33  380.22 1730.72  361.68 2484.87  374.25 3593.53   356.5
  5294.1  356.39 5435.28  362.36 5583.78  345.73 5662.01  362.81 9889.96   357.8
10646.13  359.3315796.61  359.5815913.21  374.1116027.77  352.1317091.24  360.75
17121.09  338.5217183.35  327.1617253.35  327.1617293.04  360.6817871.87  352.93
17921.79  370.6318010.71  360.2923925.79  353.7324009.32  368.6724137.73  356.47
24200.98  368.0426724.05  358.5927590.31  366.2428570.23  425.41 29492.4  435.79
#Mann= 9 ,-1 , 0
       0     .07       0  673.33     .06       0  5294.1     .05       0
 9889.96      .1       010646.13     .05       015796.61     .15       0
17091.24    .055       017293.04     .15       018010.71     .06       0
Levee=-1,15913.21,374.11,-1,17921.79,370.63,,
#XS Ineff= 2 ,-1
       015913.21     39017921.79 29492.4     390
Permanent Ineff=
       F       F
Bank Sta=17091.24,17293.04
XS Rating Curve= 0 ,0
Exp/Cntr=0.3,0.1

Type RM Length L Ch R = 1 ,159456  ,1796.97,2111.7,856.13
BEGIN DESCRIPTION:
LOB - Bois D'Arc, ROB - Dallas LID1/2
END DESCRIPTION:
XS GIS Cut Line= 4
2574022.578059816909063.899213462559391.791022766900614.24643568
2558348.966948696899676.746435672550237.855837576895365.98254678
#Sta/Elev= 30
       0  404.85   307.8  396.52  540.76  362.74 2072.69   372.4  3282.1  359.26
 4750.08  359.57  5546.9  348.75 6383.02  360.23 6580.04  345.05  6680.2  358.99
  7953.6  358.83 9688.69  360.2913642.18  358.2115942.82  359.1716083.73  373.43
16189.08  355.0216691.93  349.6317550.99  358.5817613.52  332.1917722.64  327.26
17780.74  343.2917786.32  359.6118232.31  351.8818272.77  369.9518310.25  363.19
23654.16  352.9823722.66  367.87 23983.2  353.4626610.13  356.2227483.23  406.98
#Mann= 12 ,-1 , 0
       0     .07       0  3282.1     .06       0 4750.08     .07       0
  7953.6     .05       0 9688.69      .1       013642.18     .05       0
15942.82     .15       017550.99    .055       017786.32     .15       0
18310.25     .06       0 23983.2     .05       026610.13     .06       0
Levee=-1,16083.73,373.43,-1,18283.99,371.07,,
#XS Ineff= 2 ,-1
       016083.73     39018283.9927483.23     390
Permanent Ineff=
       F       F
Bank Sta=17550.99,17786.32
XS Rating Curve= 0 ,0
Exp/Cntr=0.3,0.1

Type RM Length L Ch R = 1 ,157344  ,948.05,3077.14,2486.59
BEGIN DESCRIPTION:
LOB - Bois D'Arc, ROB - Dallas LID1/2
END DESCRIPTION:
XS GIS Cut Line= 4
2576124.256300566909043.413102352560240.402133886898849.66310234
2558682.068800546898932.996435672550808.120060356894467.16161053
#Sta/Elev= 30
       0  410.53 2046.93  362.09 4085.18  375.84 8675.15  357.34 9612.65  345.92
 9776.27   360.311051.82  366.4511732.16  347.9811932.42  373.3613343.42  358.91
14104.43  367.2614140.35  343.2815220.16  362.1415252.47  342.7815444.82  344.04
   15515   368.915619.05  343.3915994.19  356.5616544.95  357.5317624.69  359.18
19638.15  359.6919708.99  327.0119777.38  326.6919898.87  359.0920434.58  367.06
 25698.6  353.8425966.05  369.68 26020.1  354.3228793.51  359.66 29486.2  399.98
#Mann= 12 ,-1 , 0
       0     .07       0 8675.15     .07       0 9776.27      .1       0
13343.42     .07       015994.19     .05       016544.95     .07       0
17624.69     .15       019638.15    .055       019898.87     .15       0
20434.58     .06       0 26020.1     .05       028793.51     .06       0
Levee=-1,17774.12,371.28,-1,20414.93,370.51,,
#XS Ineff= 2 ,-1
       017774.15     39020414.93 29486.2     390
Permanent Ineff=
       F       F
Bank Sta=19638.15,19898.87
XS Rating Curve= 0 ,0
Exp/Cntr=0.3,0.1

Type RM Length L Ch R = 1 ,154267  ,2928.63,3003.32,1020.6
BEGIN DESCRIPTION:
LOB - Bois D'Arc, ROB - Dallas LID1/2
END DESCRIPTION:
XS GIS Cut Line= 5
2577683.119930486908112.994882482562017.311695226899122.99645831
2561369.395340146897553.204650392560632.806918296897148.53059098
2550948.498531046894340.13036789
#Sta/Elev= 30
       0   410.8  837.14  401.79 2176.36  363.36 6785.31   357.3 9245.48  346.31
11036.79  359.4911152.87  342.1312375.82  353.2213335.26  360.7214359.38  352.55
15278.67  370.1915496.36  342.3815796.75  360.5815905.35  340.5616448.28  369.19
 16753.2  345.7617172.32  356.5717799.81   360.118394.04  357.59 18423.7  334.59
18536.48  328.5818584.13  357.9120530.15  358.6620600.43  375.7620675.41  350.89
21160.32  372.8521230.31  348.3627259.18  352.3430138.64  359.9630683.54  395.82
#Mann= 16 ,-1 , 0
       0     .07       0  837.14     .07       0 6785.31     .07       0
 9245.48     .07       011036.79      .1       012375.82     .07       0
13335.26      .1       014359.38     .07       015796.75      .1       0
17172.32     .07       017799.81     .15       018394.04    .055       0
18584.13     .15       020675.41     .06       027259.18     .05       0
30138.64     .06       0
Levee=-1,18057.04,375.03,-1,20600.43,375.76,,
#XS Ineff= 2 ,-1
       018057.04     39020600.4330683.54     390
Permanent Ineff=
       F       F
Bank Sta=18394.04,18584.13
XS Rating Curve= 0 ,0
Exp/Cntr=0.3,0.1

Type RM Length L Ch R = 1 ,151264  ,621.55,2495.98,3306.68
BEGIN DESCRIPTION:
LOB - Bois D'Arc, ROB - Dallas LID1/2
END DESCRIPTION:
XS GIS Cut Line= 5
 2578634.50910386906008.828159062562540.853627156895992.51026523
2560824.186784896896009.176898552560782.641592386895987.49255873
2551073.515013316894178.02144015
#Sta/Elev= 30
       0  408.76  437.28  409.29 4197.57  360.34 6017.73  356.82 6077.77   372.2
 6148.51  352.14 7931.23  350.88 8046.75  370.36 8495.57  346.93  9301.6  344.28
 9417.25  360.68 9653.25  343.2912288.91  356.7713090.76  351.9214954.12  348.87
16304.17  360.3216491.45  337.9316705.35  356.5817869.34   357.119925.13  356.92
19985.24  330.1520138.63  323.7320258.42  355.9620714.75  372.1520879.38  354.32
21039.31  338.5921084.29  357.9627246.89  355.2130125.76   359.530595.58  388.68
#Mann= 12 ,-1 , 0
       0     .07       0  437.28     .07       012288.91      .1       0
13090.76     .07       014954.12      .1       016705.35     .07       0
17869.34     .15       019925.13    .055       020258.42     .15       0
20879.38     .06       027246.89     .05       030125.76     .06       0
Levee=-1,17986.26,369.76,-1,20714.75,372.15,,
#XS Ineff= 2 ,-1
       017986.26     39020714.7530595.58     390
Permanent Ineff=
       F       F
Bank Sta=19925.13,20258.42
XS Rating Curve= 0 ,0
Exp/Cntr=0.3,0.1

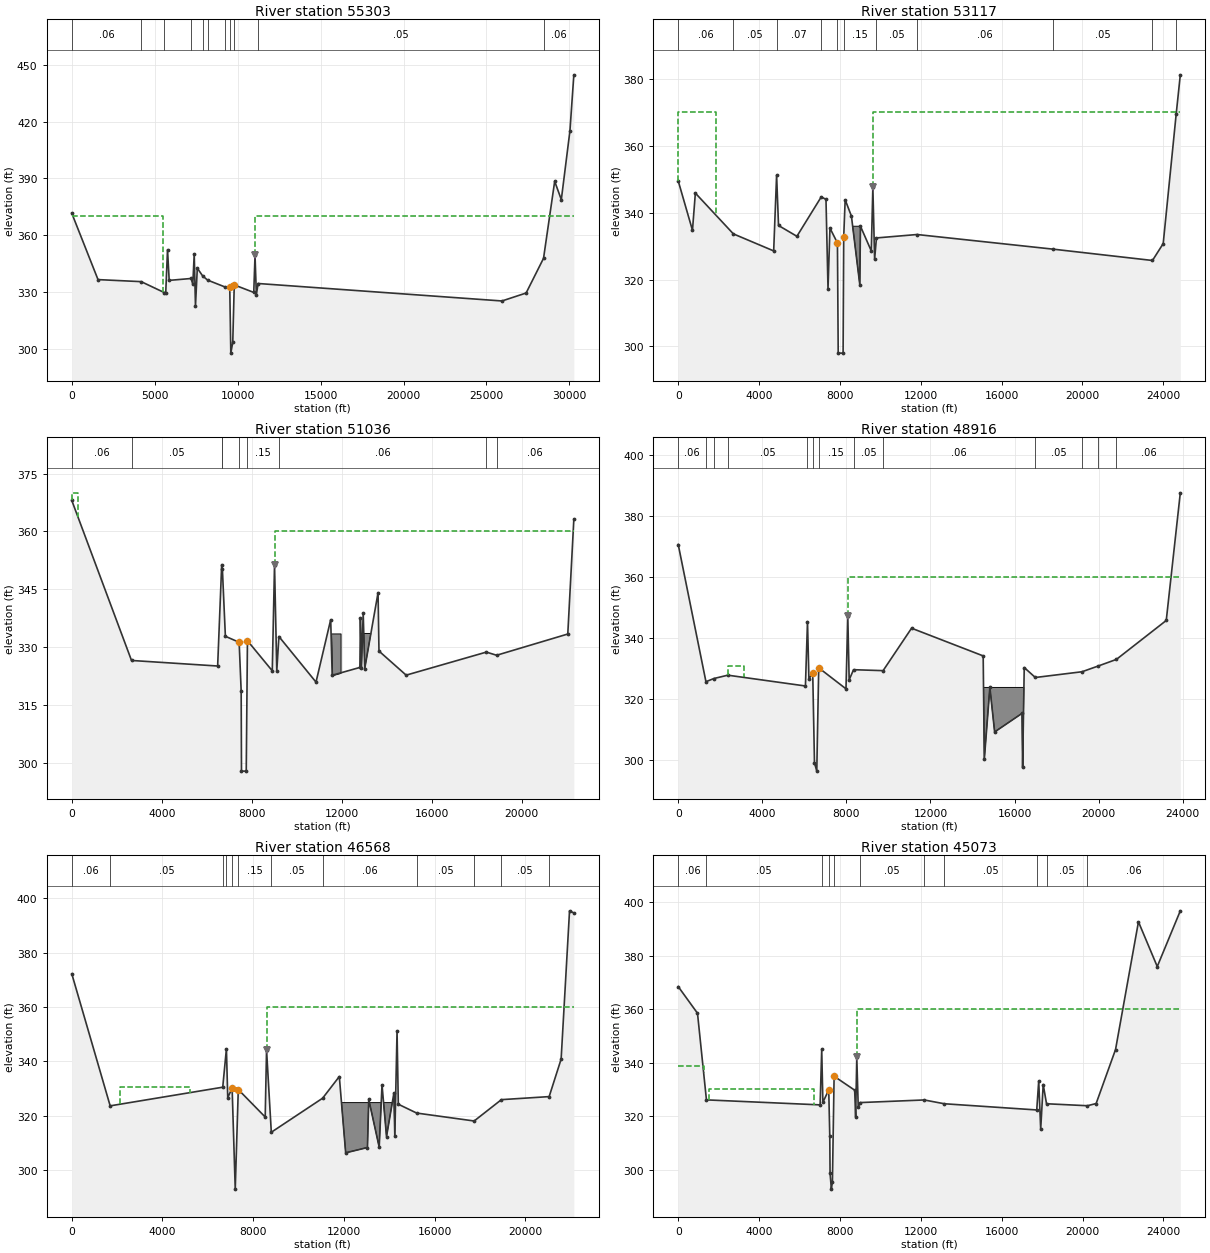
Type RM Length L Ch R = 1 ,55303   ,1445.25,2185.82,5056.24
BEGIN DESCRIPTION:
ROB - Ellis LID2
LOB IFA station 5498: flow expansion due to Kaufman MUD1 levee upstream
END DESCRIPTION:
XS GIS Cut Line= 5
2600163.400754836852175.874097612592870.282117796851101.55589129
2589209.171006686851298.778113522587475.789913646851091.50307786
2570298.522858526847833.26885425
#Sta/Elev= 30
       0  371.61 1581.82  336.57 4183.88  335.49 5588.81  329.68 5664.35  329.61
 5772.52  352.37 5872.48  336.16 7191.94  337.15  7296.9  334.13 7381.86   350.1
 7457.67  322.57 7567.84   342.6 7884.38  338.58 8186.46  336.31 9217.52  332.75
  9523.9  332.52 9587.79  297.76 9704.98  303.41  9795.5  333.7710971.24   329.8
11047.28  349.3511128.37  328.5511231.58  334.5125935.46  325.2927390.41  329.49
28440.88  347.8229112.58  388.4429512.27  378.7730032.44  415.15 30267.6  444.65
#Mann= 11 ,-1 , 0
       0     .06       0 4183.88     .05       0 5588.81     .07       0
 7191.94      .1       0 7884.38     .07       0 8186.46     .15       0
 9217.52     .05       0  9523.9    .055       0  9795.5     .15       0
11231.58     .05       028440.88     .06       0
Levee=0,,,-1,11047.28,349.35,,
#XS Ineff= 2 ,-1
       0    5498     37011047.36 30267.6     370
Permanent Ineff=
       F       F
Bank Sta=9523.9,9795.5
XS Rating Curve= 0 ,0
Exp/Cntr=0.3,0.1

Type RM Length L Ch R = 1 ,53117   ,2370.77,2080.68,2424.78
BEGIN DESCRIPTION:
ROB - Ellis LID2
LOB IFA station 1882: flow expansion due to Kaufman MUD1 levee upstream
END DESCRIPTION:
XS GIS Cut Line= 5
  2598702.505271 6851461.5101835 2591793.5662614 6849984.0356367
 2590815.2676502 6849141.1536922 2590348.3386047 6849003.1768502
 2577092.3232486 6840049.7655826
#Sta/Elev= 30
       0  349.46  704.03  334.71  847.03  345.83 2727.64  333.64 4721.89  328.55
 4866.64  351.19 4961.57  336.15 5870.93  332.92 7075.07  344.69 7309.78  343.96
 7409.86  317.28  7506.3  335.36 7876.59  330.93 7914.65     298 8156.42     298
 8186.86  332.75 8258.81  343.84 8568.46  338.95 8983.23  318.44 9015.18  335.93
 9551.19  328.54 9628.53  347.66 9715.98  326.05  9806.7  332.4311814.35  333.45
18525.39  329.0923461.93  325.6923993.63  330.7424635.51  369.4524839.83  381.18
#Mann= 11 ,-1 , 0
       0     .06       0 2727.64     .05       0 4866.64     .07       0
 7075.07     .15       0 7876.59    .055       0 8186.86     .15       0
  9806.7     .05       011814.35     .06       018525.39     .05       0
23461.93      .1       024635.51     .06       0
Levee=0,,,-1,9628.53,347.66,,
#XS Ineff= 2 ,-1
       0    1882     370 9628.5824839.83     370
Permanent Ineff=
       F       F
#Block Obstruct= 1 ,-1
 8274.12  9015.8  335.93
Bank Sta=7876.59,8186.86
XS Rating Curve= 0 ,0
Exp/Cntr=0.3,0.1

Type RM Length L Ch R = 1 ,51036   ,2003.75,2119.69,2544.85
BEGIN DESCRIPTION:
ROB - Ellis LID2
END DESCRIPTION:
XS GIS Cut Line= 3
  2598796.934316 6850931.0148033 2592849.0176502 6848149.7648033
 2580108.8727335  6838879.246163
#Sta/Elev= 30
       0  368.03 2655.86  326.51 6485.69  325.07 6666.02  351.37    6696  350.24
 6829.57  332.78 7441.54  331.22 7531.66  318.56 7545.45   297.8 7756.97   297.8
 7810.45  331.64 8914.66  323.82 9014.57  351.34 9114.73  323.79 9209.35  332.72
 10858.6  320.8911511.65  337.0911578.09  322.6712809.38   324.712832.91  337.47
12878.71  324.6412957.17  338.7713025.04  324.4213617.67  344.1113657.95  328.95
14866.75   322.718432.44  328.6818889.25  327.8622052.62  333.3722322.13  363.14
#Mann= 9 ,-1 , 0
       0     .06       0 2655.86     .05       0 6666.02     .15       0
    6696     .07       0 7441.54    .055       0 7810.45     .15       0
 9209.35     .06       018432.44     .05       018889.25     .06       0
Levee=0,,,-1,9014.57,351.34,,
#XS Ineff= 2 ,-1
       0     271     370 9014.6422322.13     360
Permanent Ineff=
       F       F
#Block Obstruct= 2 ,-1
11511.6511950.64  333.5212832.9113617.67  333.52
Bank Sta=7441.54,7810.45
XS Rating Curve= 0 ,0
Exp/Cntr=0.3,0.1

Type RM Length L Ch R = 1 ,48916   ,2124.59,2348.27,2946.84
BEGIN DESCRIPTION:
ROB - Ellis LID2
END DESCRIPTION:
XS GIS Cut Line= 4
   2598649.01765 6850708.0981367 2593949.0176502   6846666.43147
 2592504.5732058 6845455.3203589 2580815.6843169 6834824.7648033
#Sta/Elev= 30
       0  370.67 1318.05  325.63 1699.02  326.68 2359.33  327.77 6050.61  324.22
 6148.76  345.36 6216.82  326.62 6398.52  328.34 6480.95  298.98 6590.29  296.26
 6682.71  330.19 7979.77  323.29 8065.83  347.16  8131.5  326.25 8339.73  329.57
 9745.12  329.2611099.58   343.214506.32   334.114560.31  300.1614824.53  323.75
15051.16  309.1216353.98  315.2316382.98  297.5116458.92  330.2816987.79  327.01
   19209   328.919961.17  330.7420843.19  332.9523214.96  345.7423883.86  387.66
#Mann= 13 ,-1 , 0
       0     .06       0 1318.05     .05       0 1699.02     .06       0
 2359.33     .05       0 6148.76     .09       0 6398.52    .055       0
 6682.71     .15       0 8339.73     .05       0 9745.12     .06       0
16987.79     .05       0   19209     .06       019961.17     .05       0
20843.19     .06       0
Levee=0,,,-1,8065.83,347.16,,
#XS Ineff= 2 ,-1
    2370    3122   330.8 8065.8923883.86     360
Permanent Ineff=
       F       F
#Block Obstruct= 1 ,-1
14499.6916528.76  323.75
Bank Sta=6398.52,6682.71
XS Rating Curve= 0 ,0
Exp/Cntr=0.3,0.1

Type RM Length L Ch R = 1 ,46568   ,1363.21,1495.23,2484.31
BEGIN DESCRIPTION:
ROB - Ellis LID2
END DESCRIPTION:
XS GIS Cut Line= 4
  2599838.304108 6851059.0992941 2595879.8405669 6845507.4499885
 2594848.5905669 6844057.4499885 2585296.6374419 6834461.8770718
#Sta/Elev= 30
       0  372.21 1692.95  323.63 6656.27  330.49 6818.38   344.6 6877.16  326.62
 7069.87   330.2 7207.75     293 7341.88  329.63 8528.83  319.52 8587.94  344.22
 8797.84  313.9211060.18  326.4411796.41  334.4112076.85  306.3513037.44  308.31
13093.66  325.9913555.12  308.4313679.19  331.3513877.93  312.3414203.31  328.33
14243.51  312.3814341.71  351.1414397.55  324.2315206.15  320.9817741.27  318.06
18943.17  325.9121048.57  327.0321576.53  340.8221947.04  395.3622137.24  394.58
#Mann= 12 ,-1 , 0
       0     .06       0 1692.95     .05       0 6656.27     .09       0
 6818.38     .09       0 7069.87    .055       0 7341.88     .15       0
 8797.84     .05       011060.18     .06       015206.15     .05       0
17741.27     .06       018943.17     .05       021048.57     .06       0
Levee=0,,,-1,8587.94,344.22,,
#XS Ineff= 2 ,-1
    2129    5230  330.45 8588.0422137.24     360
Permanent Ineff=
       F       F
#Block Obstruct= 1 ,-1
11801.95 14322.2  324.82
Bank Sta=7069.87,7341.88
XS Rating Curve= 0 ,0
Exp/Cntr=0.5,0.3

Type RM Length L Ch R = 1 ,45073   ,345.39,280.26,285.37
BEGIN DESCRIPTION:
US Bridge
ROB - Ellis LID2
END DESCRIPTION:
XS GIS Cut Line= 6
  2600926.770416 6850712.1886244 2597846.9093053 6846038.5775133
 2596030.9370831 6842936.1469578 2593793.0898608 6839338.9247355
 2587239.1402081 6832884.5844578  2585513.575972 6831516.0080689
#Sta/Elev= 30
       0  368.47  952.76   358.5 1395.06  326.08 7018.46  324.21 7097.09  344.94
 7154.81  325.17 7444.93  329.81 7496.13  312.38 7510.31   298.7 7574.28  292.68
 7626.64  295.39 7710.21  334.93 8727.83  329.71 8775.26  319.72 8831.57  341.99
 8904.04  323.35 9000.28  325.0712167.55  326.0513159.35  324.6317733.49  322.31
17831.35  333.1517929.29   315.118052.72  331.8318217.56  324.63 20241.9  323.89
20671.26  324.7121631.78  344.9322764.77  392.7223694.75  375.9824835.29  396.83
#Mann= 11 ,-1 , 0
       0     .06       0 1395.06     .05       0 7097.09     .09       0
 7444.93    .055       0 7710.21     .15       0 9000.28     .05       0
12167.55     .06       013159.35     .05       017733.49     .06       0
18217.56     .05       0 20241.9     .06       0
Levee=0,,,-1,8831.57,341.99,,
#XS Ineff= 3 ,-1
       0    1260   338.8    1532    6738     330 8831.5824835.29     360
Permanent Ineff=
       F       F       F
Bank Sta=7444.93,7710.21
XS Rating Curve= 0 ,0
Exp/Cntr=0.5,0.3

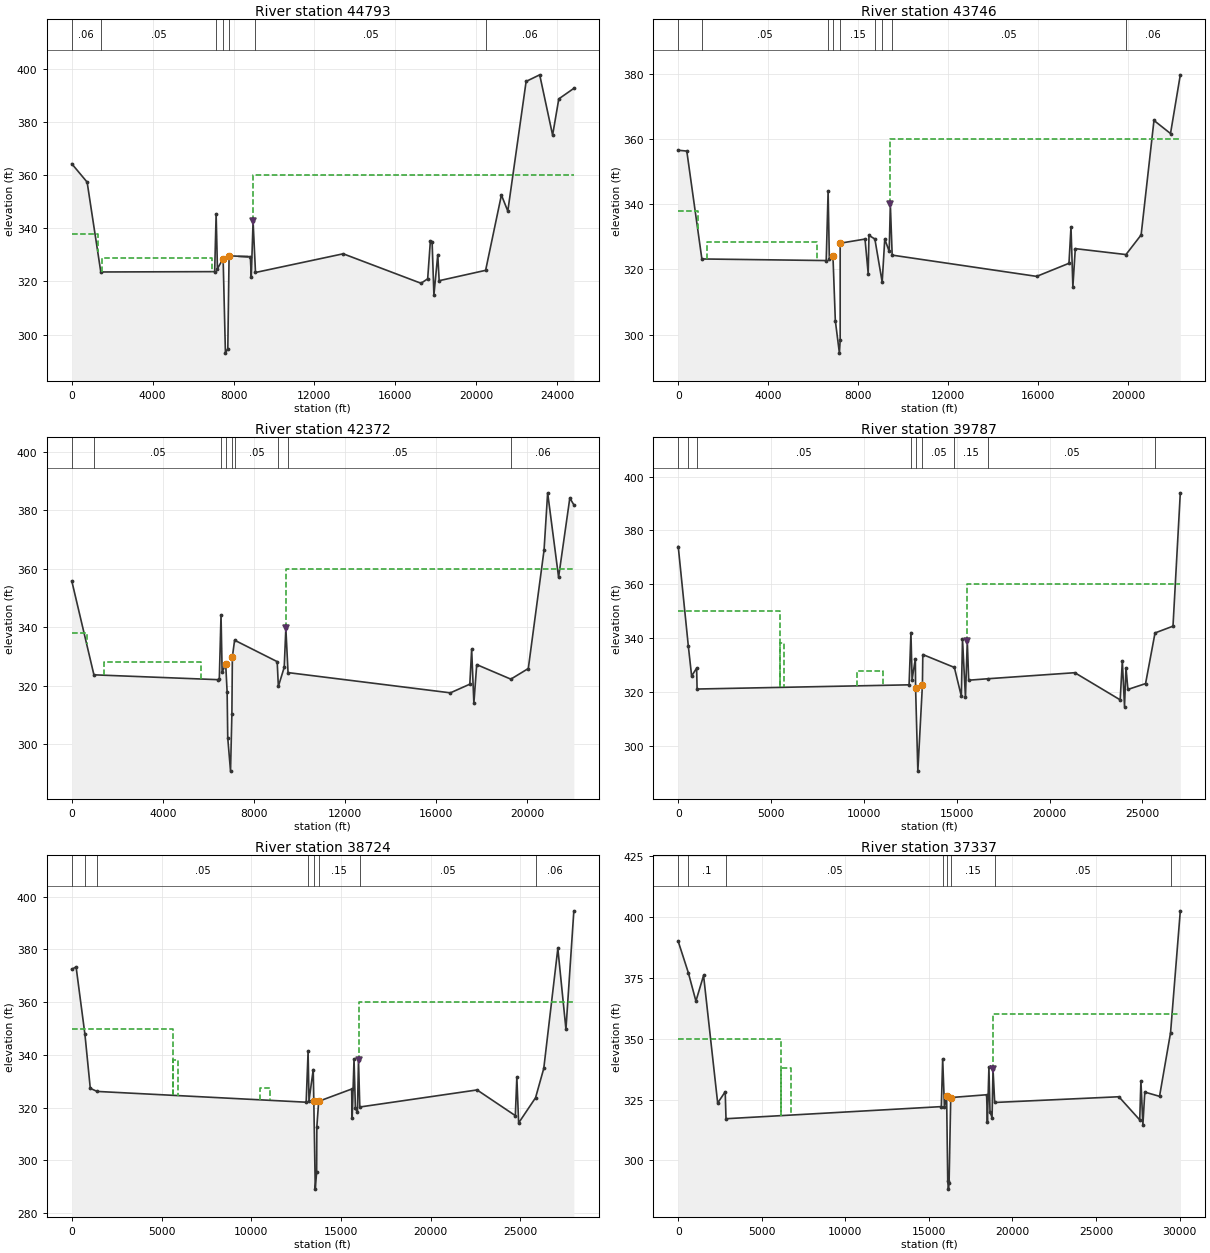
Type RM Length L Ch R = 1 ,44793   ,681.19,1046.32,1063.06
BEGIN DESCRIPTION:
DS Bridge
ROB - Ellis LID2
END DESCRIPTION:
XS GIS Cut Line= 6
   2601201.10032 6850624.5597711 2598121.2392092 6845950.9486599
  2596305.266987 6842848.5181044 2594067.4197648 6839251.2958822
  2587513.470112 6832796.9556044 2585787.9058759 6831428.3792155
#Sta/Elev= 30
       0  364.25   759.9  357.34 1436.19  323.54 7068.61  323.67 7141.11  345.37
 7205.66  324.75 7486.92   328.6 7600.77  293.01 7718.76   294.7  7781.3  329.62
    8834  329.28 8879.09  321.72 8968.54  342.65 9087.95  323.3513426.66  330.38
17275.59  319.2917604.55  320.9617738.86  335.2717824.38  334.8817912.77  314.86
 18104.1  330.0518172.89  320.2620471.14  324.1621252.55  352.49 21568.6  346.44
22474.59  395.2323146.12  397.71 23784.5  375.0324091.36  388.66 24835.2  392.62
#Mann= 7 ,-1 , 0
       0     .06       0 1436.19     .05       0 7141.11     .09       0
 7486.92    .055       0  7781.3     .09       0 9087.95     .05       0
20471.14     .06       0
Levee=0,,,-1,8968.54,342.65,,
#XS Ineff= 3 ,-1
       0    1286     338    1505    6920  328.75 8968.42 24835.2     360
Permanent Ineff=
       F       F       F
#Block Obstruct= 1 ,-1
 8212.59 8693.81  329.65
Bank Sta=7486.92,7781.3
XS Rating Curve= 0 ,0
Exp/Cntr=0.5,0.3

Type RM Length L Ch R = 1 ,43746   ,782.09,1374.19,1573.74
BEGIN DESCRIPTION:
ROB - Ellis LID2
END DESCRIPTION:
XS GIS Cut Line= 6
   2601283.10594 6850114.9713198 2598849.7726067 6845814.9713198
 2598184.1374419 6844234.0992941 2597436.9152197 6841800.7659607
 2594688.5818863 6838775.3546181 2587952.4707752 6832768.4101737
#Sta/Elev= 30
       0  356.61  380.29  356.35 1050.35  323.22 6576.81  322.73 6661.05  343.98
 6716.36  323.28  6875.8  324.22 6981.87  304.26 7163.12   294.3 7197.19  298.26
 7197.37  328.06 8301.69  329.33 8441.93  318.73 8476.98  330.45  8738.5  329.36
 9064.25  316.11 9178.61  329.34 9376.07  325.53 9426.74  340.03 9508.31   324.4
15930.02  317.8717366.23  321.8917455.67  333.0817539.51  314.6417646.76  326.39
19899.45  324.5720572.74   330.6 21143.6  365.7621878.84  361.7422314.38  379.77
#Mann= 9 ,-1 , 0
       0     .06       0 1050.35     .05       0 6661.05     .15       0
  6875.8    .055       0 7197.37     .15       0  8738.5     .05       0
 9064.25     .15       0 9508.31     .05       019899.45     .06       0
Levee=0,,,-1,9426.74,340.03,,
#XS Ineff= 3 ,-1
       0     863     338    1285    6165  328.55 9426.7622314.38     360
Permanent Ineff=
       F       F       F
Bank Sta=6875.8,7197.37
XS Rating Curve= 0 ,0
Exp/Cntr=0.3,0.1

Type RM Length L Ch R = 1 ,42372   ,3867.9,2585.3,725.77
BEGIN DESCRIPTION:
ROB - Ellis LID2
END DESCRIPTION:
XS GIS Cut Line= 4
  2601396.573784 6849917.6173496 2599366.7616801 6843692.2464785
 2599000.7404511 6840882.8951274 2589275.7404511 6832767.6173496
#Sta/Elev= 30
       0  355.87  972.79  323.77 6428.02  322.11 6478.47  322.31 6553.92  344.26
 6602.77   324.7 6759.83  327.34 6822.67   317.8 6849.05  302.22 6971.62  290.84
 7031.24  310.42 7052.39  329.93  7150.5  335.61 9020.06  328.28 9072.11  319.82
 9329.57  326.35 9400.68  339.72 9496.65  324.5316625.65  317.6117479.32  320.57
17559.79   332.5 17657.4  314.0417781.89  327.26 19280.6  322.2920047.19  325.92
20739.15  366.4420896.72     38621377.12  357.1521870.54  384.2222047.19   381.9
#Mann= 9 ,-1 , 0
       0     .06       0  972.79     .05       0 6553.92     .15       0
 6759.83    .055       0 7052.39     .15       0  7150.5     .05       0
 9072.11     .15       0 9496.65     .05       0 19280.6     .06       0
Levee=0,,,-1,9400.68,339.72,,
#XS Ineff= 3 ,-1
       0     656     338    1420    5671   328.2 9401.3522047.19     360
Permanent Ineff=
       F       F       F
Bank Sta=6759.83,7052.39
XS Rating Curve= 0 ,0
Exp/Cntr=0.3,0.1

Type RM Length L Ch R = 1 ,39787   ,892.19,1062.65,1007.03
BEGIN DESCRIPTION:
ROB - Ellis LID2
LOB IFA station 5469: flow expansion due to natural high ground upstream
END DESCRIPTION:
XS GIS Cut Line= 3
  2609212.137262 6852849.0371331 2599638.6514077 6840565.1583585
 2590714.0585588 6833359.5000961
#Sta/Elev= 30
       0  374.03  543.82     337  721.29  325.87  990.94   328.8 1015.82  321.04
 12434.1   322.6   12535  342.0312595.48  324.5712773.05   332.312785.25   321.5
12906.56  290.5113152.72   322.613173.96  333.8714873.87  329.0715249.02  318.38
15311.54  339.5715471.06  317.96   15570  338.8615645.78  324.3216688.86  324.87
21361.63  327.1123805.59  317.01   23921  331.5624038.68  314.5324117.98  328.97
24220.47  320.8825172.64  323.0625681.99  341.8926650.31  344.4227044.21     394
#Mann= 9 ,-1 , 0
       0     .06       0  543.82      .1       0  990.94     .05       0
   12535     .15       012785.25    .055       013152.72     .05       0
14873.87     .15       016688.86     .05       025681.99     .06       0
Levee=0,,,-1,15570,338.86,,
#XS Ineff= 4 ,-1
       0    5469     350    5469    5709     338    9607   11003   327.8
15569.0127044.21     360
Permanent Ineff=
       F       F       F       F
Bank Sta=12785.25,13152.72
XS Rating Curve= 0 ,0
Exp/Cntr=0.3,0.1

Type RM Length L Ch R = 1 ,38724   ,2589.44,1387.22,926.77
BEGIN DESCRIPTION:
ROB - Ellis LID2
LOB IFA station 5655: flow expansion due to natural high ground upstream
END DESCRIPTION:
XS GIS Cut Line= 4
   2610043.95631 6852965.4574309 2603252.0039816 6843606.0567849
 2600797.9969442 6840205.9265522  2590797.408302 6833183.5301745
#Sta/Elev= 30
       0  372.46  240.88  373.37  733.71  347.78 1031.29  327.36 1406.51  326.17
13061.28  322.0813168.51  341.34 13219.1  322.6713454.97  334.4613486.97   322.7
13568.35  289.13 13644.8  295.6113655.92  312.7313758.43  322.4215596.14  327.07
15625.02  316.0815728.31  338.3415805.02  319.7215917.31  318.2815977.76  338.15
16049.68  320.2622584.53  326.7324717.01  316.9924800.38  331.5824901.51  314.22
25843.56  323.7726302.09  334.9127085.14  380.3727536.79  349.7627977.22  394.63
#Mann= 8 ,-1 , 0
       0     .06       0  733.71      .1       0 1406.51     .05       0
13168.51     .15       013486.97    .055       013758.43     .15       0
16049.68     .05       025843.56     .06       0
Levee=0,,,-1,15977.76,338.15,,
#XS Ineff= 4 ,-1
       0    5655     350    5655    5923     338   10497   11041   327.5
15979.5627977.22     360
Permanent Ineff=
       F       F       F       F
Bank Sta=13486.97,13758.43
XS Rating Curve= 0 ,0
Exp/Cntr=0.3,0.1

Type RM Length L Ch R = 1 ,37337   ,3427.32,2177.73,1690.74
BEGIN DESCRIPTION:
ROB - Ellis LID2
LOB IFA station 6156: flow expansion due to natural high ground upstream
END DESCRIPTION:
XS GIS Cut Line= 3
  2615335.622977 6851823.7907643 2601386.6348669 6839577.7655373
 2591771.9152196 6833306.6046181
#Sta/Elev= 30
       0  389.89  601.66   377.1 1058.46  365.41 1515.82  375.93 2360.04  323.58
 2810.74  328.21 2857.44  317.1315741.77   322.115822.04  341.7515928.32  321.93
16057.47  326.4716125.44  291.57   16168  288.2416205.98  290.8716304.57  325.82
18451.41  326.9718498.33  315.9218589.38   338.218653.98  320.0118776.11  317.58
18835.12  337.37 18934.7   323.826364.29  326.1527613.66  316.6427683.05  332.72
27802.17   314.727916.74  328.0628797.64  326.3229457.16  352.4430040.95  402.45
#Mann= 8 ,-1 , 0
       0     .06       0  601.66      .1       0 2857.44     .05       0
15822.04     .15       016057.47    .055       016304.57     .15       0
 18934.7     .05       029457.16     .06       0
Levee=0,,,-1,18835.12,337.37,,
#XS Ineff= 3 ,-1
       0    6156     350    6156    6728     33818835.9830040.95     360
Permanent Ineff=
       F       F       F
Bank Sta=16057.47,16304.57
XS Rating Curve= 0 ,0
Exp/Cntr=0.3,0.1