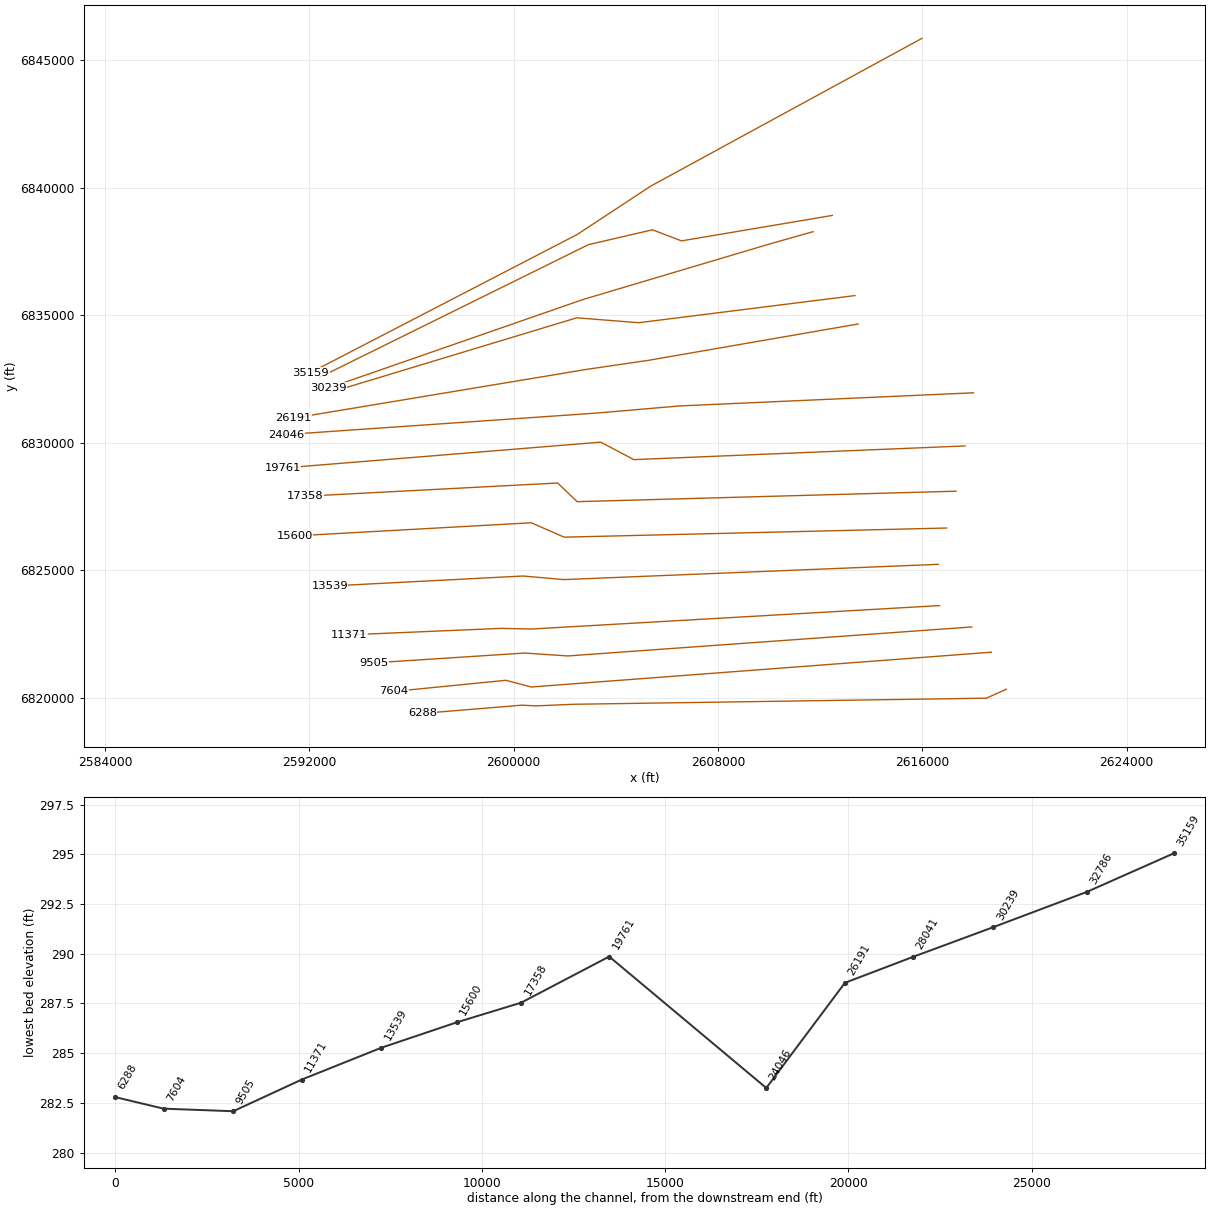
HEC-RAS study TR_FEMA.prj: Trinity_River_FEMA

--- TR_FEMA.g03 (geometry) --- (continued)

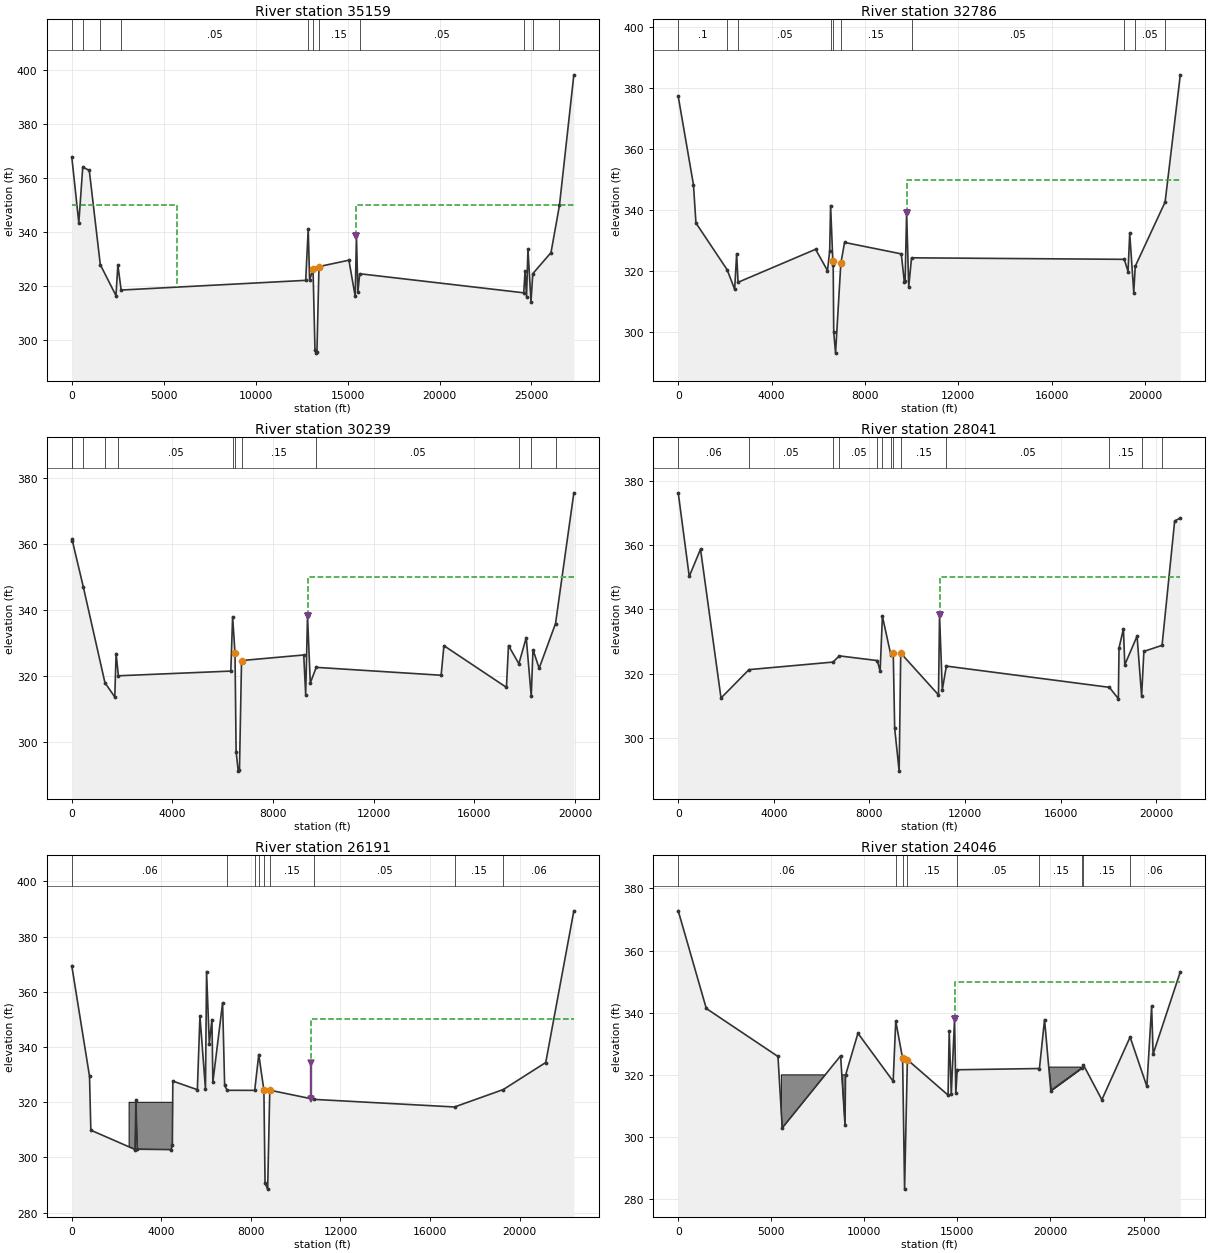
Type RM Length L Ch R = 1 ,35159   ,3333.38,2373.47,517.22
BEGIN DESCRIPTION:
ROB - Ellis LID2
LOB IFA station 5715: flow expansion due to natural high ground upstream
END DESCRIPTION:
XS GIS Cut Line= 4
   2615990.11631 6845847.5727087 2605372.0607548 6840058.6838198
 2602487.6690384 6838160.7157798 2592049.6929974 6832751.0490626
#Sta/Elev= 30
       0  367.84  383.55  343.38   596.9  364.04  951.99  362.81 1551.25  327.86
 2404.04  316.38 2506.63  327.68 2685.93  318.4412722.47  322.0412857.72  341.16
12934.03  322.1713119.58  326.26 13225.6  296.15 13282.3  295.0513332.27  295.53
13443.18  327.1415069.93  329.5115413.88  316.0815480.15  338.6415558.94  317.61
15656.95  324.4924576.89  317.4224649.26  325.3424730.47  315.8624807.06  333.62
24972.62  314.1725070.94  324.5226060.58  332.3326519.65  349.8127302.92  398.25
#Mann= 11 ,-1 , 0
       0      .1       0   596.9     .06       0 1551.25      .1       0
 2685.93     .05       012857.72     .15       013119.58    .055       0
13443.18     .15       015656.95     .05       024576.89     .15       0
25070.94     .05       026519.65     .06       0
Levee=0,,,-1,15480.15,338.64,,
#XS Ineff= 2 ,-1
       0    5715     35015480.2127302.92     350
Permanent Ineff=
       F       F
Bank Sta=13119.58,13443.18
XS Rating Curve= 0 ,0
Exp/Cntr=0.3,0.1

Type RM Length L Ch R = 1 ,32786   ,932.09,2546.34,1762.9
BEGIN DESCRIPTION:
ROB - Ellis LID2
END DESCRIPTION:
XS GIS Cut Line= 5
   2612477.24508 6838907.2006829   2606570.87934 6837910.0942014
 2605434.6766815 6838344.2164293 2602926.8978586 6837761.6567014
 2592404.3284141 6832563.4506829
#Sta/Elev= 30
       0  377.24   652.7  348.29  758.57  335.77 2095.92  320.44 2418.58  314.01
  2503.3   325.7 2563.95  316.33 5886.86  327.14 6395.95  320.17 6489.72  326.52
 6529.91  341.49 6625.46  323.35 6640.64  322.08 6663.42  300.01 6742.11  293.11
 6968.26  322.49  7127.6  329.39 9558.81  325.64 9688.36  316.51 9723.16  316.79
 9787.39  339.17 9877.91  314.83 9998.96  324.3519117.69  323.8519277.15  319.85
19348.81   332.419521.83  312.9719586.63  321.5820864.95  342.6221517.27  384.32
#Mann= 10 ,-1 , 0
       0      .1       0 2095.92     .06       0 2563.95     .05       0
 6529.91     .15       0 6625.46    .055       0 6968.26     .15       0
 9998.96     .05       019117.69     .15       019586.63     .05       0
20864.95     .06       0
Levee=0,,,-1,9787.39,339.17,,
#XS Ineff= 2 , 0
       0                 9787.44       0     350
Permanent Ineff=
       F       F
Bank Sta=6625.46,6968.26
XS Rating Curve= 0 ,0
Exp/Cntr=0.3,0.1

Type RM Length L Ch R = 1 ,30239   ,2121.82,2198.11,574.75
BEGIN DESCRIPTION:
ROB - Ellis LID2
END DESCRIPTION:
XS GIS Cut Line= 4
  2611724.189525 6838270.3025348 2610022.1061919 6837788.7053126
  2602711.342303  6835611.274757 2592744.1374419 6832143.4101737
#Sta/Elev= 30
       0  361.04    8.18  361.52  462.84  346.92 1317.94  318.09 1708.85  313.77
 1761.26   326.9  1852.1  320.18 6320.15   321.6  6391.5  338.05 6486.82  326.95
 6530.21  297.24 6614.31  291.34 6663.86  291.79 6746.07  324.79 9217.26  326.47
 9294.63  314.49 9367.52  338.23 9478.18  318.03 9713.62  322.7314677.13  320.34
14787.63  329.2917271.11  316.6817353.89  329.3217765.76  323.8218058.24  331.72
18257.43  313.9818326.52  328.0618571.96  322.4519222.44  335.9819950.38  375.52
#Mann= 12 ,-1 , 0
       0      .1       0    8.18     .06       0  462.84      .1       0
 1317.94     .06       0  1852.1     .05       0  6391.5     .15       0
 6486.82    .055       0 6746.07     .15       0 9713.62     .05       0
17765.76     .15       018257.43     .05       019222.44     .06       0
Levee=0,,,-1,9367.52,338.23,,
#XS Ineff= 2 , 0
       0                 9367.67       0     350
Permanent Ineff=
       F       F
Bank Sta=6486.82,6746.07
XS Rating Curve= 0 ,0
Exp/Cntr=0.3,0.1

Type RM Length L Ch R = 1 ,28041   ,1424.7,1850.02,1966.69
BEGIN DESCRIPTION:
ROB - Ellis LID2
END DESCRIPTION:
XS GIS Cut Line= 4
   2613364.12008 6835765.9043866  2604898.842303 6834703.4043866
 2602469.6756363 6834894.7238311 2592864.1200808 6831988.1266088
#Sta/Elev= 30
       0  376.19  460.84  350.26  932.26  358.71 1789.54  312.52  2958.9  321.33
  6477.9  323.68 6737.59   325.6 8331.43  324.14 8445.45  320.81 8541.68  337.89
 8891.15  326.02 8995.21  326.45  9054.8  303.11 9241.87  289.84 9307.65  326.47
10887.19   313.510931.68   338.2 11047.2  315.0111215.96  322.4318035.58  315.84
18412.18  312.3118440.22  328.0818624.09  333.9918681.23  322.8419194.99  331.74
19385.52   313.119479.95  326.9920240.48  328.8720767.51  367.4321004.03   368.4
#Mann= 13 ,-1 , 0
       0     .06       0  2958.9     .05       0  6477.9     .06       0
 6737.59     .05       0 8331.43     .06       0 8541.68     .06       0
 8891.15     .15       0 8995.21    .055       0 9307.65     .15       0
11215.96     .05       018035.58     .15       019385.52     .05       0
20240.48     .06       0
Levee=0,,,-1,10931.68,338.2,,
#XS Ineff= 2 , 0
       0                10931.05       0     350
Permanent Ineff=
       F       F
Bank Sta=8995.21,9307.65
XS Rating Curve= 0 ,0
Exp/Cntr=0.3,0.1

Type RM Length L Ch R = 1 ,26191   ,2208.75,2145.1,1627.42
BEGIN DESCRIPTION:
ROB - Ellis LID2
END DESCRIPTION:
XS GIS Cut Line= 4
  2613487.036747 6834653.0571644 2605281.5679974 6833229.0120255
 2602909.4104089 6832882.7844453 2591372.6096641 6830962.8546181
#Sta/Elev= 30
       0  369.47   792.5  329.42  851.69  309.89 2830.34  302.89 2862.46  320.93
 2924.58     303 4439.92  302.85 4492.11  304.67 4512.69  327.68 5608.19  324.55
 5723.38  351.24 5970.42  324.82    6019  367.34 6141.37  341.26  6259.7  349.97
 6300.58  327.26 6735.18  356.02 6827.04  326.08 6938.13  324.34 8169.06  324.31
 8350.68   337.3 8579.84  324.38 8630.98  290.66 8747.63  288.54 8842.51  324.38
10837.65  321.0417091.92   318.319269.76  324.6121165.59   334.422420.79  389.34
#Mann= 9 ,-1 , 0
       0     .06       0 6938.13     .05       0 8169.06     .06       0
 8350.68     .06       0 8579.84    .055       0 8842.51     .15       0
10837.65     .05       017091.92     .15       019269.76     .06       0
Levee=0,,,-1,10681.42,334.4,,
#XS Ineff= 2 , 0
       0                10681.25       0     350
Permanent Ineff=
       F       F
#Block Obstruct= 1 ,-1
  2559.9 4512.69     320
Bank Sta=8579.84,8842.51
XS Rating Curve= 0 ,0
Exp/Cntr=0.3,0.1

Type RM Length L Ch R = 1 ,24046   ,2150.45,4285.27,1243.91
BEGIN DESCRIPTION:
ROB - Ellis LID2
END DESCRIPTION:
XS GIS Cut Line= 4
  2618005.516276 6831956.4031599 2606504.9013308 6831441.7203589
 2603206.9846641 6831158.3870255 2591081.3268229 6830320.2000931
#Sta/Elev= 30
       0  372.76 1507.73  341.35 5358.95  325.91 5587.33  302.91 8724.77  326.14
 8961.27  303.85 8988.06  319.85 9656.12  333.38 11548.2  317.9411686.88  337.32
12055.11   325.312161.19  283.2512311.37  324.8814497.88  313.4914558.98  334.14
14670.65  313.8414846.15  337.9814915.68  314.1314988.75  321.6419406.97  322.04
19681.62  337.7720018.37  314.9521692.26  322.2521774.55  323.1622761.67     312
24279.19  332.1625179.28  316.2925435.15  342.0325515.71  326.6926976.66  353.15
#Mann= 9 ,-1 , 0
       0     .06       011686.88     .06       012055.11    .055       0
12311.37     .15       014988.75     .05       019406.97     .15       0
21692.26     .05       021774.55     .15       024279.19     .06       0
Levee=0,,,-1,14846.15,337.98,,
#XS Ineff= 2 , 0
       0                14846.14       0     350
Permanent Ineff=
       F       F
#Block Obstruct= 2 ,-1
 5539.12 8988.06     32019868.5521590.32  322.66
Bank Sta=12055.11,12311.37
XS Rating Curve= 0 ,0
Exp/Cntr=0.3,0.1

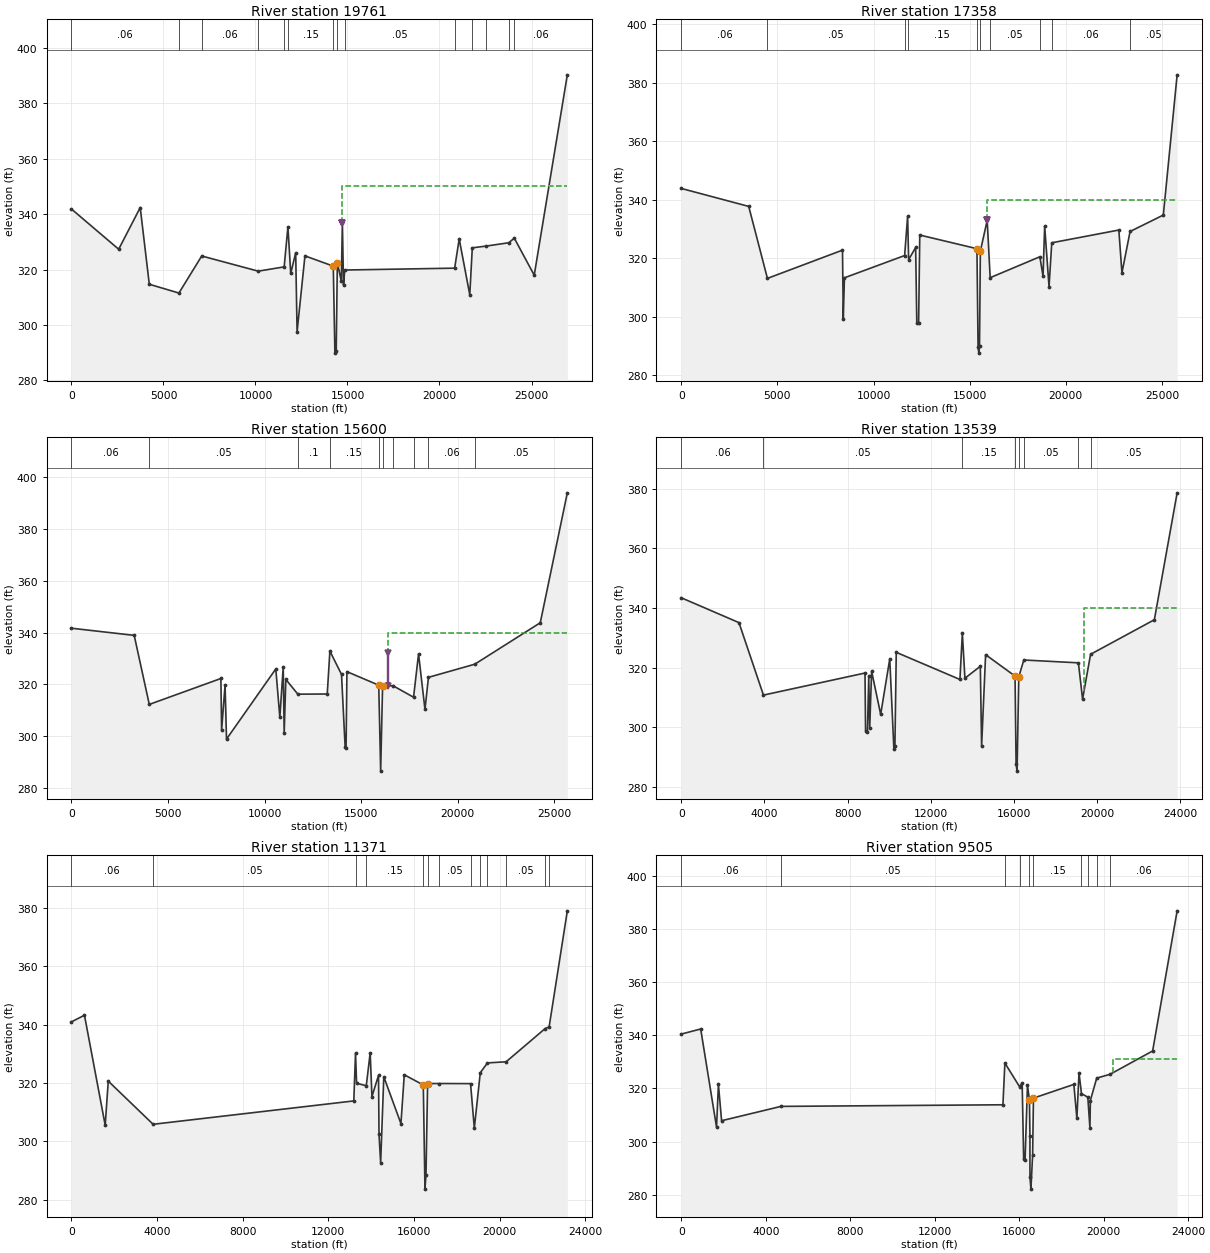
Type RM Length L Ch R = 1 ,19761   ,1667.72,2402.96,1502.54
BEGIN DESCRIPTION:
ROB - Ellis LID2
END DESCRIPTION:
XS GIS Cut Line= 4
  2617675.582382  6829873.695452 2604705.0561615 6829337.5528737
 2603411.4228539 6830022.0524582 2590950.9369418 6829007.6189793
#Sta/Elev= 30
       0  341.85 2566.34  327.35  3736.7  342.38 4229.96  314.71 5839.93  311.54
  7078.7  324.9110148.36  319.4411558.66  320.9811763.17  335.44 11915.8  318.63
12185.79  326.0612261.16  297.5812688.54  324.9514228.22  321.25 14316.2  289.86
14387.41  290.4714449.01  322.5614664.05  315.8714722.77  336.99 14784.7  314.39
14850.28  319.8520823.65  320.5221071.54  331.0621645.63  310.9221782.82  327.86
22513.25  328.4623758.59  329.6824066.84  331.3325148.06  317.98 26946.9  390.28
#Mann= 14 ,-1 , 0
       0     .06       0 5839.93     .05       0  7078.7     .06       0
10148.36     .05       011558.66      .1       011763.17     .15       0
14228.22    .055       014449.01     .15       014850.28     .05       0
20823.65     .15       021782.82     .06       022513.25     .15       0
23758.59     .05       024066.84     .06       0
Levee=0,,,-1,14722.77,336.99,,
#XS Ineff= 2 , 0
       0                14722.91       0     350
Permanent Ineff=
       F       F
Bank Sta=14228.22,14449.01
XS Rating Curve= 0 ,0
Exp/Cntr=0.3,0.1

Type RM Length L Ch R = 1 ,17358   ,1420.5,1758.18,1573.47
BEGIN DESCRIPTION:
ROB - Ellis LID2
END DESCRIPTION:
XS GIS Cut Line= 4
  2617325.027619   6828100.30077 2602483.9771289 6827689.9468975
 2601723.6513308 6828420.8407292 2591844.9203689 6827903.9698543
#Sta/Elev= 30
       0  343.84 3507.69   337.7 4481.58  313.09 8386.33  322.75 8426.59  299.28
 8486.79  313.2911618.63   320.911773.99  334.3111826.98  319.5112191.52  323.65
12251.93   297.812345.92  297.7512406.34  327.9115379.45  323.2415438.49  289.48
15479.56  287.5415513.17  289.8515557.89  322.4215913.33  332.9516067.94  313.33
18652.41  320.4818817.39  313.8418902.67  330.9619130.18   310.219271.54  325.26
22761.06  329.6222921.87  314.9723345.55  329.1225074.75  334.7425793.57  382.68
#Mann= 10 ,-1 , 0
       0     .06       0 4481.58     .05       011618.63      .1       0
11773.99     .15       015379.45    .055       015557.89     .15       0
16067.94     .05       018652.41     .15       019271.54     .06       0
23345.55     .05       0
Levee=0,,,-1,15913.33,332.95,,
#XS Ineff= 2 , 0
       0                15913.35       0     340
Permanent Ineff=
       F       F
Bank Sta=15379.45,15557.89
XS Rating Curve= 0 ,0
Exp/Cntr=0.3,0.1

Type RM Length L Ch R = 1 ,15600   ,1608.95,2060.49,2106.04
BEGIN DESCRIPTION:
ROB - Ellis LID2
END DESCRIPTION:
XS GIS Cut Line= 4
  2616953.851988 6826656.8399823 2601977.2145359 6826298.6985631
 2600689.1096641  6826862.618507 2591425.2169149 6826347.5269563
#Sta/Elev= 30
       0  341.69 3247.39  338.93 4027.84  312.29  7734.2  322.29 7771.73  302.44
 7951.05  319.79 8024.98   298.910576.64  325.9810785.35  307.3210961.44  326.86
11009.95   301.311095.96  321.9211718.38  316.2413238.98  316.3113375.88  332.87
13977.19  323.8714166.39  295.6914213.29  295.57 14257.6  324.9315904.39  319.71
 16003.8  286.5516103.74 319.47616648.49  319.4717706.17  315.07 17965.2  331.78
18296.69  310.3718477.35  322.7420873.65   327.824265.14   343.825665.24  393.93
#Mann= 10 ,-1 , 0
       0     .06       0 4027.84     .05       011718.38      .1       0
13375.88     .15       015904.39    .055       016103.74     .15       0
16648.49     .05       017706.17     .15       018477.35     .06       0
20873.65     .05       0
Levee=0,,,-1,16378.11,332.03,,
#XS Ineff= 2 , 0
       0                16378.11       0     340
Permanent Ineff=
       F       F
Bank Sta=15904.39,16103.74
XS Rating Curve= 0 ,0
Exp/Cntr=0.3,0.1

Type RM Length L Ch R = 1 ,13539   ,1853.81,2167.97,2021.98
BEGIN DESCRIPTION:
ROB IFA station 19377: flow expansion due to Ellis LID2 levee upstream
END DESCRIPTION:
XS GIS Cut Line= 4
  2616623.918094  6825234.000063 2601962.4806649 6824635.9948795
 2600358.5541085 6824776.2990626 2592791.3708253 6824383.1898411
#Sta/Elev= 30
       0  343.39 2775.84  335.06 3953.71  310.76 8841.22  318.16 8867.95  298.84
 8957.82  298.42 9020.78  317.01 9066.89  299.69 9158.91  318.78 9594.84   304.3
10031.85  322.8710230.43   292.8 10280.7  293.5710345.09   325.113408.84     316
13525.78  331.5113649.38  316.4214390.17  320.4114452.01  293.6114644.67  324.32
16060.18  317.1416110.86  287.5716157.83  285.2716241.02 316.86316481.97  322.53
 19109.8  321.58 19310.9  309.4119695.51  324.4422765.08  336.0323861.07  378.58
#Mann= 8 ,-1 , 0
       0     .06       0 3953.71     .05       013525.78     .15       0
16060.18    .055       016241.02     .15       016481.97     .05       0
 19109.8     .15       019695.51     .05       0
#XS Ineff= 2 , 0
       0                   19377       0     340
Permanent Ineff=
       F       F
Bank Sta=16060.18,16241.02
XS Rating Curve= 0 ,0
Exp/Cntr=0.3,0.1

Type RM Length L Ch R = 1 ,11371   ,1126.53,1866.67,1035.01
XS GIS Cut Line= 4
  2616678.549045 6823617.0750931 2600683.9868244 6822697.6332504
 2599525.4779132 6822724.6510036 2593543.1323784 6822471.2417597
#Sta/Elev= 30
       0  341.02  607.45  343.29 1576.29  305.58 1719.57   320.7 3815.42   305.9
13191.75  313.9113271.83  330.3413321.82  319.9713774.15319.1138 13956.7  330.37
14039.04   315.414346.56  322.6814369.23  302.4814446.18  292.7314592.49   322.2
15393.52  306.1415549.96  322.8716438.22  319.3816516.24  283.6716564.05  288.58
16639.64  319.8617168.75  319.8818645.72  319.84 18822.4  304.5919100.58  323.58
19435.75  326.9420308.26  327.3322124.54  338.6822317.14  339.2923167.53  379.08
#Mann= 13 ,-1 , 0
       0     .06       0 3815.42     .05       013271.83     .06       0
13774.15     .15       016438.22    .055       016639.64     .15       0
17168.75     .05       018645.72     .15       019100.58     .05       0
19435.75     .06       020308.26     .05       022124.54     .06       0
22317.14     .05       0
Bank Sta=16438.22,16639.64
XS Rating Curve= 0 ,0
Exp/Cntr=0.3,0.1

Type RM Length L Ch R = 1 ,9505    ,1134.79,1900.98,1032.38
XS GIS Cut Line= 4
  2617943.653671  6822780.116724 2602120.2802758  6821643.751677
 2600430.9125433 6821757.1829476 2594525.7712673 6821374.0195375
#Sta/Elev= 30
       0   340.5  919.31  342.41  1668.9  305.46 1758.73  321.51 1908.43  307.85
 4718.92  313.25 15227.5  313.8615319.42  329.5916014.85  320.6716138.72  322.04
16208.93  293.4216274.19  293.01 16389.1  321.1916483.71  315.5916505.97  302.11
16507.06   286.616552.25  282.0816633.09  294.9316672.79  316.3718584.62  321.53
18728.66  308.7218828.48  325.8918946.26  318.0919245.89  316.7119346.87  305.02
19365.78  315.4519666.52   323.920300.58  325.3522314.28  334.1323474.79  386.93
#Mann= 10 ,-1 , 0
       0     .06       0 4718.92     .05       015319.42     .06       0
16014.85     .15       016483.71    .055       016672.79     .15       0
18946.26     .05       019245.89     .15       019666.52     .05       0
20300.58     .06       0
#XS Ineff= 2 , 0
       0                20419.34       0     331
Permanent Ineff=
       F       F
Bank Sta=16483.71,16672.79
XS Rating Curve= 0 ,0
Exp/Cntr=0.3,0.1

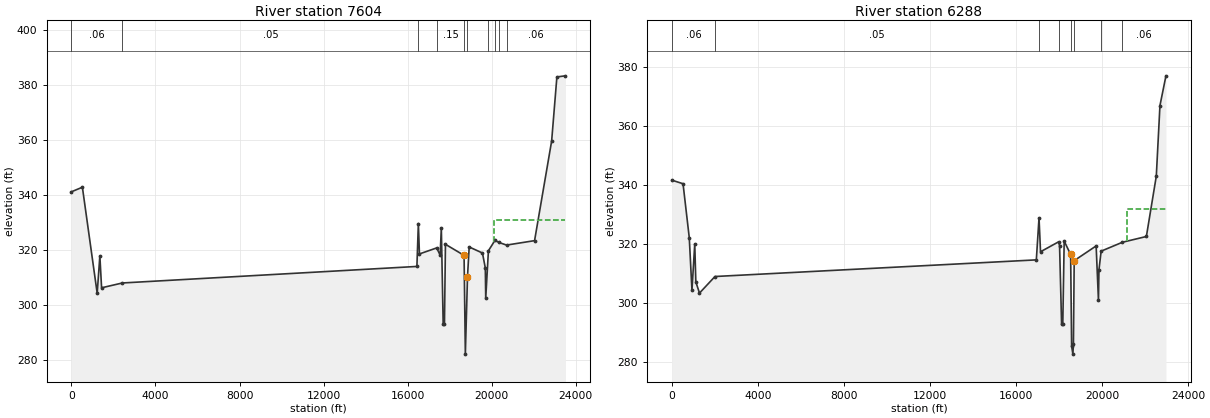
Type RM Length L Ch R = 1 ,7604    ,1109.26,1315.69,1024.77
XS GIS Cut Line= 4
  2618706.625802  6821790.315041 2600688.1924188 6820426.8980209
  2599694.164641 6820689.1896876 2595306.2479743 6820253.2869098
#Sta/Elev= 30
       0  341.11  524.17  342.78 1228.28   304.3 1355.65  317.87 1437.33  306.28
 2425.82  308.0316439.61  314.0316509.06  329.6116559.86  318.5717380.66  320.75
17546.34  318.1217601.51  327.9817689.72  293.1217750.21  292.9817797.94  322.06
18683.77  318.0518744.51  282.2118846.83  310.2818926.93   321.119558.28   318.9
19694.32  313.4819714.03  302.4719842.43  319.7220153.77  323.4920349.21  322.72
20704.53  321.7822037.77  323.3922850.49  359.5523099.93   382.823507.45   383.2
#Mann= 10 ,-1 , 0
       0     .06       0 2425.82     .05       016509.06     .06       0
17380.66     .15       018683.77    .055       018846.83     .15       0
19842.43     .05       020153.77     .15       020349.21     .05       0
20704.53     .06       0
#XS Ineff= 2 , 0
       0                20091.76       0     331
Permanent Ineff=
       F       F
Bank Sta=18683.77,18846.83
XS Rating Curve= 0 ,0
Exp/Cntr=0.3,0.1

Type RM Length L Ch R = 1 ,6288    ,4777.52,6287.97,5432.52
XS GIS Cut Line= 6
2619293.73848072 6820341.02639792618516.223959626819988.94081597
2602318.95386082 6819749.15356592600866.164771656819685.79903381
2600323.704570476819714.953503062596424.624770226819393.00007872
#Sta/Elev= 30
       0  341.78   519.1  340.57   808.6  322.28  933.51  304.43 1063.51  320.15
  1113.5  307.29 1283.49  303.49 2003.45  309.1116938.12  314.7517063.12  328.99
17133.08   317.517972.71  320.8718017.69   319.618112.65  292.8618167.63  292.91
 18232.6  321.1118532.45  316.58 18578.5   285.518636.94  282.7918662.12  286.18
18698.05  314.4919717.65  319.4819825.78  300.99   19849  311.3819950.19  317.71
20936.78  320.7222052.49  322.6822513.65  343.1422683.49  367.0922962.33  377.16
#Mann= 8 ,-1 , 0
       0     .06       0 2003.45     .05       017063.12     .06       0
17972.71     .15       018532.45    .055       018698.05     .15       0
19950.19     .05       020936.78     .06       0
#XS Ineff= 2 , 0
       0                   21133       0     332
Permanent Ineff=
       F       F
Bank Sta=18532.45,18698.05
XS Rating Curve= 0 ,0
Exp/Cntr=0.3,0.1
Stream Node=Trinity River   ,                , 0 , 0 ,Upstream end
Stream Node=Trinity River   ,                , 0 , 1 ,Downstream end
LCMann Table=0

--- TR_FEMA.g04 (geometry) ---

Geom Title=Trinity_NV_EllisLID2
Program Version=5.06
BEGIN GEOM DESCRIPTION:
Scenario B
END GEOM DESCRIPTION:

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
River Reach=Trinity River   ,1

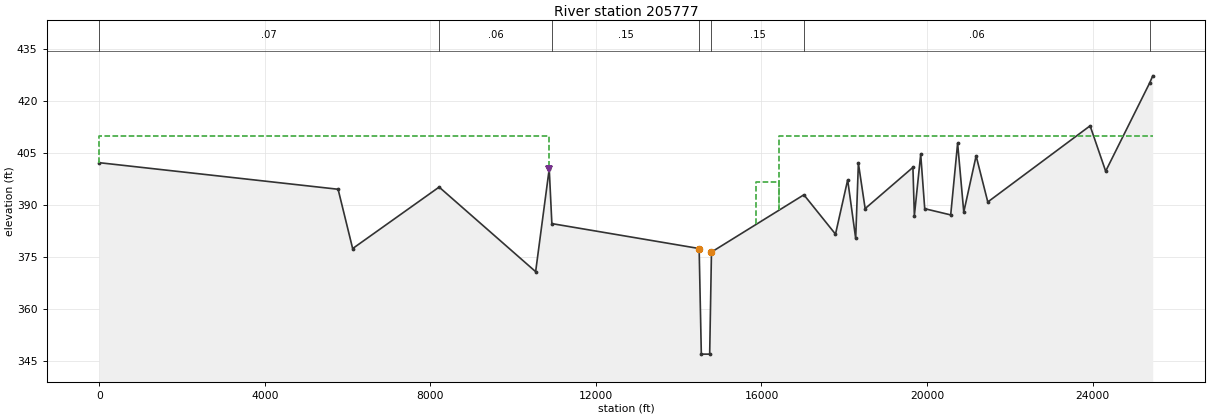
Type RM Length L Ch R = 1 ,205777  ,1262.75,1248.24,1229.51
BEGIN DESCRIPTION:
LOB - Southside WWTP
ROB IFA station 16416: flow contraction due to Dallas LID1/2 levee downstream
END DESCRIPTION:
XS GIS Cut Line= 6
2540980.83019298 6933539.73664742535497.477602626924208.30611411
2533614.000070366920921.000024692533600.635923866920903.28221235
 2529903.70565376914444.53364694 2528203.05241526911525.84775851
#Sta/Elev= 30
       0  402.32 5769.27  394.66 6121.02  377.55 8210.64  395.2910542.62  370.89
10870.96  400.54 10934.7  384.7514493.46  377.5614546.29   347.114748.07   347.1
14791.42  376.5417024.34  393.0617788.14  381.7118082.62  397.3718276.12  380.47
18341.35  402.1718504.74  389.0819659.18  400.9719693.92  387.0319847.13  404.74
19944.42  389.0520572.06  387.2620739.04  407.9220887.76  388.0721186.02  404.29
21468.32  390.9923940.48  412.9624316.52  399.8725381.49  425.37 25454.1  427.38
#Mann= 7 ,-1 , 0
       0     .07       0 8210.64     .06       0 10934.7     .15       0
14493.46    .055       014791.42     .15       017024.34     .06       0
25381.49     .08       0
Levee=-1,10870.96,400.54,0,,,,
#XS Ineff= 3 ,-1
       010870.96     41015871.74   16416  396.63   16416 25454.1     410
Permanent Ineff=
       F       F       F
Bank Sta=14493.46,14791.42
XS Rating Curve= 0 ,0
Exp/Cntr=0.3,0.1