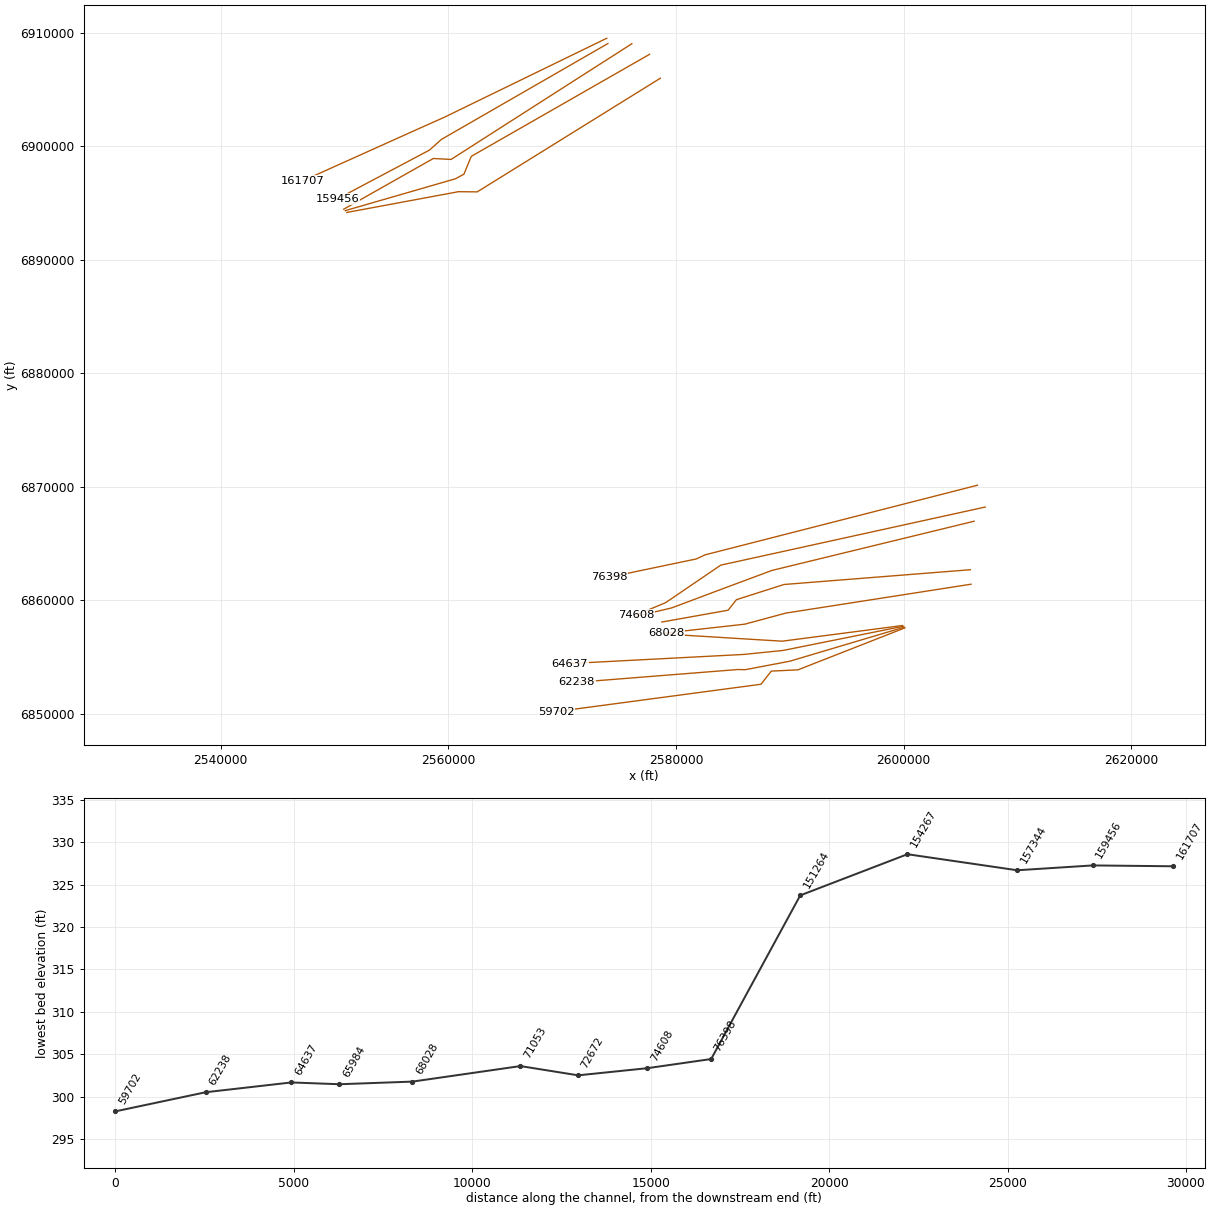
HEC-RAS study TR_FEMA.prj: Trinity_River_FEMA

--- TR_FEMA.g04 (geometry) --- (continued)

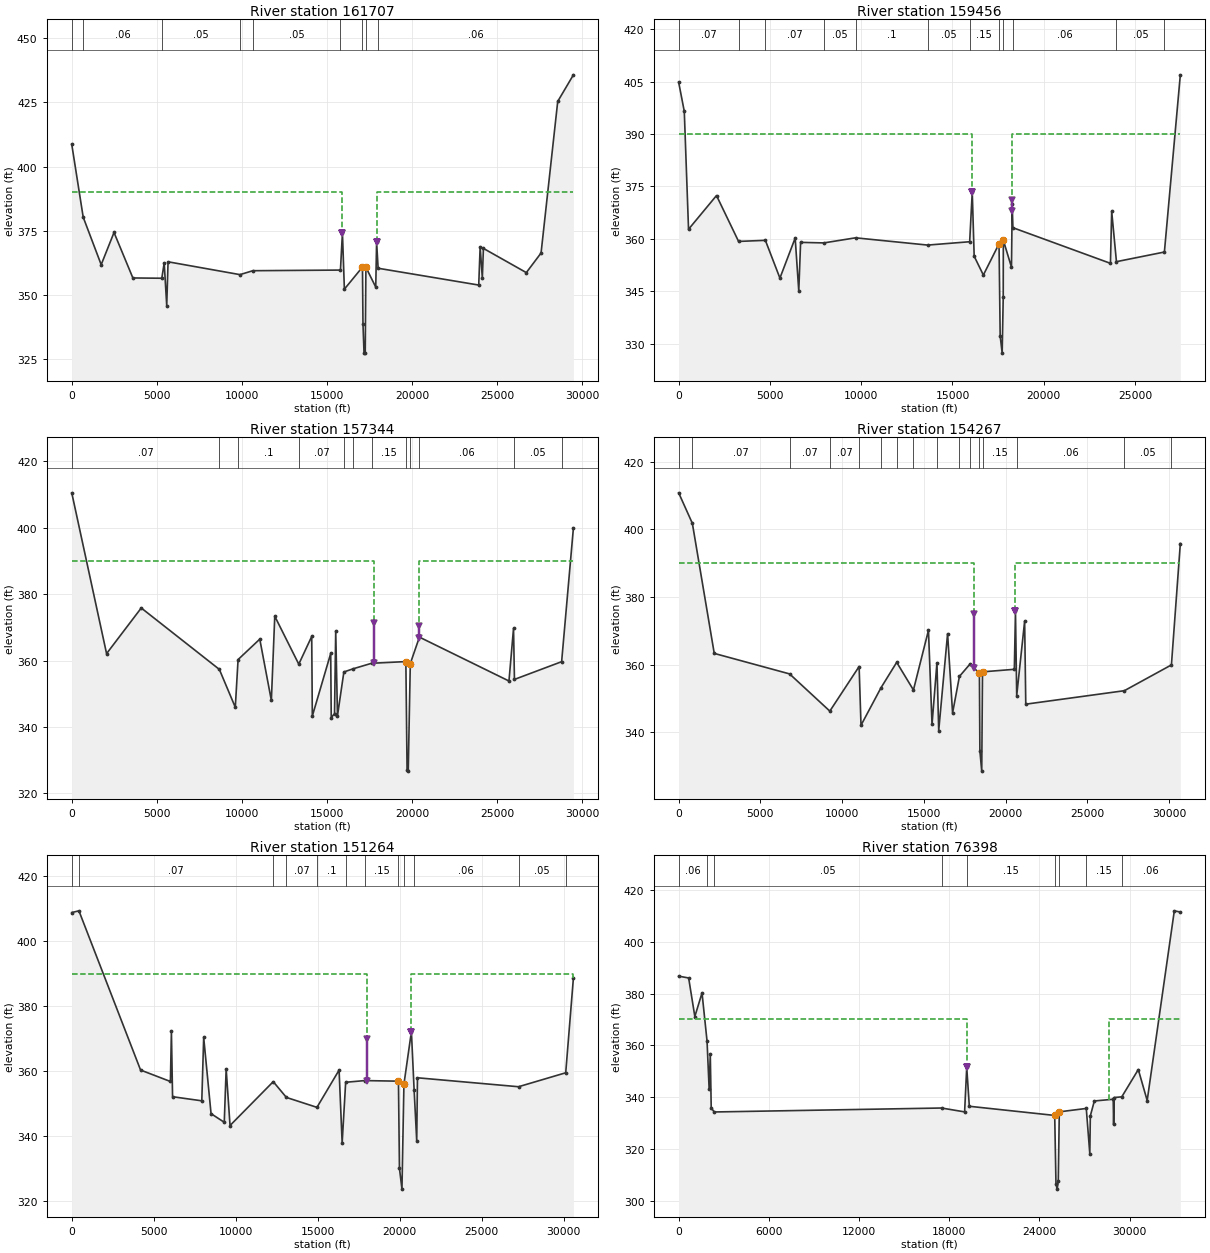
Type RM Length L Ch R = 1 ,161707  ,1287.44,2251.17,2226.65
BEGIN DESCRIPTION:
LOB - Bois D'Arc, ROB - Dallas LID1/2
END DESCRIPTION:
XS GIS Cut Line= 4
 2573919.27944876909528.308935682559622.057226476902553.30893567
2557775.182226466901729.35060234 2547235.25167096896976.22560234
#Sta/Elev= 30
       0  408.66  673.33  380.22 1730.72  361.68 2484.87  374.25 3593.53   356.5
  5294.1  356.39 5435.28  362.36 5583.78  345.73 5662.01  362.81 9889.96   357.8
10646.13  359.3315796.61  359.5815913.21  374.1116027.77  352.1317091.24  360.75
17121.09  338.5217183.35  327.1617253.35  327.1617293.04  360.6817871.87  352.93
17921.79  370.6318010.71  360.2923925.79  353.7324009.32  368.6724137.73  356.47
24200.98  368.0426724.05  358.5927590.31  366.2428570.23  425.41 29492.4  435.79
#Mann= 9 ,-1 , 0
       0     .07       0  673.33     .06       0  5294.1     .05       0
 9889.96      .1       010646.13     .05       015796.61     .15       0
17091.24    .055       017293.04     .15       018010.71     .06       0
Levee=-1,15913.21,374.11,-1,17921.79,370.63,,
#XS Ineff= 2 ,-1
       015913.21     39017921.79 29492.4     390
Permanent Ineff=
       F       F
Bank Sta=17091.24,17293.04
XS Rating Curve= 0 ,0
Exp/Cntr=0.3,0.1

Type RM Length L Ch R = 1 ,159456  ,1796.97,2111.7,856.13
BEGIN DESCRIPTION:
LOB - Bois D'Arc, ROB - Dallas LID1/2
END DESCRIPTION:
XS GIS Cut Line= 4
2574022.578059816909063.899213462559391.791022766900614.24643568
2558348.966948696899676.746435672550237.855837576895365.98254678
#Sta/Elev= 30
       0  404.85   307.8  396.52  540.76  362.74 2072.69   372.4  3282.1  359.26
 4750.08  359.57  5546.9  348.75 6383.02  360.23 6580.04  345.05  6680.2  358.99
  7953.6  358.83 9688.69  360.2913642.18  358.2115942.82  359.1716083.73  373.43
16189.08  355.0216691.93  349.6317550.99  358.5817613.52  332.1917722.64  327.26
17780.74  343.2917786.32  359.6118232.31  351.8818272.77  369.9518310.25  363.19
23654.16  352.9823722.66  367.87 23983.2  353.4626610.13  356.2227483.23  406.98
#Mann= 12 ,-1 , 0
       0     .07       0  3282.1     .06       0 4750.08     .07       0
  7953.6     .05       0 9688.69      .1       013642.18     .05       0
15942.82     .15       017550.99    .055       017786.32     .15       0
18310.25     .06       0 23983.2     .05       026610.13     .06       0
Levee=-1,16083.73,373.43,-1,18283.99,371.07,,
#XS Ineff= 2 ,-1
       016083.73     39018283.9927483.23     390
Permanent Ineff=
       F       F
Bank Sta=17550.99,17786.32
XS Rating Curve= 0 ,0
Exp/Cntr=0.3,0.1

Type RM Length L Ch R = 1 ,157344  ,948.05,3077.14,2486.59
BEGIN DESCRIPTION:
LOB - Bois D'Arc, ROB - Dallas LID1/2
END DESCRIPTION:
XS GIS Cut Line= 4
2576124.256300566909043.413102352560240.402133886898849.66310234
2558682.068800546898932.996435672550808.120060356894467.16161053
#Sta/Elev= 30
       0  410.53 2046.93  362.09 4085.18  375.84 8675.15  357.34 9612.65  345.92
 9776.27   360.311051.82  366.4511732.16  347.9811932.42  373.3613343.42  358.91
14104.43  367.2614140.35  343.2815220.16  362.1415252.47  342.7815444.82  344.04
   15515   368.915619.05  343.3915994.19  356.5616544.95  357.5317624.69  359.18
19638.15  359.6919708.99  327.0119777.38  326.6919898.87  359.0920434.58  367.06
 25698.6  353.8425966.05  369.68 26020.1  354.3228793.51  359.66 29486.2  399.98
#Mann= 12 ,-1 , 0
       0     .07       0 8675.15     .07       0 9776.27      .1       0
13343.42     .07       015994.19     .05       016544.95     .07       0
17624.69     .15       019638.15    .055       019898.87     .15       0
20434.58     .06       0 26020.1     .05       028793.51     .06       0
Levee=-1,17774.12,371.28,-1,20414.93,370.51,,
#XS Ineff= 2 ,-1
       017774.15     39020414.93 29486.2     390
Permanent Ineff=
       F       F
Bank Sta=19638.15,19898.87
XS Rating Curve= 0 ,0
Exp/Cntr=0.3,0.1

Type RM Length L Ch R = 1 ,154267  ,2928.63,3003.32,1020.6
BEGIN DESCRIPTION:
LOB - Bois D'Arc, ROB - Dallas LID1/2
END DESCRIPTION:
XS GIS Cut Line= 5
2577683.119930486908112.994882482562017.311695226899122.99645831
2561369.395340146897553.204650392560632.806918296897148.53059098
2550948.498531046894340.13036789
#Sta/Elev= 30
       0   410.8  837.14  401.79 2176.36  363.36 6785.31   357.3 9245.48  346.31
11036.79  359.4911152.87  342.1312375.82  353.2213335.26  360.7214359.38  352.55
15278.67  370.1915496.36  342.3815796.75  360.5815905.35  340.5616448.28  369.19
 16753.2  345.7617172.32  356.5717799.81   360.118394.04  357.59 18423.7  334.59
18536.48  328.5818584.13  357.9120530.15  358.6620600.43  375.7620675.41  350.89
21160.32  372.8521230.31  348.3627259.18  352.3430138.64  359.9630683.54  395.82
#Mann= 16 ,-1 , 0
       0     .07       0  837.14     .07       0 6785.31     .07       0
 9245.48     .07       011036.79      .1       012375.82     .07       0
13335.26      .1       014359.38     .07       015796.75      .1       0
17172.32     .07       017799.81     .15       018394.04    .055       0
18584.13     .15       020675.41     .06       027259.18     .05       0
30138.64     .06       0
Levee=-1,18057.04,375.03,-1,20600.43,375.76,,
#XS Ineff= 2 ,-1
       018057.04     39020600.4330683.54     390
Permanent Ineff=
       F       F
Bank Sta=18394.04,18584.13
XS Rating Curve= 0 ,0
Exp/Cntr=0.3,0.1

Type RM Length L Ch R = 1 ,151264  ,621.55,2495.98,3306.68
BEGIN DESCRIPTION:
LOB - Bois D'Arc, ROB - Dallas LID1/2
END DESCRIPTION:
XS GIS Cut Line= 5
 2578634.50910386906008.828159062562540.853627156895992.51026523
2560824.186784896896009.176898552560782.641592386895987.49255873
2551073.515013316894178.02144015
#Sta/Elev= 30
       0  408.76  437.28  409.29 4197.57  360.34 6017.73  356.82 6077.77   372.2
 6148.51  352.14 7931.23  350.88 8046.75  370.36 8495.57  346.93  9301.6  344.28
 9417.25  360.68 9653.25  343.2912288.91  356.7713090.76  351.9214954.12  348.87
16304.17  360.3216491.45  337.9316705.35  356.5817869.34   357.119925.13  356.92
19985.24  330.1520138.63  323.7320258.42  355.9620714.75  372.1520879.38  354.32
21039.31  338.5921084.29  357.9627246.89  355.2130125.76   359.530595.58  388.68
#Mann= 12 ,-1 , 0
       0     .07       0  437.28     .07       012288.91      .1       0
13090.76     .07       014954.12      .1       016705.35     .07       0
17869.34     .15       019925.13    .055       020258.42     .15       0
20879.38     .06       027246.89     .05       030125.76     .06       0
Levee=-1,17986.26,369.76,-1,20714.75,372.15,,
#XS Ineff= 2 ,-1
       017986.26     39020714.7530595.58     390
Permanent Ineff=
       F       F
Bank Sta=19925.13,20258.42
XS Rating Curve= 0 ,0
Exp/Cntr=0.3,0.1

Type RM Length L Ch R = 1 ,76398   ,1366.66,1790.14,1812.24
BEGIN DESCRIPTION:
LOB - Kaufman MUD1
ROB IFA station 28654: flow contraction due to Ellis LID2 levee downstream
END DESCRIPTION:
XS GIS Cut Line= 4
2606496.303529836870144.903692242582555.794270566864008.95461815
2581795.377603896863650.621284822574149.081307596862047.68147001
#Sta/Elev= 30
       0  386.75  664.16  386.05 1075.59  371.15 1553.77  380.26 1887.39  361.67
 2028.38     343 2102.55  356.67 2165.46  335.77 2369.57  334.26 17484.7  335.79
19019.32  334.2919159.68  351.5219332.29  336.4625011.92  332.9225095.98  306.48
25173.32  304.4425249.32   307.725316.97  334.3127111.45  335.6227346.03  318.15
27381.17  332.7527648.06  338.5128902.27  339.1828930.64  329.4228969.84  339.84
29472.69  340.1130572.04  350.6631162.57  338.6932967.12     41233367.44  411.53
#Mann= 9 ,-1 , 0
       0     .06       0 1887.39      .1       0 2369.57     .05       0
 17484.7     .15       019159.68     .15       025011.92    .055       0
25316.97     .06       027111.45     .15       029472.69     .06       0
Levee=-1,19159.68,351.52,0,,,,
#XS Ineff= 2 , 0
       019160.35     370   28654       0     370
Permanent Ineff=
       F       F
Bank Sta=25011.92,25316.97
XS Rating Curve= 0 ,0
Exp/Cntr=0.3,0.1

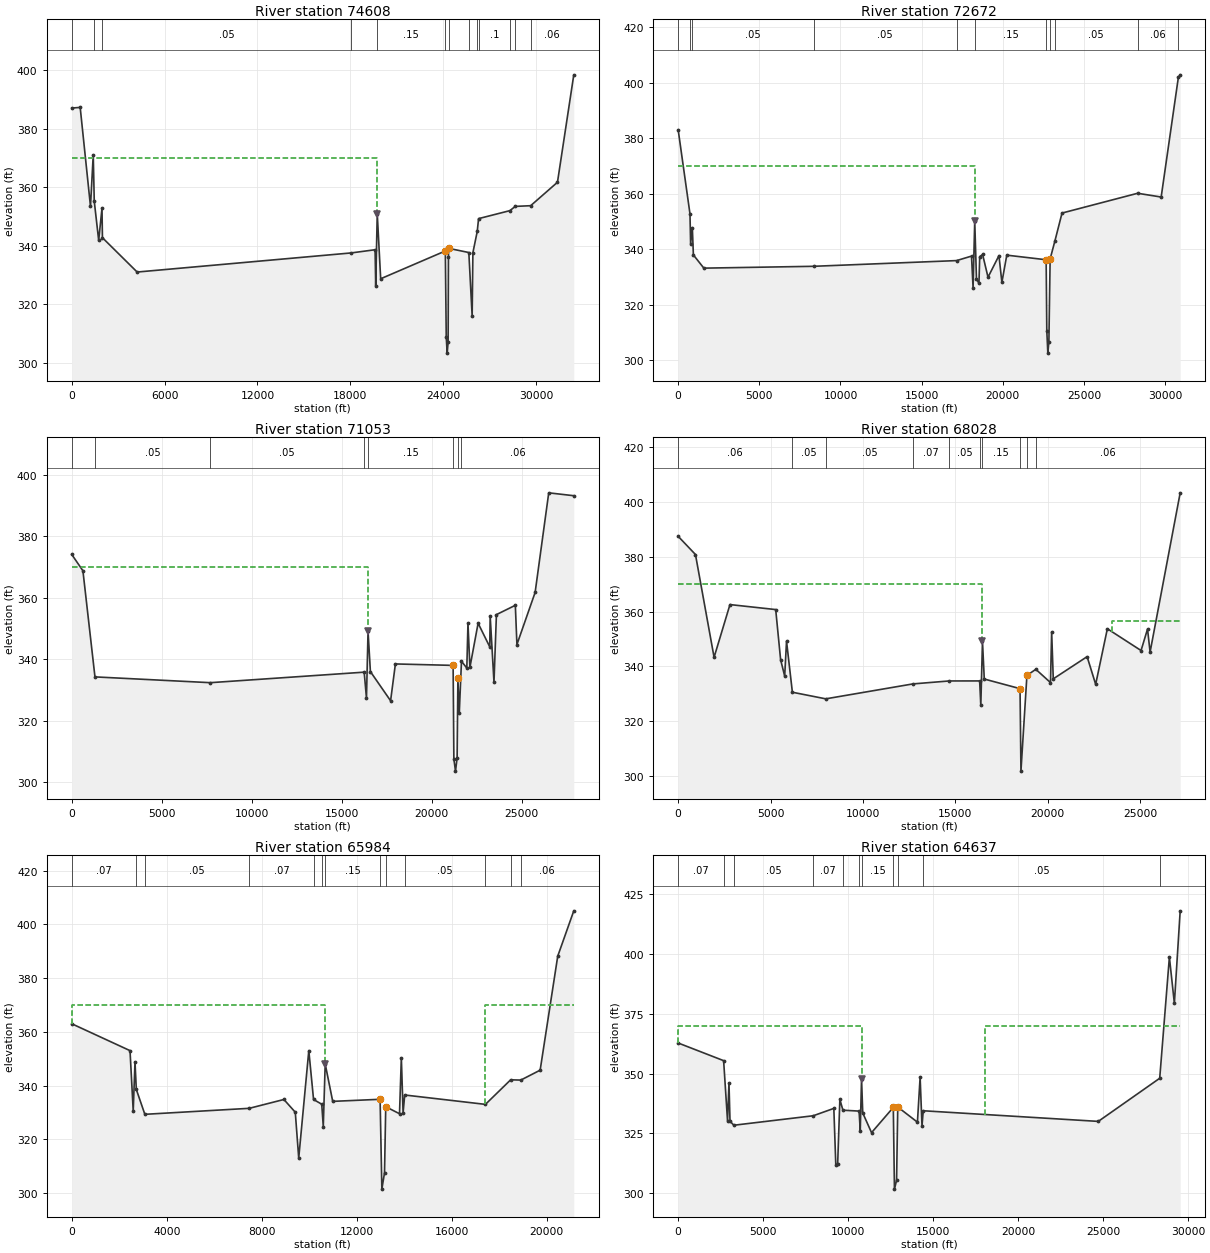
Type RM Length L Ch R = 1 ,74608   ,1431.86,1935.4,1883.95
BEGIN DESCRIPTION:
LOB - Kaufman MUD1
ROB IFA station 27520: flow contraction due to Ellis LID2 levee downstream
END DESCRIPTION:
XS GIS Cut Line= 4
2607172.70399279 6868220.89906262583937.460937236863102.84350704
2579097.669270566859799.892118152576528.224826116858723.50322926
#Sta/Elev= 30
       0  386.99  544.02  387.21 1209.35  353.46 1387.84  371.06  1453.2   355.2
 1739.91  341.83 1952.79   352.8 1981.77  342.74 4224.41  331.0318049.59  337.55
19598.54  338.6419639.09  326.3419738.14  350.9919959.74  328.7424137.05  338.22
24196.64  308.8824256.73  303.3624317.16  307.0724337.97  336.15 24351.3  339.12
25656.08  337.6925870.55  315.9925918.44  337.6326199.21  344.8826285.54  349.26
28312.69  351.9928652.85  353.4329650.73  353.6731383.55  361.6732437.45  398.33
#Mann= 13 ,-1 , 0
       0     .06       0  1453.2      .1       0 1981.77     .05       0
18049.59     .15       019738.14     .15       024137.05    .055       0
 24351.3     .06       025656.08     .15       026199.21     .06       0
26285.54      .1       028312.69     .06       028652.85     .05       0
29650.73     .06       0
Levee=-1,19738.14,350.99,0,,,,
#XS Ineff= 2 , 0
       019738.01     370               0
Permanent Ineff=
       F       F
Bank Sta=24137.05,24351.3
XS Rating Curve= 0 ,0
Exp/Cntr=0.3,0.1

Type RM Length L Ch R = 1 ,72672   ,1501.06,1619.39,1672.71
BEGIN DESCRIPTION:
LOB - Kaufman MUD1
END DESCRIPTION:
XS GIS Cut Line= 5
2606198.363715026866971.767118162588441.419270566862638.43378482
2583873.020374556860934.26640181  2579635.8637156859339.82267371
2576476.141492786858575.93378482
#Sta/Elev= 30
       0  383.01   727.2  352.74  766.89  341.94  871.99  347.76  937.51  337.91
 1582.58  333.15 8340.55  333.8117154.88  335.8718074.57  337.4918170.86  326.06
18272.61  350.1918379.52  329.3318533.11  327.6518579.39  337.2818758.24  338.07
19091.29  329.8819765.68  337.6719945.51  328.0220247.72  337.8322673.05  336.17
22712.98  310.65 22777.3  302.5222842.09  306.6622918.57  336.4623219.55   343.1
23651.49     353 28308.2  360.1329760.24  358.7830818.87  401.8830931.89  402.82
#Mann= 11 ,-1 , 0
       0     .06       0   727.2      .1       0  871.99     .05       0
 8340.55     .05       017154.88     .15       018272.61     .15       0
22673.05    .055       022918.57     .15       023219.55     .05       0
 28308.2     .06       030818.87     .06       0
Levee=-1,18272.61,350.19,0,,,,
#XS Ineff= 2 , 0
       018272.99     370               0
Permanent Ineff=
       F       F
Bank Sta=22673.05,22918.57
XS Rating Curve= 0 ,0
Exp/Cntr=0.3,0.1

Type RM Length L Ch R = 1 ,71053   ,2459.34,3024.49,2512.9
BEGIN DESCRIPTION:
LOB - Kaufman MUD1
END DESCRIPTION:
XS GIS Cut Line= 5
2605863.33767335 6862699.80531262589491.809895566861397.72197927
2585316.462673346860060.916423712584586.601562236859133.13864593
2578762.64322889 6858090.4303126
#Sta/Elev= 30
       0  374.05  619.76  368.76 1289.43  334.25 7702.91  332.3716253.83  335.79
16381.42  327.3416468.21  349.1416598.92  335.9817721.62  326.4917989.07  338.46
21197.53  337.9921239.12  307.5521329.45  303.6121420.01  307.87 21462.5  333.79
21539.34  322.4721661.53  339.3521958.48  337.1222022.37  351.7122131.22  337.35
22586.16   351.723233.27  344.0223256.45  354.0823468.82   332.5 23604.2   354.5
24655.53  357.5324743.94  344.7825755.54  361.7126512.19   394.127904.46  393.16
#Mann= 8 ,-1 , 0
       0     .06       0 1289.43     .05       0 7702.91     .05       0
16253.83     .15       016468.21     .15       021197.53    .055       0
 21462.5     .15       021661.53     .06       0
Levee=-1,16468.21,349.14,0,,,,
#XS Ineff= 2 , 0
       016467.63     370               0
Permanent Ineff=
       F       F
Bank Sta=21197.53,21462.5
XS Rating Curve= 0 ,0
Exp/Cntr=0.3,0.1

Type RM Length L Ch R = 1 ,68028   ,2550.09,2044.38,1660.23
BEGIN DESCRIPTION:
LOB - Kaufman MUD1
END DESCRIPTION:
XS GIS Cut Line= 4
2605931.785011316861423.225451462589668.590566876858881.67452554
2586047.062789096857900.771747762579138.035011316857129.47545146
#Sta/Elev= 30
       0   387.5  935.94  380.86 1943.46  343.33 2802.54  362.58 5277.51  360.76
 5543.05  342.47  5763.6  336.46 5863.55  349.23 6180.16  330.58 7986.68  328.17
12702.35  333.6214668.17   334.716313.76  334.7116376.19  325.7416466.15  349.24
16563.36   335.418498.82  331.8918547.94  301.7818871.39  336.7219352.53  338.95
20145.87  334.1120209.69   352.620296.95  335.4722128.28  343.5722591.26  333.46
23223.39  353.76 25046.8  345.81 25397.3  353.6525536.06  345.2527164.56  403.38
#Mann= 10 ,-1 , 0
       0     .06       0 6180.16     .05       0 7986.68     .05       0
12702.35     .07       014668.17     .05       016313.76     .15       0
16466.15     .15       018498.82    .055       018871.39     .15       0
19352.53     .06       0
Levee=-1,16466.15,349.24,0,,,,
#XS Ineff= 2 ,-1
       016467.39     370   2349427164.56   356.5
Permanent Ineff=
       F       F
Bank Sta=18498.82,18871.39
XS Rating Curve= 0 ,0
Exp/Cntr=0.3,0.1

Type RM Length L Ch R = 1 ,65984   ,761.4,1346.66,1829.69
BEGIN DESCRIPTION:
LOB - Kaufman MUD1
END DESCRIPTION:
XS GIS Cut Line= 4
2599899.674578646857782.477761572589338.451606636856402.66982564
2586149.562643236856597.114318642578859.972563656857045.02648056
#Sta/Elev= 30
       0  363.01 2454.07  353.01 2589.02  330.55 2663.99  348.86 2718.96  338.58
 3078.82  329.31 7477.09  331.54 8936.51  334.83 9416.33  330.09 9561.27  313.02
  9986.1  353.0310186.02  334.8310530.89  333.0710595.86  324.7510676.33  348.07
10993.27  334.1312989.66   334.913063.81  301.4713175.51  307.5413227.37  332.13
13807.24  329.5313884.37  350.3313958.72  329.8914025.36   336.517427.05  333.01
18489.29  342.1518916.26  342.0519732.17  345.7420473.26  388.1821149.13  405.04
#Mann= 13 ,-1 , 0
       0     .07       0 2718.96     .06       0 3078.82     .05       0
 7477.09     .07       010186.02     .05       010530.89     .15       0
10676.33     .15       012989.66    .055       013227.37     .06       0
14025.36     .05       017427.05     .06       018489.29     .05       0
18916.26     .06       0
Levee=-1,10676.33,348.07,0,,,,
#XS Ineff= 2 ,-1
       010675.66     370   1742721149.13     370
Permanent Ineff=
       F       F
Bank Sta=12989.66,13227.37
XS Rating Curve= 0 ,0
Exp/Cntr=0.3,0.1

Type RM Length L Ch R = 1 ,64637   ,1009.07,2399.06,1604.33
BEGIN DESCRIPTION:
LOB - Kaufman MUD1
END DESCRIPTION:
XS GIS Cut Line= 4
2599965.936913316857716.215426892589427.340536486855588.78103347
2585969.007230046855236.003195732570686.948883476854434.65768556
#Sta/Elev= 30
       0  362.84 2674.05  355.45 2903.96  330.26 2988.93  346.18 3048.91  330.12
 3273.83  328.42 7947.17  332.39 9156.71  335.47 9271.66  311.98 9381.62  312.13
 9511.57  339.22  9691.5  334.7110641.13  334.34 10711.1  326.1910786.73  347.98
10856.94  333.5711375.03  325.32 12655.1  335.8812722.57  301.6812847.47  305.35
12917.21  336.05   14074  329.7114232.38  348.5214343.15  328.1414416.02  334.48
24712.42  330.0328326.19  348.0828895.17  398.7729188.35  379.4529530.52  418.16
#Mann= 11 ,-1 , 0
       0     .07       0 2674.05     .06       0 3273.83     .05       0
 7947.17     .07       0  9691.5     .05       010641.13     .15       0
10786.73     .15       0 12655.1    .055       012917.21     .06       0
14416.02     .05       028326.19     .06       0
Levee=-1,10786.76,347.98,0,,,,
#XS Ineff= 2 ,-1
       010787.51     370   1806429530.52     370
Permanent Ineff=
       F       F
Bank Sta=12655.1,12917.21
XS Rating Curve= 0 ,0
Exp/Cntr=0.3,0.1

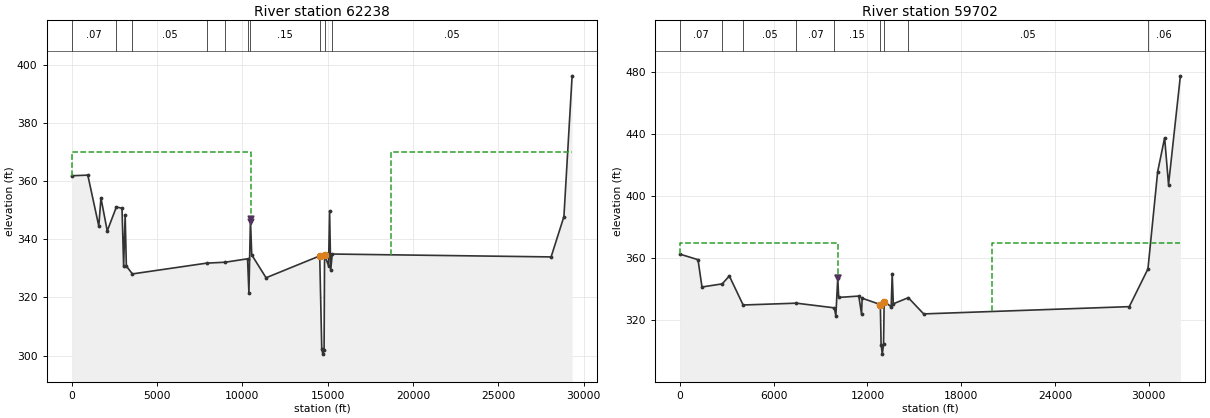
Type RM Length L Ch R = 1 ,62238   ,934.88,2536.56,1721.21
BEGIN DESCRIPTION:
LOB - Kaufman MUD1
END DESCRIPTION:
XS GIS Cut Line= 5
 2600070.0630174 6857640.48723192589996.437823476854635.30885907
2586090.592944896853892.311001232585441.287484976853906.20008107
2571292.502462396852779.63737357
#Sta/Elev= 30
       0   361.8  944.76  362.01  1589.6   344.5 1714.56  354.18 2084.47  342.84
 2619.34  351.08 2949.25  350.62 3044.23  330.72 3134.21  348.27 3204.19  330.77
  3559.1  328.08 7917.97  331.79 8987.74  332.0910307.48  333.2710387.47  321.62
10477.67  346.8610552.87  334.6311392.43  326.76   14538  334.2714657.47  302.21
14722.48  300.5314793.15  301.8814821.85  334.5615054.51  330.8615115.79  349.72
15180.49  329.3515272.27  334.9128099.84  333.9228850.59  347.7729331.23  396.12
#Mann= 10 ,-1 , 0
       0     .07       0 2619.34     .06       0  3559.1     .05       0
 7917.97     .07       0 8987.74     .05       010307.48     .15       0
10477.67     .15       0   14538    .055       014821.85     .06       0
15272.27     .05       0
Levee=-1,10482.67,346.86,0,,,,
#XS Ineff= 2 ,-1
       0 10483.4     370   1873729331.23     370
Permanent Ineff=
       F       F
Bank Sta=14538,14821.85
XS Rating Curve= 0 ,0
Exp/Cntr=0.3,0.1

Type RM Length L Ch R = 1 ,59702   ,1056.97,2878.56,838.01
BEGIN DESCRIPTION:
LOB - Kaufman MUD1
END DESCRIPTION:
XS GIS Cut Line= 5
 2600117.39330336857574.224897222590721.588932226853876.65125564
2588378.092963076853766.616698822587474.751265796852609.13804264
2569517.328847386850204.46371815
#Sta/Elev= 30
       0  362.63 1154.68  359.07 1409.61  341.48 2704.25   343.5 3159.13  348.59
 4043.89   329.9 7452.94  331.07 9882.27  328.06 9977.25  322.8510099.32  347.32
10159.24  334.7711445.83  335.6411621.68  324.0511661.96  334.2612824.23   330.2
12873.03  304.45 12951.6  298.2713031.31  304.8513070.14  332.0213518.94  328.85
13585.21  350.0913652.52  330.6514614.64   334.6   15599  324.1628757.88  328.84
29952.04   353.130574.18  415.67 31020.4  437.5131270.17  407.4132029.23  477.42
#Mann= 9 ,-1 , 0
       0     .07       0 2704.25     .06       0 4043.89     .05       0
 7452.94     .07       0 9882.27     .15       012824.23    .055       0
13070.14     .15       014614.64     .05       029952.04     .06       0
Levee=-1,10099.32,347.32,0,,,,
#XS Ineff= 2 ,-1
       010100.35     370   1996732029.23     370
Permanent Ineff=
       F       F
Bank Sta=12824.23,13070.14
XS Rating Curve= 0 ,0
Exp/Cntr=0.3,0.1