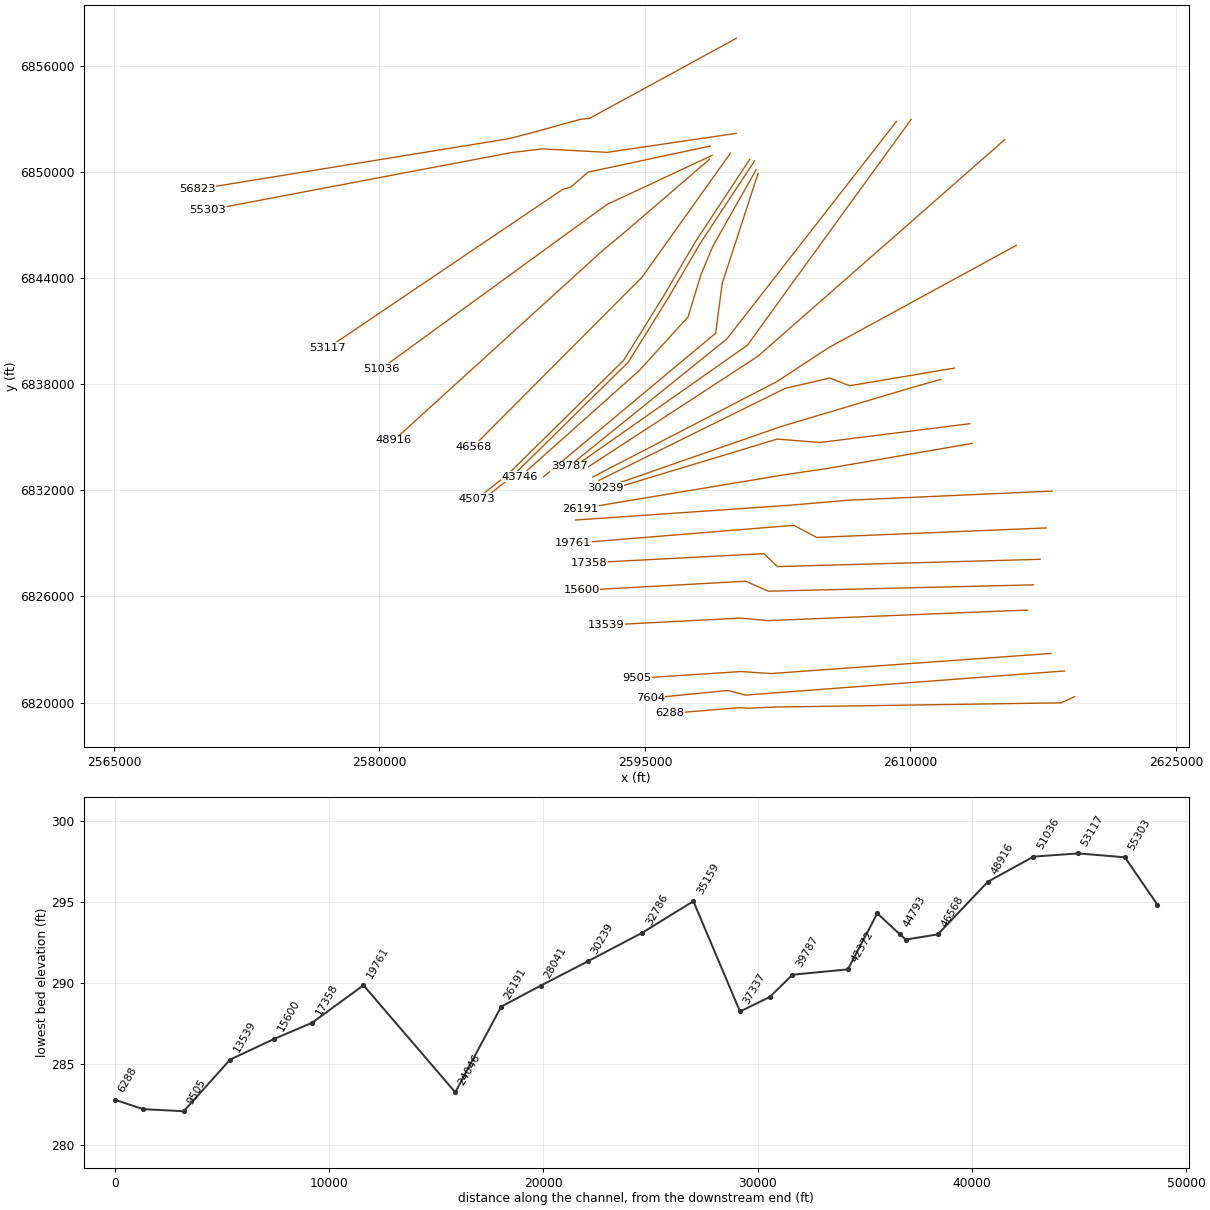
HEC-RAS study TR_FEMA.prj: Trinity_River_FEMA

--- TR_FEMA.g04 (geometry) --- (continued)

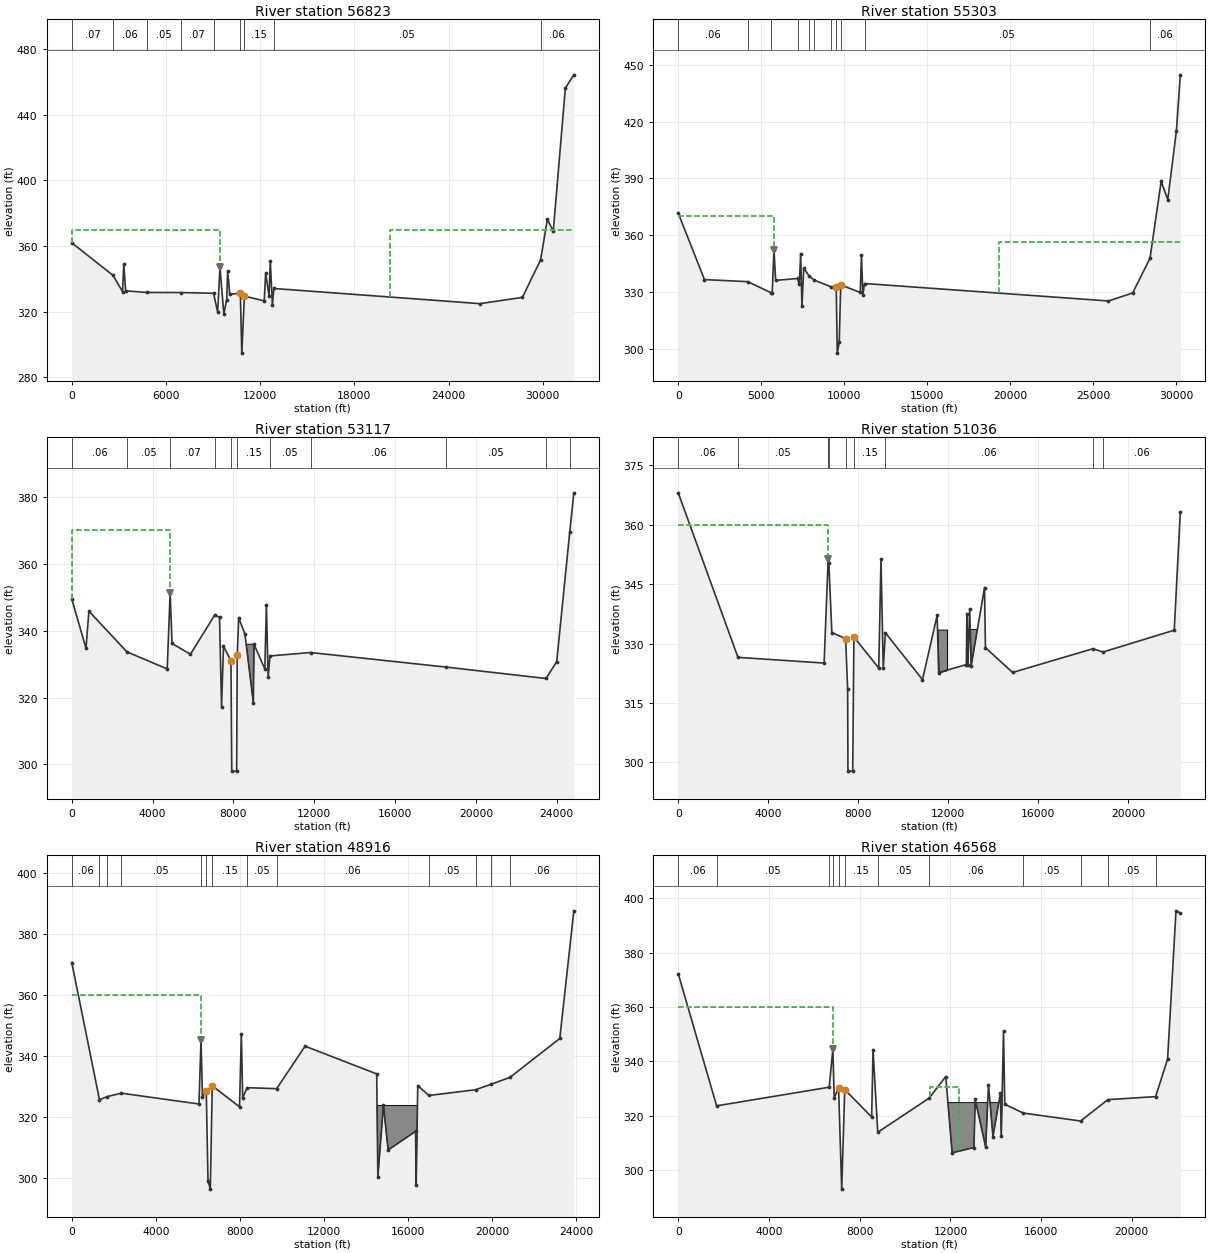
Type RM Length L Ch R = 1 ,56823   ,1814.93,1520.67,905.82
BEGIN DESCRIPTION:
LOB - Kaufman MUD1
END DESCRIPTION:
XS GIS Cut Line= 6
2600164.723589216857545.826660072591868.659144646853018.84982164
2591375.143071296852974.125173552588772.712580656852253.63908173
2587328.241060146851877.223824052569716.981663326849015.22790764
#Sta/Elev= 30
       0  362.01 2628.83  342.19 3233.56  332.27 3313.52  349.09 3433.47  332.78
 4782.89  331.77    6952  331.73 9031.16  331.28 9291.06  319.89 9441.28  347.18
 9686.46  318.71 9869.48  327.38 9931.25  344.8610063.92  330.6410737.48  331.34
10830.73  294.8310995.67  329.5612257.78  326.6612349.83  343.4212568.44  329.76
12644.66  351.0612780.08  324.0812869.66   334.226003.58  324.9628707.25  328.77
29865.42  351.6430294.22  376.3130669.65  369.0431440.07   456.2 31981.7  464.31
#Mann= 9 ,-1 , 0
       0     .07       0 2628.83     .06       0 4782.89     .05       0
    6952     .07       0 9031.16     .15       010737.48    .055       0
10995.67     .15       012869.66     .05       029865.42     .06       0
Levee=-1,9441.28,347.18,0,,,,
#XS Ineff= 2 ,-1
       0 9440.25     370   20271 31981.7     370
Permanent Ineff=
       F       F
Bank Sta=10737.48,10995.67
XS Rating Curve= 0 ,0
Exp/Cntr=0.3,0.1

Type RM Length L Ch R = 1 ,55303   ,1445.25,2185.82,5056.24
BEGIN DESCRIPTION:
LOB - Kaufman LID1/Henderson LID1
END DESCRIPTION:
XS GIS Cut Line= 5
2600163.400754836852175.874097612592870.282117796851101.55589129
2589209.171006686851298.778113522587475.789913646851091.50307786
2570298.522858526847833.26885425
#Sta/Elev= 30
       0  371.61 1581.82  336.57 4183.88  335.49 5588.81  329.68 5664.35  329.61
 5772.52  352.37 5872.48  336.16 7191.94  337.15  7296.9  334.13 7381.86   350.1
 7457.67  322.57 7567.84   342.6 7884.38  338.58 8186.46  336.31 9217.52  332.75
  9523.9  332.52 9587.79  297.76 9704.98  303.41  9795.5  333.7710971.24   329.8
11047.28  349.3511128.37  328.5511231.58  334.5125935.46  325.2927390.41  329.49
28440.88  347.8229112.58  388.4429512.27  378.7730032.44  415.15 30267.6  444.65
#Mann= 11 ,-1 , 0
       0     .06       0 4183.88     .05       0 5588.81     .07       0
 7191.94      .1       0 7884.38     .07       0 8186.46     .15       0
 9217.52     .05       0  9523.9    .055       0  9795.5     .15       0
11231.58     .05       028440.88     .06       0
Levee=-1,5772.52,352.37,0,,,,
#XS Ineff= 2 ,-1
       0 5772.27     370   19335 30267.6   356.5
Permanent Ineff=
       F       F
Bank Sta=9523.9,9795.5
XS Rating Curve= 0 ,0
Exp/Cntr=0.3,0.1

Type RM Length L Ch R = 1 ,53117   ,2370.77,2080.68,2424.78
BEGIN DESCRIPTION:
ROB - Ellis LID2
LOB IFA station 1882: flow expansion due to Kaufman MUD1 levee upstream
END DESCRIPTION:
XS GIS Cut Line= 5
  2598702.505271 6851461.5101835 2591793.5662614 6849984.0356367
 2590815.2676502 6849141.1536922 2590348.3386047 6849003.1768502
 2577092.3232486 6840049.7655826
#Sta/Elev= 30
       0  349.46  704.03  334.71  847.03  345.83 2727.64  333.64 4721.89  328.55
 4866.64  351.19 4961.57  336.15 5870.93  332.92 7075.07  344.69 7309.78  343.96
 7409.86  317.28  7506.3  335.36 7876.59  330.93 7914.65     298 8156.42     298
 8186.86  332.75 8258.81  343.84 8568.46  338.95 8983.23  318.44 9015.18  335.93
 9551.19  328.54 9628.53  347.66 9715.98  326.05  9806.7  332.4311814.35  333.45
18525.39  329.0923461.93  325.6923993.63  330.7424635.51  369.4524839.83  381.18
#Mann= 11 ,-1 , 0
       0     .06       0 2727.64     .05       0 4866.64     .07       0
 7075.07     .15       0 7876.59    .055       0 8186.86     .15       0
  9806.7     .05       011814.35     .06       018525.39     .05       0
23461.93      .1       024635.51     .06       0
Levee=-1,4866.64,351.19,0,,,,
#XS Ineff= 1 ,-1
       0 4865.26     370
Permanent Ineff=
       F
#Block Obstruct= 1 ,-1
 8274.12  9015.8  335.93
Bank Sta=7876.59,8186.86
XS Rating Curve= 0 ,0
Exp/Cntr=0.3,0.1

Type RM Length L Ch R = 1 ,51036   ,2003.75,2119.69,2544.85
BEGIN DESCRIPTION:
LOB - Kaufman LID1/Henderson LID1
END DESCRIPTION:
XS GIS Cut Line= 3
  2598796.934316 6850931.0148033 2592849.0176502 6848149.7648033
 2580108.8727335  6838879.246163
#Sta/Elev= 30
       0  368.03 2655.86  326.51 6485.69  325.07 6666.02  351.37    6696  350.24
 6829.57  332.78 7441.54  331.22 7531.66  318.56 7545.45   297.8 7756.97   297.8
 7810.45  331.64 8914.66  323.82 9014.57  351.34 9114.73  323.79 9209.35  332.72
 10858.6  320.8911511.65  337.0911578.09  322.6712809.38   324.712832.91  337.47
12878.71  324.6412957.17  338.7713025.04  324.4213617.67  344.1113657.95  328.95
14866.75   322.718432.44  328.6818889.25  327.8622052.62  333.3722322.13  363.14
#Mann= 9 ,-1 , 0
       0     .06       0 2655.86     .05       0 6666.02     .15       0
    6696     .07       0 7441.54    .055       0 7810.45     .15       0
 9209.35     .06       018432.44     .05       018889.25     .06       0
Levee=-1,6666.02,351.37,0,,,,
#XS Ineff= 1 ,-1
       0 6663.86     360
Permanent Ineff=
       F
#Block Obstruct= 2 ,-1
11511.6511950.64  333.5212832.9113617.67  333.52
Bank Sta=7441.54,7810.45
XS Rating Curve= 0 ,0
Exp/Cntr=0.3,0.1

Type RM Length L Ch R = 1 ,48916   ,2124.59,2348.27,2946.84
BEGIN DESCRIPTION:
LOB - Kaufman LID1/Henderson LID1
END DESCRIPTION:
XS GIS Cut Line= 4
   2598649.01765 6850708.0981367 2593949.0176502   6846666.43147
 2592504.5732058 6845455.3203589 2580815.6843169 6834824.7648033
#Sta/Elev= 30
       0  370.67 1318.05  325.63 1699.02  326.68 2359.33  327.77 6050.61  324.22
 6148.76  345.36 6216.82  326.62 6398.52  328.34 6480.95  298.98 6590.29  296.26
 6682.71  330.19 7979.77  323.29 8065.83  347.16  8131.5  326.25 8339.73  329.57
 9745.12  329.2611099.58   343.214506.32   334.114560.31  300.1614824.53  323.75
15051.16  309.1216353.98  315.2316382.98  297.5116458.92  330.2816987.79  327.01
   19209   328.919961.17  330.7420843.19  332.9523214.96  345.7423883.86  387.66
#Mann= 13 ,-1 , 0
       0     .06       0 1318.05     .05       0 1699.02     .06       0
 2359.33     .05       0 6148.76     .09       0 6398.52    .055       0
 6682.71     .15       0 8339.73     .05       0 9745.12     .06       0
16987.79     .05       0   19209     .06       019961.17     .05       0
20843.19     .06       0
Levee=-1,6148.76,345.36,0,,,,
#XS Ineff= 1 ,-1
       0 6149.94     360
Permanent Ineff=
       F
#Block Obstruct= 1 ,-1
14499.6916528.76  323.75
Bank Sta=6398.52,6682.71
XS Rating Curve= 0 ,0
Exp/Cntr=0.3,0.1

Type RM Length L Ch R = 1 ,46568   ,1363.21,1495.23,2484.31
BEGIN DESCRIPTION:
LOB - Kaufman LID1/Henderson LID1
END DESCRIPTION:
XS GIS Cut Line= 4
  2599838.304108 6851059.0992941 2595879.8405669 6845507.4499885
 2594848.5905669 6844057.4499885 2585296.6374419 6834461.8770718
#Sta/Elev= 30
       0  372.21 1692.95  323.63 6656.27  330.49 6818.38   344.6 6877.16  326.62
 7069.87   330.2 7207.75     293 7341.88  329.63 8528.83  319.52 8587.94  344.22
 8797.84  313.9211060.18  326.4411796.41  334.4112076.85  306.3513037.44  308.31
13093.66  325.9913555.12  308.4313679.19  331.3513877.93  312.3414203.31  328.33
14243.51  312.3814341.71  351.1414397.55  324.2315206.15  320.9817741.27  318.06
18943.17  325.9121048.57  327.0321576.53  340.8221947.04  395.3622137.24  394.58
#Mann= 12 ,-1 , 0
       0     .06       0 1692.95     .05       0 6656.27     .09       0
 6818.38     .09       0 7069.87    .055       0 7341.88     .15       0
 8797.84     .05       011060.18     .06       015206.15     .05       0
17741.27     .06       018943.17     .05       021048.57     .06       0
Levee=-1,6818.38,344.6,0,,,,
#XS Ineff= 2 ,-1
       0 6818.81     360   11088   12386  330.45
Permanent Ineff=
       F       F
#Block Obstruct= 1 ,-1
11801.95 14322.2  324.82
Bank Sta=7069.87,7341.88
XS Rating Curve= 0 ,0
Exp/Cntr=0.5,0.3

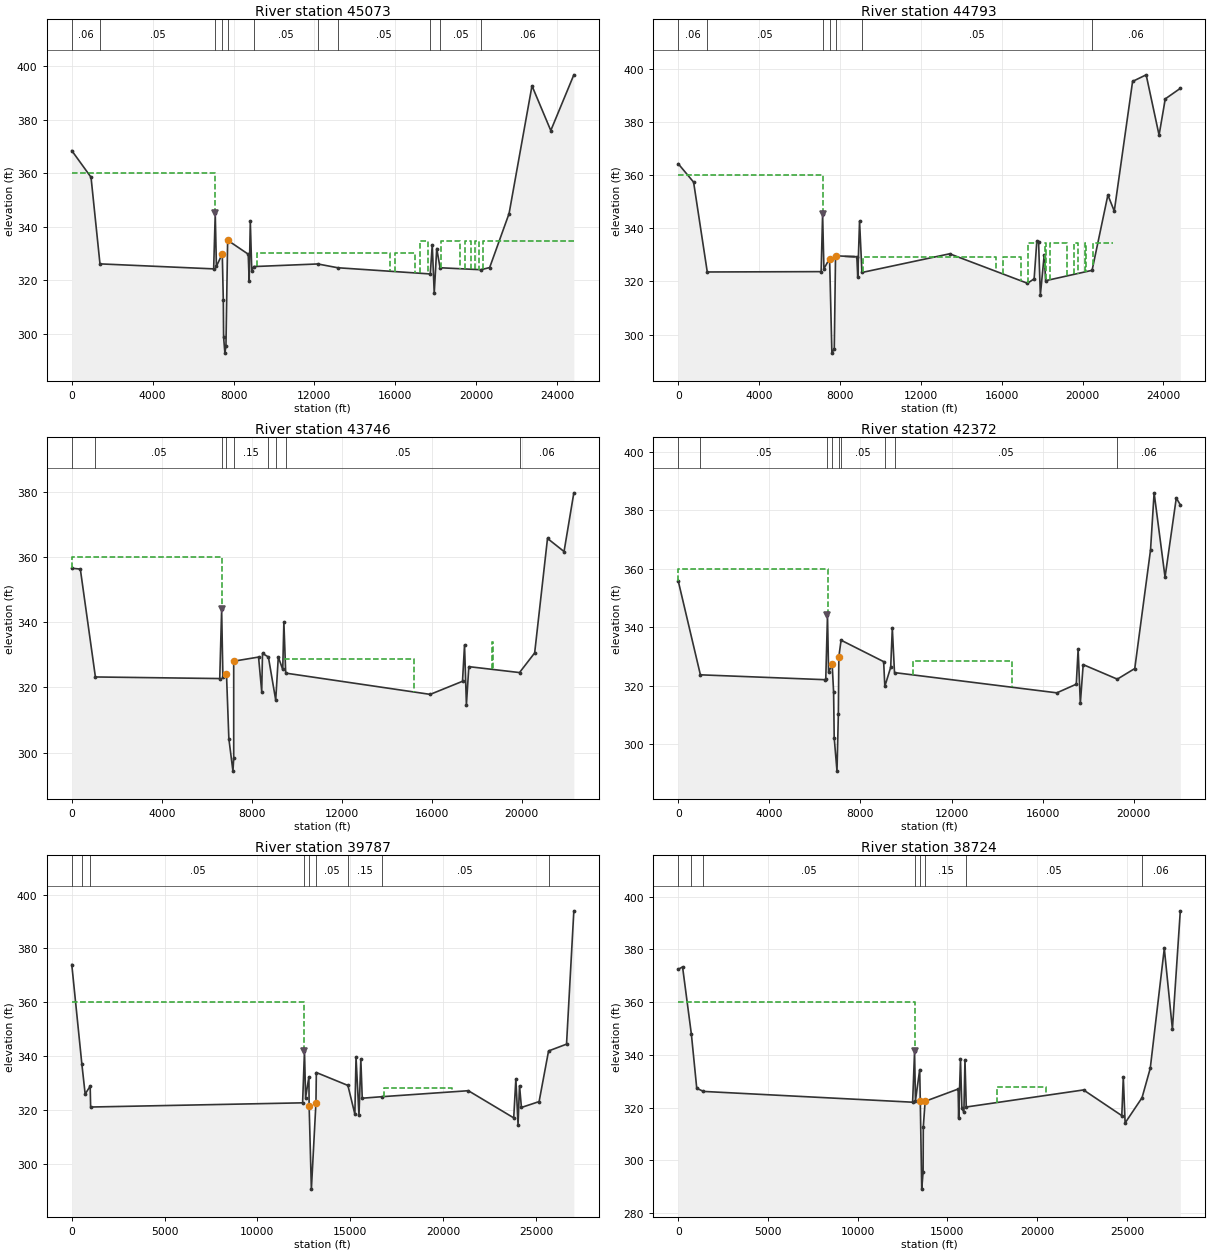
Type RM Length L Ch R = 1 ,45073   ,345.39,280.26,285.37
BEGIN DESCRIPTION:
US Bridge
LOB - Kaufman LID1/Henderson LID1
END DESCRIPTION:
XS GIS Cut Line= 6
  2600926.770416 6850712.1886244 2597846.9093053 6846038.5775133
 2596030.9370831 6842936.1469578 2593793.0898608 6839338.9247355
 2587239.1402081 6832884.5844578  2585513.575972 6831516.0080689
#Sta/Elev= 30
       0  368.47  952.76   358.5 1395.06  326.08 7018.46  324.21 7097.09  344.94
 7154.81  325.17 7444.93  329.81 7496.13  312.38 7510.31   298.7 7574.28  292.68
 7626.64  295.39 7710.21  334.93 8727.83  329.71 8775.26  319.72 8831.57  341.99
 8904.04  323.35 9000.28  325.0712167.55  326.0513159.35  324.6317733.49  322.31
17831.35  333.1517929.29   315.118052.72  331.8318217.56  324.63 20241.9  323.89
20671.26  324.7121631.78  344.9322764.77  392.7223694.75  375.9824835.29  396.83
#Mann= 11 ,-1 , 0
       0     .06       0 1395.06     .05       0 7097.09     .09       0
 7444.93    .055       0 7710.21     .15       0 9000.28     .05       0
12167.55     .06       013159.35     .05       017733.49     .06       0
18217.56     .05       0 20241.9     .06       0
Levee=-1,7097.09,344.94,0,,,,
#XS Ineff= 8 ,-1
       0 7096.81     360    915715722.39     33015982.5416995.54     330
17221.8117634.33   334.618276.2519184.04   334.619444.9419738.26   334.6
19953.1320140.75   334.620354.6324835.29   334.6
Permanent Ineff=
       F       F       F       F       F       F       F       F
Bank Sta=7444.93,7710.21
XS Rating Curve= 0 ,0
Exp/Cntr=0.5,0.3

Type RM Length L Ch R = 1 ,44793   ,681.19,1046.32,1063.06
BEGIN DESCRIPTION:
DS Bridge
LOB - Kaufman LID1/Henderson LID1
END DESCRIPTION:
XS GIS Cut Line= 6
   2601201.10032 6850624.5597711 2598121.2392092 6845950.9486599
  2596305.266987 6842848.5181044 2594067.4197648 6839251.2958822
  2587513.470112 6832796.9556044 2585787.9058759 6831428.3792155
#Sta/Elev= 30
       0  364.25   759.9  357.34 1436.19  323.54 7068.61  323.67 7141.11  345.37
 7205.66  324.75 7486.92   328.6 7600.77  293.01 7718.76   294.7  7781.3  329.62
    8834  329.28 8879.09  321.72 8968.54  342.65 9087.95  323.3513426.66  330.38
17275.59  319.2917604.55  320.9617738.86  335.2717824.38  334.8817912.77  314.86
 18104.1  330.0518172.89  320.2620471.14  324.1621252.55  352.49 21568.6  346.44
22474.59  395.2323146.12  397.71 23784.5  375.0324091.36  388.66 24835.2  392.62
#Mann= 7 ,-1 , 0
       0     .06       0 1436.19     .05       0 7141.11     .09       0
 7486.92    .055       0  7781.3     .09       0 9087.95     .05       0
20471.14     .06       0
Levee=-1,7141.11,345.37,0,,,,
#XS Ineff= 9 ,-1
       0 7141.96     360    9123   15699   329.1   16087   16968   329.1
17314.44   17738   334.3   18140   18201   334.3   18405   19212   334.3
   19594   19753   334.3   20119   20148   334.3   20524   21500   334.3
Permanent Ineff=
       F       F       F       F       F       F       F       F       F
#Block Obstruct= 1 ,-1
 8212.59 8693.81  329.65
Bank Sta=7486.92,7781.3
XS Rating Curve= 0 ,0
Exp/Cntr=0.5,0.3

Type RM Length L Ch R = 1 ,43746   ,782.09,1374.19,1573.74
BEGIN DESCRIPTION:
LOB - Kaufman LID1/Henderson LID1
END DESCRIPTION:
XS GIS Cut Line= 6
   2601283.10594 6850114.9713198 2598849.7726067 6845814.9713198
 2598184.1374419 6844234.0992941 2597436.9152197 6841800.7659607
 2594688.5818863 6838775.3546181 2587952.4707752 6832768.4101737
#Sta/Elev= 30
       0  356.61  380.29  356.35 1050.35  323.22 6576.81  322.73 6661.05  343.98
 6716.36  323.28  6875.8  324.22 6981.87  304.26 7163.12   294.3 7197.19  298.26
 7197.37  328.06 8301.69  329.33 8441.93  318.73 8476.98  330.45  8738.5  329.36
 9064.25  316.11 9178.61  329.34 9376.07  325.53 9426.74  340.03 9508.31   324.4
15930.02  317.8717366.23  321.8917455.67  333.0817539.51  314.6417646.76  326.39
19899.45  324.5720572.74   330.6 21143.6  365.7621878.84  361.7422314.38  379.77
#Mann= 9 ,-1 , 0
       0     .06       0 1050.35     .05       0 6661.05     .15       0
  6875.8    .055       0 7197.37     .15       0  8738.5     .05       0
 9064.25     .15       0 9508.31     .05       019899.45     .06       0
Levee=-1,6661.05,343.98,0,,,,
#XS Ineff= 4 ,-1
       0 6660.86     360    943315197.22  328.7518669.5518735.28   333.9
20772.2122314.38   333.9
Permanent Ineff=
       F       F       F       F
Bank Sta=6875.8,7197.37
XS Rating Curve= 0 ,0
Exp/Cntr=0.3,0.1

Type RM Length L Ch R = 1 ,42372   ,3867.9,2585.3,725.77
BEGIN DESCRIPTION:
LOB - Kaufman LID1/Henderson LID1
END DESCRIPTION:
XS GIS Cut Line= 4
  2601396.573784 6849917.6173496 2599366.7616801 6843692.2464785
 2599000.7404511 6840882.8951274 2589275.7404511 6832767.6173496
#Sta/Elev= 30
       0  355.87  972.79  323.77 6428.02  322.11 6478.47  322.31 6553.92  344.26
 6602.77   324.7 6759.83  327.34 6822.67   317.8 6849.05  302.22 6971.62  290.84
 7031.24  310.42 7052.39  329.93  7150.5  335.61 9020.06  328.28 9072.11  319.82
 9329.57  326.35 9400.68  339.72 9496.65  324.5316625.65  317.6117479.32  320.57
17559.79   332.5 17657.4  314.0417781.89  327.26 19280.6  322.2920047.19  325.92
20739.15  366.4420896.72     38621377.12  357.1521870.54  384.2222047.19   381.9
#Mann= 9 ,-1 , 0
       0     .06       0  972.79     .05       0 6553.92     .15       0
 6759.83    .055       0 7052.39     .15       0  7150.5     .05       0
 9072.11     .15       0 9496.65     .05       0 19280.6     .06       0
Levee=-1,6553.92,344.26,0,,,,
#XS Ineff= 2 ,-1
       0 6555.25     360   1032614673.69   328.6
Permanent Ineff=
       F       F
Bank Sta=6759.83,7052.39
XS Rating Curve= 0 ,0
Exp/Cntr=0.3,0.1

Type RM Length L Ch R = 1 ,39787   ,892.19,1062.65,1007.03
BEGIN DESCRIPTION:
LOB - Kaufman LID1/Henderson LID1
END DESCRIPTION:
XS GIS Cut Line= 3
  2609212.137262 6852849.0371331 2599638.6514077 6840565.1583585
 2590714.0585588 6833359.5000961
#Sta/Elev= 30
       0  374.03  543.82     337  721.29  325.87  990.94   328.8 1015.82  321.04
 12434.1   322.6   12535  342.0312595.48  324.5712773.05   332.312785.25   321.5
12906.56  290.5113152.72   322.613173.96  333.8714873.87  329.0715249.02  318.38
15311.54  339.5715471.06  317.96   15570  338.8615645.78  324.3216688.86  324.87
21361.63  327.1123805.59  317.01   23921  331.5624038.68  314.5324117.98  328.97
24220.47  320.8825172.64  323.0625681.99  341.8926650.31  344.4227044.21     394
#Mann= 9 ,-1 , 0
       0     .06       0  543.82      .1       0  990.94     .05       0
   12535     .15       012785.25    .055       013152.72     .05       0
14873.87     .15       016688.86     .05       025681.99     .06       0
Levee=-1,12535,342.03,0,,,,
#XS Ineff= 2 ,-1
       012534.75     360   1684520478.93  328.25
Permanent Ineff=
       F       F
Bank Sta=12785.25,13152.72
XS Rating Curve= 0 ,0
Exp/Cntr=0.3,0.1

Type RM Length L Ch R = 1 ,38724   ,2589.44,1387.22,926.77
BEGIN DESCRIPTION:
LOB - Kaufman LID1/Henderson LID1
END DESCRIPTION:
XS GIS Cut Line= 4
   2610043.95631 6852965.4574309 2603252.0039816 6843606.0567849
 2600797.9969442 6840205.9265522  2590797.408302 6833183.5301745
#Sta/Elev= 30
       0  372.46  240.88  373.37  733.71  347.78 1031.29  327.36 1406.51  326.17
13061.28  322.0813168.51  341.34 13219.1  322.6713454.97  334.4613486.97   322.7
13568.35  289.13 13644.8  295.6113655.92  312.7313758.43  322.4215596.14  327.07
15625.02  316.0815728.31  338.3415805.02  319.7215917.31  318.2815977.76  338.15
16049.68  320.2622584.53  326.7324717.01  316.9924800.38  331.5824901.51  314.22
25843.56  323.7726302.09  334.9127085.14  380.3727536.79  349.7627977.22  394.63
#Mann= 8 ,-1 , 0
       0     .06       0  733.71      .1       0 1406.51     .05       0
13168.51     .15       013486.97    .055       013758.43     .15       0
16049.68     .05       025843.56     .06       0
Levee=-1,13168.51,341.34,0,,,,
#XS Ineff= 2 ,-1
       013169.59     360   1774920509.89     328
Permanent Ineff=
       F       F
Bank Sta=13486.97,13758.43
XS Rating Curve= 0 ,0
Exp/Cntr=0.3,0.1

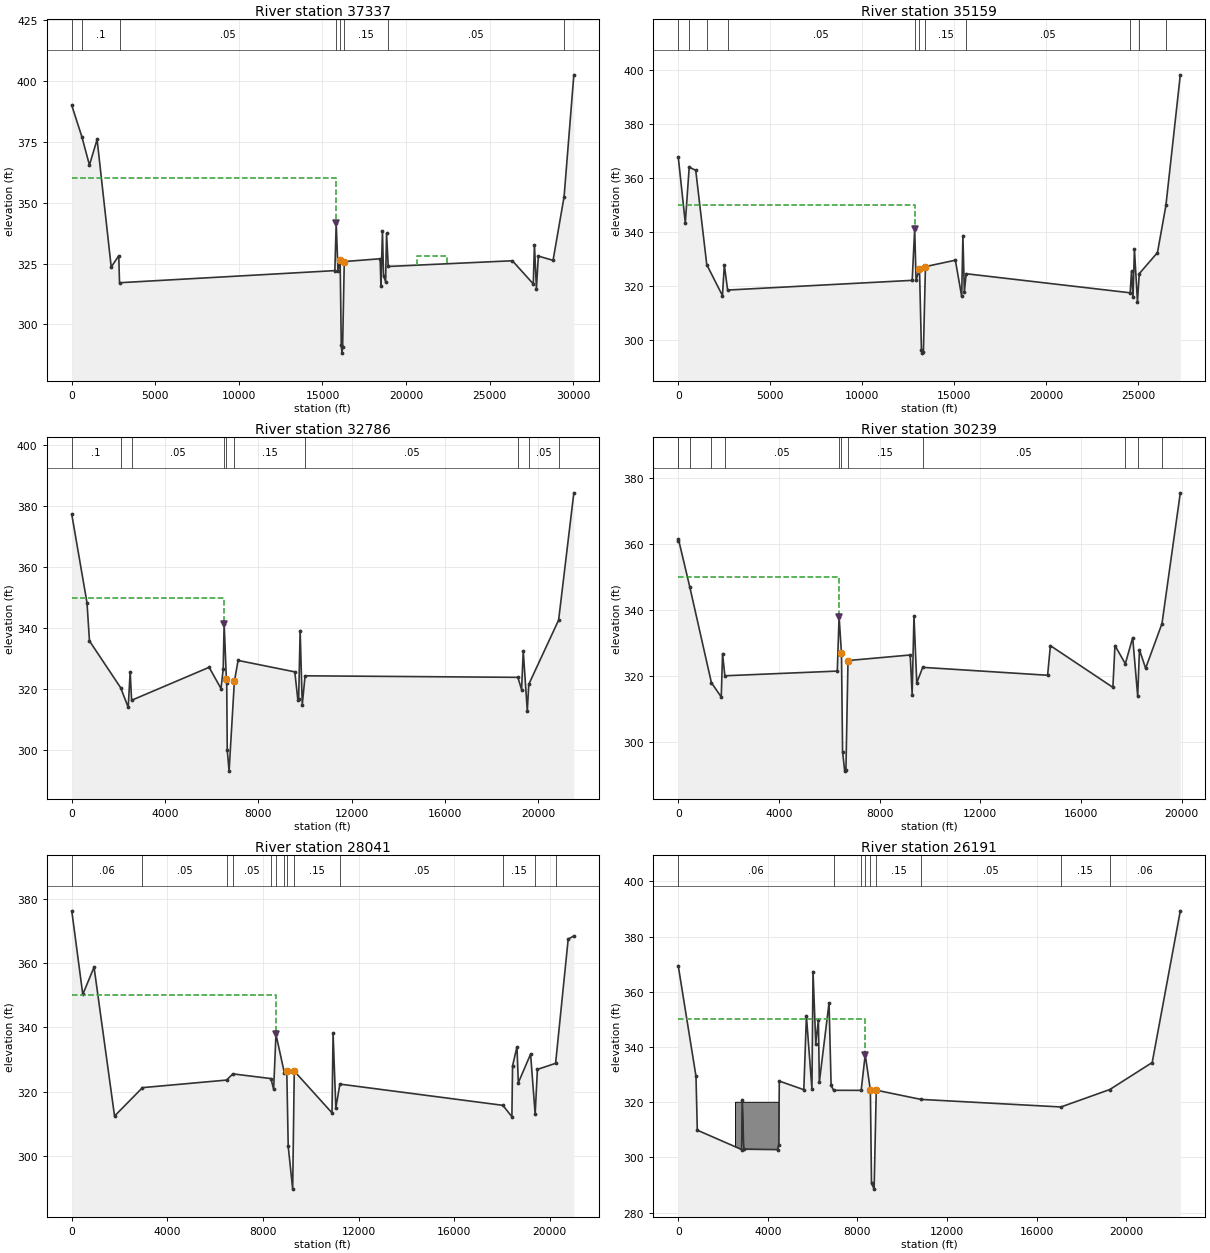
Type RM Length L Ch R = 1 ,37337   ,3427.32,2177.73,1690.74
BEGIN DESCRIPTION:
LOB - Kaufman LID1/Henderson LID1
END DESCRIPTION:
XS GIS Cut Line= 3
  2615335.622977 6851823.7907643 2601386.6348669 6839577.7655373
 2591771.9152196 6833306.6046181
#Sta/Elev= 30
       0  389.89  601.66   377.1 1058.46  365.41 1515.82  375.93 2360.04  323.58
 2810.74  328.21 2857.44  317.1315741.77   322.115822.04  341.7515928.32  321.93
16057.47  326.4716125.44  291.57   16168  288.2416205.98  290.8716304.57  325.82
18451.41  326.9718498.33  315.9218589.38   338.218653.98  320.0118776.11  317.58
18835.12  337.37 18934.7   323.826364.29  326.1527613.66  316.6427683.05  332.72
27802.17   314.727916.74  328.0628797.64  326.3229457.16  352.4430040.95  402.45
#Mann= 8 ,-1 , 0
       0     .06       0  601.66      .1       0 2857.44     .05       0
15822.04     .15       016057.47    .055       016304.57     .15       0
 18934.7     .05       029457.16     .06       0
Levee=-1,15822.04,341.75,0,,,,
#XS Ineff= 2 ,-1
       015821.49     360   2065822430.71   327.9
Permanent Ineff=
       F       F
Bank Sta=16057.47,16304.57
XS Rating Curve= 0 ,0
Exp/Cntr=0.3,0.1

Type RM Length L Ch R = 1 ,35159   ,3333.38,2373.47,517.22
BEGIN DESCRIPTION:
LOB - Kaufman LID1/Henderson LID1
END DESCRIPTION:
XS GIS Cut Line= 4
   2615990.11631 6845847.5727087 2605372.0607548 6840058.6838198
 2602487.6690384 6838160.7157798 2592049.6929974 6832751.0490626
#Sta/Elev= 30
       0  367.84  383.55  343.38   596.9  364.04  951.99  362.81 1551.25  327.86
 2404.04  316.38 2506.63  327.68 2685.93  318.4412722.47  322.0412857.72  341.16
12934.03  322.1713119.58  326.26 13225.6  296.15 13282.3  295.0513332.27  295.53
13443.18  327.1415069.93  329.5115413.88  316.0815480.15  338.6415558.94  317.61
15656.95  324.4924576.89  317.4224649.26  325.3424730.47  315.8624807.06  333.62
24972.62  314.1725070.94  324.5226060.58  332.3326519.65  349.8127302.92  398.25
#Mann= 11 ,-1 , 0
       0      .1       0   596.9     .06       0 1551.25      .1       0
 2685.93     .05       012857.72     .15       013119.58    .055       0
13443.18     .15       015656.95     .05       024576.89     .15       0
25070.94     .05       026519.65     .06       0
Levee=-1,12857.72,341.16,0,,,,
#XS Ineff= 1 ,-1
       012857.82     350
Permanent Ineff=
       F
Bank Sta=13119.58,13443.18
XS Rating Curve= 0 ,0
Exp/Cntr=0.3,0.1

Type RM Length L Ch R = 1 ,32786   ,932.09,2546.34,1762.9
BEGIN DESCRIPTION:
LOB - Kaufman LID1/Henderson LID1
END DESCRIPTION:
XS GIS Cut Line= 5
   2612477.24508 6838907.2006829   2606570.87934 6837910.0942014
 2605434.6766815 6838344.2164293 2602926.8978586 6837761.6567014
 2592404.3284141 6832563.4506829
#Sta/Elev= 30
       0  377.24   652.7  348.29  758.57  335.77 2095.92  320.44 2418.58  314.01
  2503.3   325.7 2563.95  316.33 5886.86  327.14 6395.95  320.17 6489.72  326.52
 6529.91  341.49 6625.46  323.35 6640.64  322.08 6663.42  300.01 6742.11  293.11
 6968.26  322.49  7127.6  329.39 9558.81  325.64 9688.36  316.51 9723.16  316.79
 9787.39  339.17 9877.91  314.83 9998.96  324.3519117.69  323.8519277.15  319.85
19348.81   332.419521.83  312.9719586.63  321.5820864.95  342.6221517.27  384.32
#Mann= 10 ,-1 , 0
       0      .1       0 2095.92     .06       0 2563.95     .05       0
 6529.91     .15       0 6625.46    .055       0 6968.26     .15       0
 9998.96     .05       019117.69     .15       019586.63     .05       0
20864.95     .06       0
Levee=-1,6529.91,341.49,0,,,,
#XS Ineff= 2 , 0
       0 6530.07     350               0
Permanent Ineff=
       F       F
Bank Sta=6625.46,6968.26
XS Rating Curve= 0 ,0
Exp/Cntr=0.3,0.1

Type RM Length L Ch R = 1 ,30239   ,2121.82,2198.11,574.75
BEGIN DESCRIPTION:
LOB - Kaufman LID1/Henderson LID1
END DESCRIPTION:
XS GIS Cut Line= 4
  2611724.189525 6838270.3025348 2610022.1061919 6837788.7053126
  2602711.342303  6835611.274757 2592744.1374419 6832143.4101737
#Sta/Elev= 30
       0  361.04    8.18  361.52  462.84  346.92 1317.94  318.09 1708.85  313.77
 1761.26   326.9  1852.1  320.18 6320.15   321.6  6391.5  338.05 6486.82  326.95
 6530.21  297.24 6614.31  291.34 6663.86  291.79 6746.07  324.79 9217.26  326.47
 9294.63  314.49 9367.52  338.23 9478.18  318.03 9713.62  322.7314677.13  320.34
14787.63  329.2917271.11  316.6817353.89  329.3217765.76  323.8218058.24  331.72
18257.43  313.9818326.52  328.0618571.96  322.4519222.44  335.9819950.38  375.52
#Mann= 12 ,-1 , 0
       0      .1       0    8.18     .06       0  462.84      .1       0
 1317.94     .06       0  1852.1     .05       0  6391.5     .15       0
 6486.82    .055       0 6746.07     .15       0 9713.62     .05       0
17765.76     .15       018257.43     .05       019222.44     .06       0
Levee=-1,6391.5,338.05,0,,,,
#XS Ineff= 2 , 0
       0 6391.11     350               0
Permanent Ineff=
       F       F
Bank Sta=6486.82,6746.07
XS Rating Curve= 0 ,0
Exp/Cntr=0.3,0.1

Type RM Length L Ch R = 1 ,28041   ,1424.7,1850.02,1966.69
BEGIN DESCRIPTION:
LOB - Kaufman LID1/Henderson LID1
END DESCRIPTION:
XS GIS Cut Line= 4
   2613364.12008 6835765.9043866  2604898.842303 6834703.4043866
 2602469.6756363 6834894.7238311 2592864.1200808 6831988.1266088
#Sta/Elev= 30
       0  376.19  460.84  350.26  932.26  358.71 1789.54  312.52  2958.9  321.33
  6477.9  323.68 6737.59   325.6 8331.43  324.14 8445.45  320.81 8541.68  337.89
 8891.15  326.02 8995.21  326.45  9054.8  303.11 9241.87  289.84 9307.65  326.47
10887.19   313.510931.68   338.2 11047.2  315.0111215.96  322.4318035.58  315.84
18412.18  312.3118440.22  328.0818624.09  333.9918681.23  322.8419194.99  331.74
19385.52   313.119479.95  326.9920240.48  328.8720767.51  367.4321004.03   368.4
#Mann= 13 ,-1 , 0
       0     .06       0  2958.9     .05       0  6477.9     .06       0
 6737.59     .05       0 8331.43     .06       0 8541.68     .06       0
 8891.15     .15       0 8995.21    .055       0 9307.65     .15       0
11215.96     .05       018035.58     .15       019385.52     .05       0
20240.48     .06       0
Levee=-1,8541.68,337.89,0,,,,
#XS Ineff= 2 , 0
       0 8540.92     350               0
Permanent Ineff=
       F       F
Bank Sta=8995.21,9307.65
XS Rating Curve= 0 ,0
Exp/Cntr=0.3,0.1

Type RM Length L Ch R = 1 ,26191   ,2208.75,2145.1,1627.42
BEGIN DESCRIPTION:
LOB - Kaufman LID1/Henderson LID1
END DESCRIPTION:
XS GIS Cut Line= 4
  2613487.036747 6834653.0571644 2605281.5679974 6833229.0120255
 2602909.4104089 6832882.7844453 2591372.6096641 6830962.8546181
#Sta/Elev= 30
       0  369.47   792.5  329.42  851.69  309.89 2830.34  302.89 2862.46  320.93
 2924.58     303 4439.92  302.85 4492.11  304.67 4512.69  327.68 5608.19  324.55
 5723.38  351.24 5970.42  324.82    6019  367.34 6141.37  341.26  6259.7  349.97
 6300.58  327.26 6735.18  356.02 6827.04  326.08 6938.13  324.34 8169.06  324.31
 8350.68   337.3 8579.84  324.38 8630.98  290.66 8747.63  288.54 8842.51  324.38
10837.65  321.0417091.92   318.319269.76  324.6121165.59   334.422420.79  389.34
#Mann= 9 ,-1 , 0
       0     .06       0 6938.13     .05       0 8169.06     .06       0
 8350.68     .06       0 8579.84    .055       0 8842.51     .15       0
10837.65     .05       017091.92     .15       019269.76     .06       0
Levee=-1,8350.68,337.3,0,,,,
#XS Ineff= 2 , 0
       0 8350.54     350               0
Permanent Ineff=
       F       F
#Block Obstruct= 1 ,-1
  2559.9 4512.69     320
Bank Sta=8579.84,8842.51
XS Rating Curve= 0 ,0
Exp/Cntr=0.3,0.1

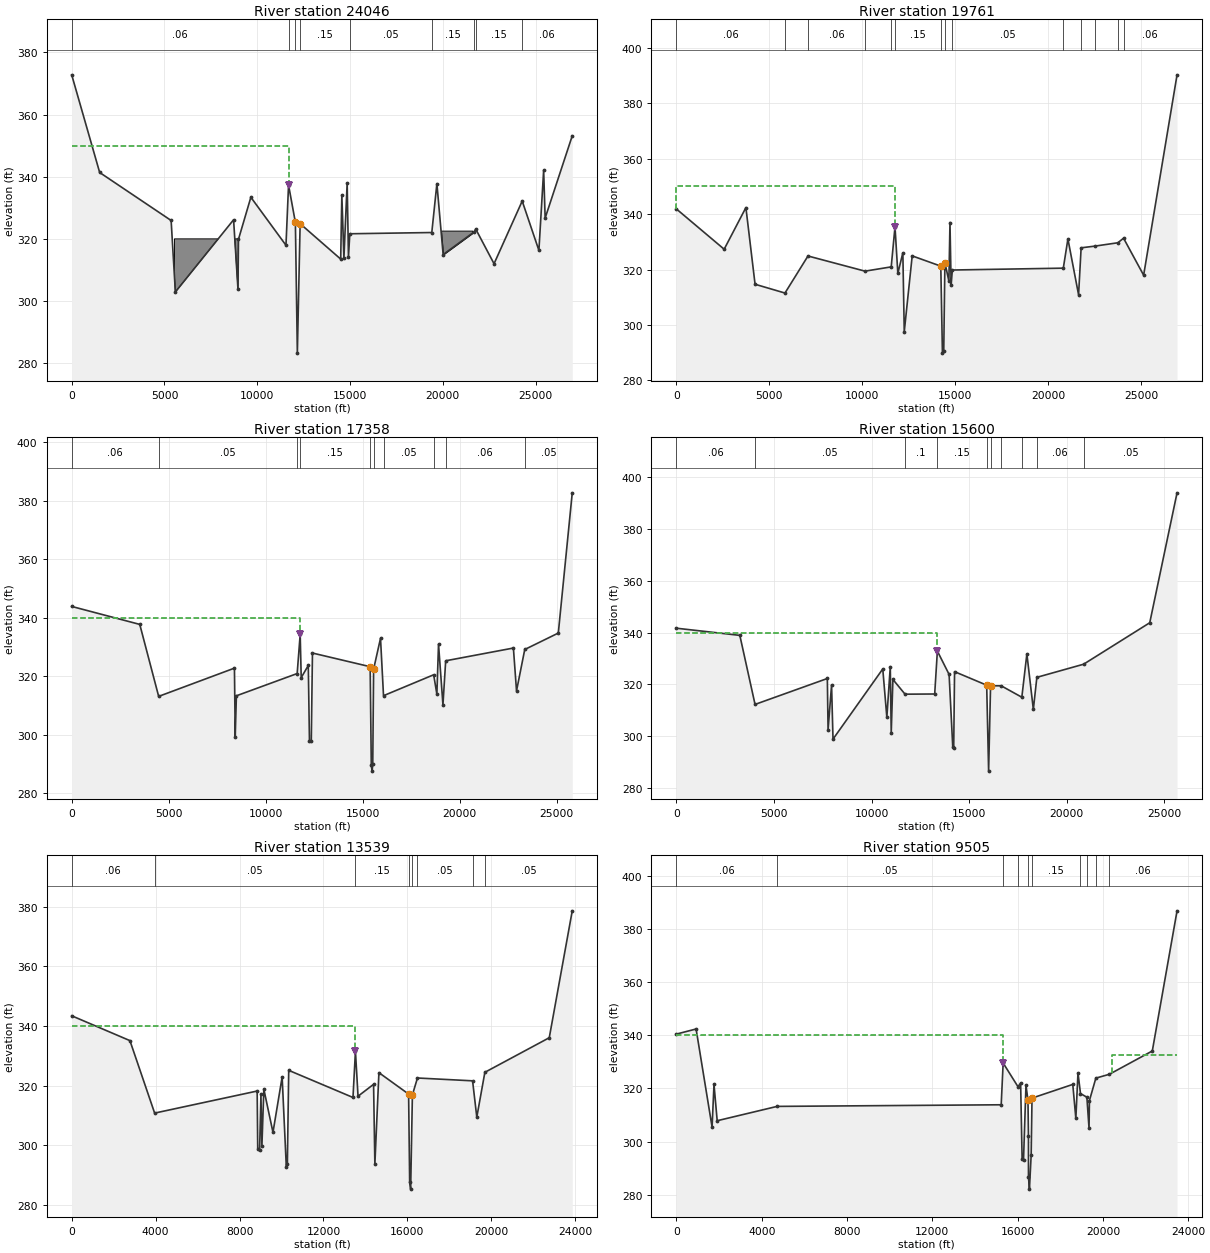
Type RM Length L Ch R = 1 ,24046   ,2150.45,4285.27,1243.91
BEGIN DESCRIPTION:
LOB - Kaufman LID1/Henderson LID1
END DESCRIPTION:
XS GIS Cut Line= 4
  2618005.516276 6831956.4031599 2606504.9013308 6831441.7203589
 2603206.9846641 6831158.3870255 2591081.3268229 6830320.2000931
#Sta/Elev= 30
       0  372.76 1507.73  341.35 5358.95  325.91 5587.33  302.91 8724.77  326.14
 8961.27  303.85 8988.06  319.85 9656.12  333.38 11548.2  317.9411686.88  337.32
12055.11   325.312161.19  283.2512311.37  324.8814497.88  313.4914558.98  334.14
14670.65  313.8414846.15  337.9814915.68  314.1314988.75  321.6419406.97  322.04
19681.62  337.7720018.37  314.9521692.26  322.2521774.55  323.1622761.67     312
24279.19  332.1625179.28  316.2925435.15  342.0325515.71  326.6926976.66  353.15
#Mann= 9 ,-1 , 0
       0     .06       011686.88     .06       012055.11    .055       0
12311.37     .15       014988.75     .05       019406.97     .15       0
21692.26     .05       021774.55     .15       024279.19     .06       0
Levee=-1,11686.88,337.32,0,,,,
#XS Ineff= 2 , 0
       011688.81     350               0
Permanent Ineff=
       F       F
#Block Obstruct= 2 ,-1
 5539.12 8988.06     32019868.5521590.32  322.66
Bank Sta=12055.11,12311.37
XS Rating Curve= 0 ,0
Exp/Cntr=0.3,0.1

Type RM Length L Ch R = 1 ,19761   ,1667.72,2402.96,1502.54
BEGIN DESCRIPTION:
LOB - Kaufman LID1/Henderson LID1
END DESCRIPTION:
XS GIS Cut Line= 4
  2617675.582382  6829873.695452 2604705.0561615 6829337.5528737
 2603411.4228539 6830022.0524582 2590950.9369418 6829007.6189793
#Sta/Elev= 30
       0  341.85 2566.34  327.35  3736.7  342.38 4229.96  314.71 5839.93  311.54
  7078.7  324.9110148.36  319.4411558.66  320.9811763.17  335.44 11915.8  318.63
12185.79  326.0612261.16  297.5812688.54  324.9514228.22  321.25 14316.2  289.86
14387.41  290.4714449.01  322.5614664.05  315.8714722.77  336.99 14784.7  314.39
14850.28  319.8520823.65  320.5221071.54  331.0621645.63  310.9221782.82  327.86
22513.25  328.4623758.59  329.6824066.84  331.3325148.06  317.98 26946.9  390.28
#Mann= 14 ,-1 , 0
       0     .06       0 5839.93     .05       0  7078.7     .06       0
10148.36     .05       011558.66      .1       011763.17     .15       0
14228.22    .055       014449.01     .15       014850.28     .05       0
20823.65     .15       021782.82     .06       022513.25     .15       0
23758.59     .05       024066.84     .06       0
Levee=-1,11763.17,335.44,0,,,,
#XS Ineff= 2 , 0
       011763.38     350               0
Permanent Ineff=
       F       F
Bank Sta=14228.22,14449.01
XS Rating Curve= 0 ,0
Exp/Cntr=0.3,0.1

Type RM Length L Ch R = 1 ,17358   ,1420.5,1758.18,1573.47
BEGIN DESCRIPTION:
LOB - Kaufman LID1/Henderson LID1
END DESCRIPTION:
XS GIS Cut Line= 4
  2617325.027619   6828100.30077 2602483.9771289 6827689.9468975
 2601723.6513308 6828420.8407292 2591844.9203689 6827903.9698543
#Sta/Elev= 30
       0  343.84 3507.69   337.7 4481.58  313.09 8386.33  322.75 8426.59  299.28
 8486.79  313.2911618.63   320.911773.99  334.3111826.98  319.5112191.52  323.65
12251.93   297.812345.92  297.7512406.34  327.9115379.45  323.2415438.49  289.48
15479.56  287.5415513.17  289.8515557.89  322.4215913.33  332.9516067.94  313.33
18652.41  320.4818817.39  313.8418902.67  330.9619130.18   310.219271.54  325.26
22761.06  329.6222921.87  314.9723345.55  329.1225074.75  334.7425793.57  382.68
#Mann= 10 ,-1 , 0
       0     .06       0 4481.58     .05       011618.63      .1       0
11773.99     .15       015379.45    .055       015557.89     .15       0
16067.94     .05       018652.41     .15       019271.54     .06       0
23345.55     .05       0
Levee=-1,11773.99,334.31,0,,,,
#XS Ineff= 2 , 0
       011775.13     340               0
Permanent Ineff=
       F       F
Bank Sta=15379.45,15557.89
XS Rating Curve= 0 ,0
Exp/Cntr=0.3,0.1

Type RM Length L Ch R = 1 ,15600   ,1608.95,2060.49,2106.04
BEGIN DESCRIPTION:
LOB - Kaufman LID1/Henderson LID1
END DESCRIPTION:
XS GIS Cut Line= 4
  2616953.851988 6826656.8399823 2601977.2145359 6826298.6985631
 2600689.1096641  6826862.618507 2591425.2169149 6826347.5269563
#Sta/Elev= 30
       0  341.69 3247.39  338.93 4027.84  312.29  7734.2  322.29 7771.73  302.44
 7951.05  319.79 8024.98   298.910576.64  325.9810785.35  307.3210961.44  326.86
11009.95   301.311095.96  321.9211718.38  316.2413238.98  316.3113375.88  332.87
13977.19  323.8714166.39  295.6914213.29  295.57 14257.6  324.9315904.39  319.71
 16003.8  286.5516103.74 319.47616648.49  319.4717706.17  315.07 17965.2  331.78
18296.69  310.3718477.35  322.7420873.65   327.824265.14   343.825665.24  393.93
#Mann= 10 ,-1 , 0
       0     .06       0 4027.84     .05       011718.38      .1       0
13375.88     .15       015904.39    .055       016103.74     .15       0
16648.49     .05       017706.17     .15       018477.35     .06       0
20873.65     .05       0
Levee=-1,13375.88,332.87,0,,,,
#XS Ineff= 2 , 0
       013375.87     340               0
Permanent Ineff=
       F       F
Bank Sta=15904.39,16103.74
XS Rating Curve= 0 ,0
Exp/Cntr=0.3,0.1

Type RM Length L Ch R = 1 ,13539   ,1853.81,2167.97,2021.98
BEGIN DESCRIPTION:
LOB - Kaufman LID1/Henderson LID1
END DESCRIPTION:
XS GIS Cut Line= 4
  2616623.918094  6825234.000063 2601962.4806649 6824635.9948795
 2600358.5541085 6824776.2990626 2592791.3708253 6824383.1898411
#Sta/Elev= 30
       0  343.39 2775.84  335.06 3953.71  310.76 8841.22  318.16 8867.95  298.84
 8957.82  298.42 9020.78  317.01 9066.89  299.69 9158.91  318.78 9594.84   304.3
10031.85  322.8710230.43   292.8 10280.7  293.5710345.09   325.113408.84     316
13525.78  331.5113649.38  316.4214390.17  320.4114452.01  293.6114644.67  324.32
16060.18  317.1416110.86  287.5716157.83  285.2716241.02 316.86316481.97  322.53
 19109.8  321.58 19310.9  309.4119695.51  324.4422765.08  336.0323861.07  378.58
#Mann= 8 ,-1 , 0
       0     .06       0 3953.71     .05       013525.78     .15       0
16060.18    .055       016241.02     .15       016481.97     .05       0
 19109.8     .15       019695.51     .05       0
Levee=-1,13525.78,331.51,0,,,,
#XS Ineff= 2 , 0
       013521.13     340               0
Permanent Ineff=
       F       F
Bank Sta=16060.18,16241.02
XS Rating Curve= 0 ,0
Exp/Cntr=0.3,0.1

Type RM Length L Ch R = 1 ,9505    ,1134.79,1900.98,1032.38
BEGIN DESCRIPTION:
LOB - Kaufman LID1/Henderson LID1
END DESCRIPTION:
XS GIS Cut Line= 4
  2617943.653671  6822780.116724 2602120.2802758  6821643.751677
 2600430.9125433 6821757.1829476 2594525.7712673 6821374.0195375
#Sta/Elev= 30
       0   340.5  919.31  342.41  1668.9  305.46 1758.73  321.51 1908.43  307.85
 4718.92  313.25 15227.5  313.8615319.42  329.5916014.85  320.6716138.72  322.04
16208.93  293.4216274.19  293.01 16389.1  321.1916483.71  315.5916505.97  302.11
16507.06   286.616552.25  282.0816633.09  294.9316672.79  316.3718584.62  321.53
18728.66  308.7218828.48  325.8918946.26  318.0919245.89  316.7119346.87  305.02
19365.78  315.4519666.52   323.920300.58  325.3522314.28  334.1323474.79  386.93
#Mann= 10 ,-1 , 0
       0     .06       0 4718.92     .05       015319.42     .06       0
16014.85     .15       016483.71    .055       016672.79     .15       0
18946.26     .05       019245.89     .15       019666.52     .05       0
20300.58     .06       0
Levee=-1,15319.42,329.59,0,,,,
#XS Ineff= 2 , 0
       015319.21     34020419.34       0   332.5
Permanent Ineff=
       F       F
Bank Sta=16483.71,16672.79
XS Rating Curve= 0 ,0
Exp/Cntr=0.3,0.1

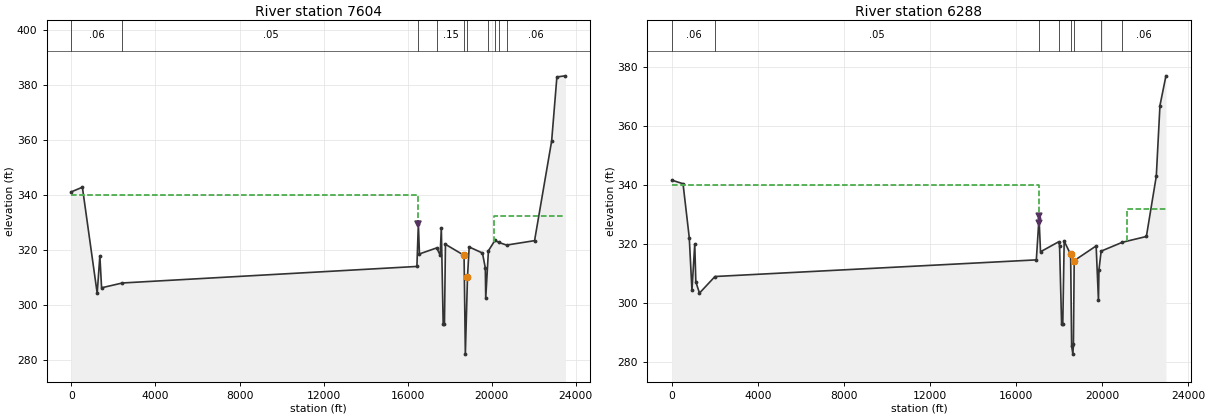
Type RM Length L Ch R = 1 ,7604    ,1109.26,1315.69,1024.77
BEGIN DESCRIPTION:
LOB - Kaufman LID1/Henderson LID1
END DESCRIPTION:
XS GIS Cut Line= 4
  2618706.625802  6821790.315041 2600688.1924188 6820426.8980209
  2599694.164641 6820689.1896876 2595306.2479743 6820253.2869098
#Sta/Elev= 30
       0  341.11  524.17  342.78 1228.28   304.3 1355.65  317.87 1437.33  306.28
 2425.82  308.0316439.61  314.0316509.06  329.6116559.86  318.5717380.66  320.75
17546.34  318.1217601.51  327.9817689.72  293.1217750.21  292.9817797.94  322.06
18683.77  318.0518744.51  282.2118846.83  310.2818926.93   321.119558.28   318.9
19694.32  313.4819714.03  302.4719842.43  319.7220153.77  323.4920349.21  322.72
20704.53  321.7822037.77  323.3922850.49  359.5523099.93   382.823507.45   383.2
#Mann= 10 ,-1 , 0
       0     .06       0 2425.82     .05       016509.06     .06       0
17380.66     .15       018683.77    .055       018846.83     .15       0
19842.43     .05       020153.77     .15       020349.21     .05       0
20704.53     .06       0
Levee=-1,16509.06,329.61,0,,,,
#XS Ineff= 2 , 0
       0   16509     34020091.76       0   332.5
Permanent Ineff=
       F       F
Bank Sta=18683.77,18846.83
XS Rating Curve= 0 ,0
Exp/Cntr=0.3,0.1

Type RM Length L Ch R = 1 ,6288    ,0,0,0
BEGIN DESCRIPTION:
LOB - Kaufman LID1/Henderson LID1
END DESCRIPTION:
XS GIS Cut Line= 6
2619293.73848072 6820341.02639792618516.223959626819988.94081597
2602318.95386082 6819749.15356592600866.164771656819685.79903381
2600323.704570476819714.953503062596424.624770226819393.00007872
#Sta/Elev= 30
       0  341.78   519.1  340.57   808.6  322.28  933.51  304.43 1063.51  320.15
  1113.5  307.29 1283.49  303.49 2003.45  309.1116938.12  314.7517063.12  328.99
17133.08   317.517972.71  320.8718017.69   319.618112.65  292.8618167.63  292.91
 18232.6  321.1118532.45  316.58 18578.5   285.518636.94  282.7918662.12  286.18
18698.05  314.4919717.65  319.4819825.78  300.99   19849  311.3819950.19  317.71
20936.78  320.7222052.49  322.6822513.65  343.1422683.49  367.0922962.33  377.16
#Mann= 8 ,-1 , 0
       0     .06       0 2003.45     .05       017063.12     .06       0
17972.71     .15       018532.45    .055       018698.05     .15       0
19950.19     .05       020936.78     .06       0
Levee=-1,17048.12,329.68,0,,,,
#XS Ineff= 2 , 0
       017048.58     340   21133       0     332
Permanent Ineff=
       F       F
Bank Sta=18532.45,18698.05
XS Rating Curve= 0 ,0
Exp/Cntr=0.3,0.1
Stream Node=Trinity River   ,                , 0 , 0 ,Upstream end
Stream Node=Trinity River   ,                , 0 , 1 ,Downstream end
LCMann Table=0

--- TR_FEMA.g05 (geometry) ---

Geom Title=Trinity_NV_KaufMUD1
Program Version=5.06
BEGIN GEOM DESCRIPTION:
Scenario C
END GEOM DESCRIPTION:

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
River Reach=Trinity River   ,1