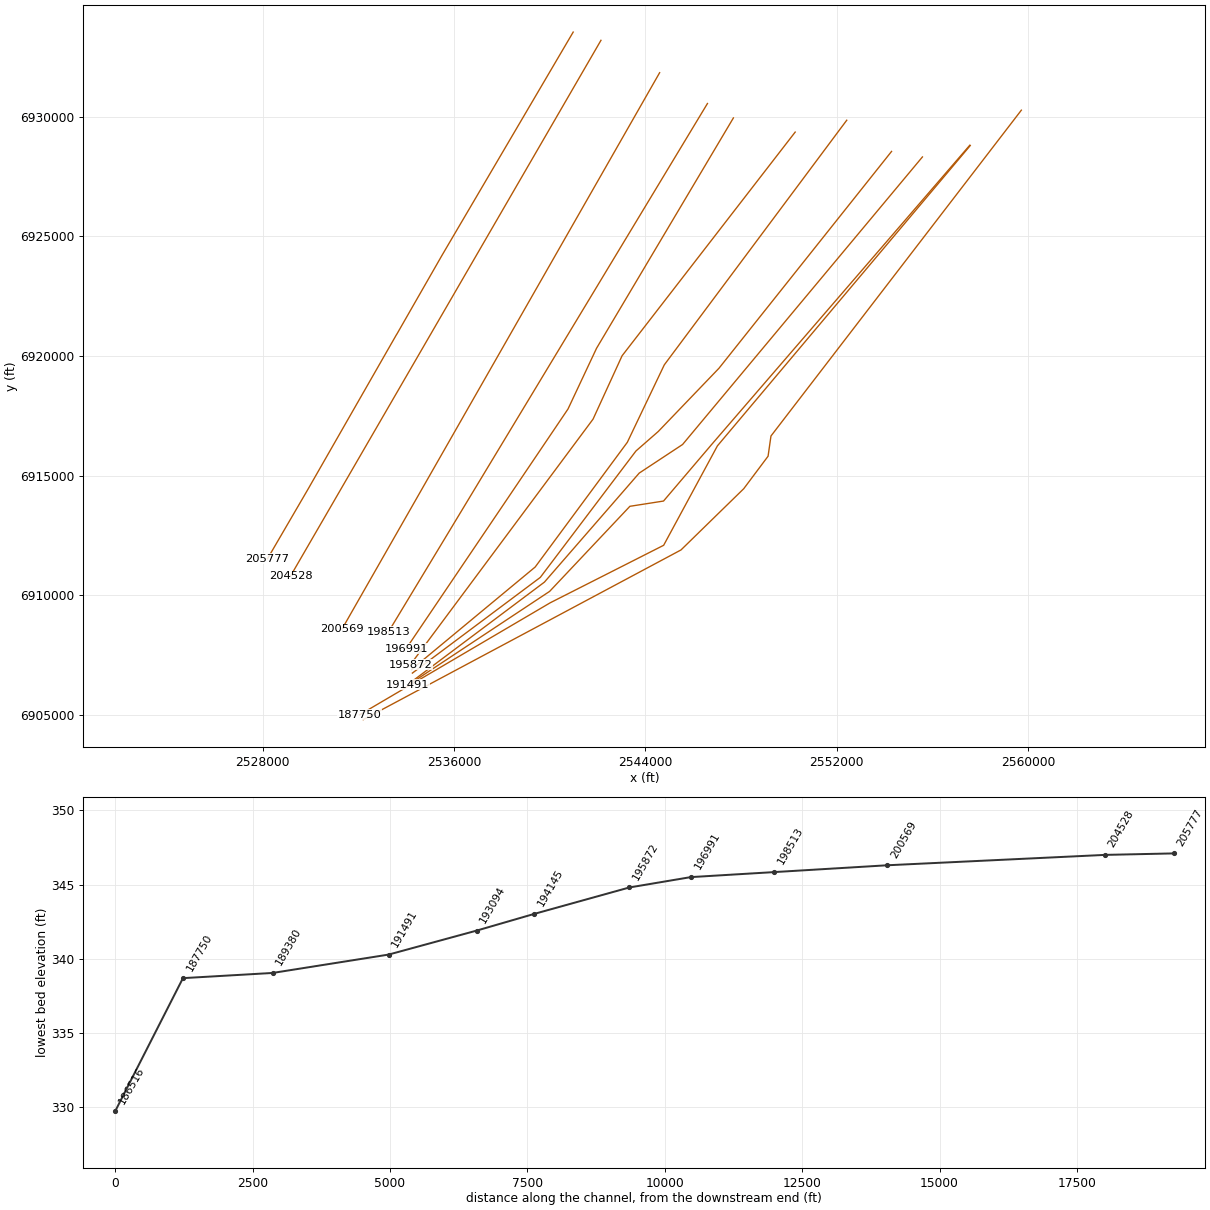
HEC-RAS study TR_FEMA.prj: Trinity_River_FEMA

--- TR_FEMA.g05 (geometry) --- (continued)

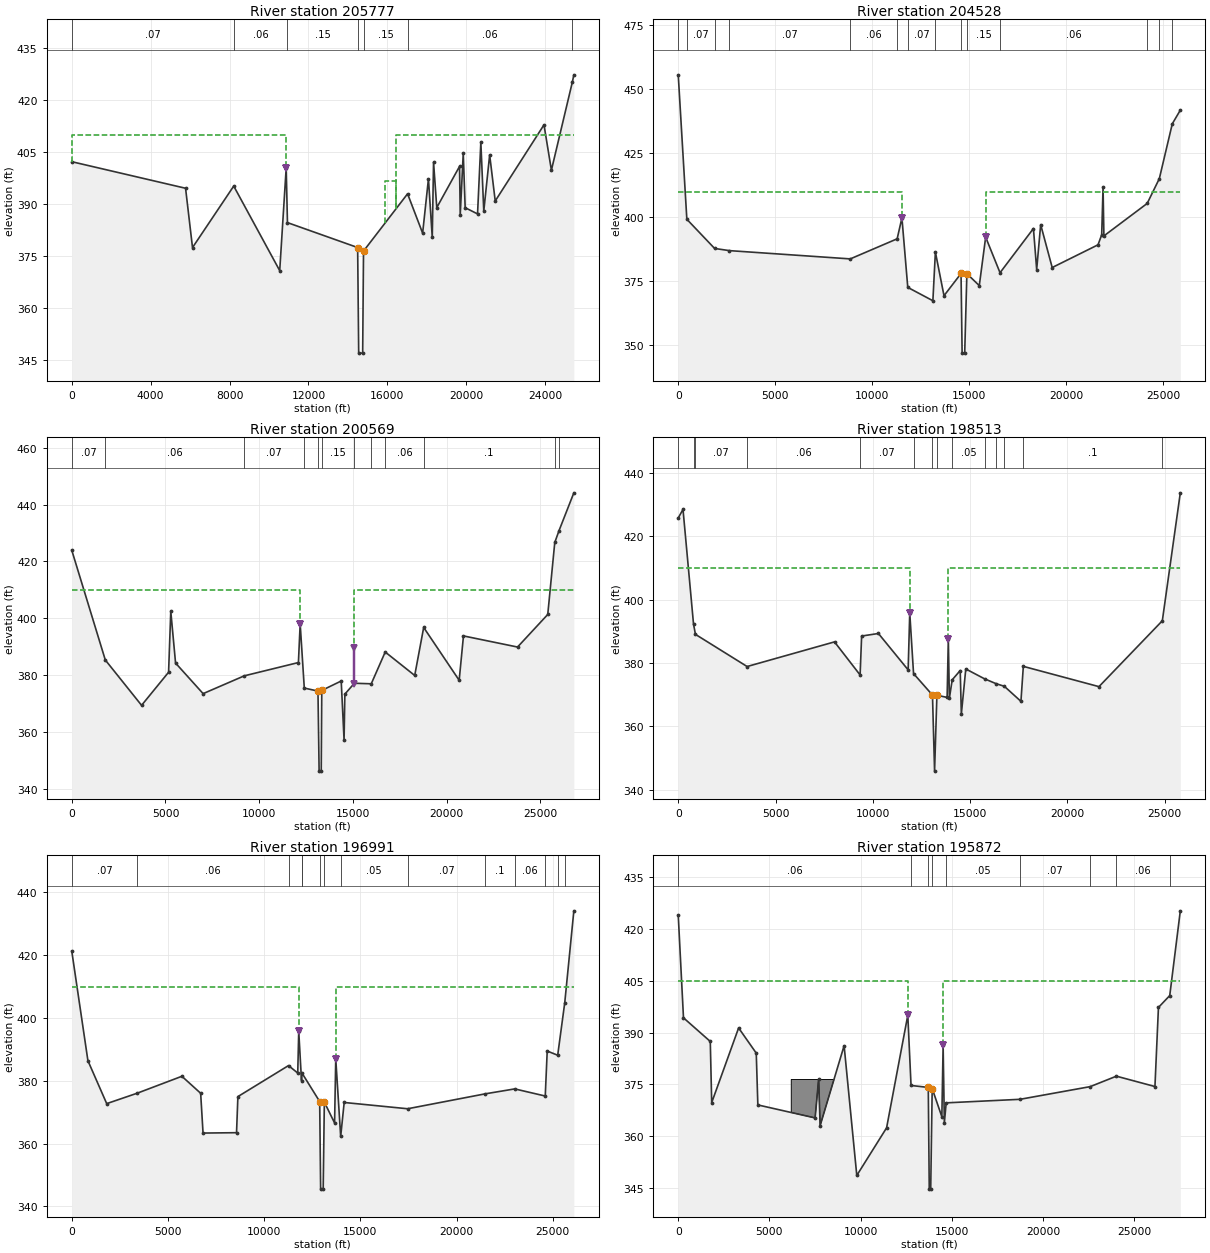
Type RM Length L Ch R = 1 ,205777  ,1262.75,1248.24,1229.51
BEGIN DESCRIPTION:
LOB - Southside WWTP
ROB IFA station 16416: flow contraction due to Dallas LID1/2 levee downstream
END DESCRIPTION:
XS GIS Cut Line= 6
2540980.83019298 6933539.73664742535497.477602626924208.30611411
2533614.000070366920921.000024692533600.635923866920903.28221235
 2529903.70565376914444.53364694 2528203.05241526911525.84775851
#Sta/Elev= 30
       0  402.32 5769.27  394.66 6121.02  377.55 8210.64  395.2910542.62  370.89
10870.96  400.54 10934.7  384.7514493.46  377.5614546.29   347.114748.07   347.1
14791.42  376.5417024.34  393.0617788.14  381.7118082.62  397.3718276.12  380.47
18341.35  402.1718504.74  389.0819659.18  400.9719693.92  387.0319847.13  404.74
19944.42  389.0520572.06  387.2620739.04  407.9220887.76  388.0721186.02  404.29
21468.32  390.9923940.48  412.9624316.52  399.8725381.49  425.37 25454.1  427.38
#Mann= 7 ,-1 , 0
       0     .07       0 8210.64     .06       0 10934.7     .15       0
14493.46    .055       014791.42     .15       017024.34     .06       0
25381.49     .08       0
Levee=-1,10870.96,400.54,0,,,,
#XS Ineff= 3 ,-1
       010870.96     41015871.74   16416  396.63   16416 25454.1     410
Permanent Ineff=
       F       F       F
Bank Sta=14493.46,14791.42
XS Rating Curve= 0 ,0
Exp/Cntr=0.3,0.1

Type RM Length L Ch R = 1 ,204528  ,2887.05,3959.05,2930.12
BEGIN DESCRIPTION:
LOB - Southside WWTP, ROB - Dallas LID1/2
END DESCRIPTION:
XS GIS Cut Line= 2
2542141.897480176933195.790666072529164.466924626910799.95733273
#Sta/Elev= 30
       0  455.63  443.94  399.25 1874.77  387.86 2636.03  387.01 8868.79  383.78
 11286.5  391.6211531.94  399.8111833.59  372.66   13128  367.4513257.32  386.45
13701.35  369.4114580.29  378.0914635.11     34714768.51     34714880.75  378.02
 15520.2  373.3515849.58  392.2716589.78  378.3818311.86  395.6418478.88  379.64
18685.27  397.1519279.01  380.4121641.73  389.2821830.52  393.1621901.42  411.66
21944.71  392.7524176.62  405.4324802.88  415.12 25470.9  436.52 25884.1  441.84
#Mann= 14 ,-1 , 0
       0     .06       0  443.94     .07       0 1874.77     .06       0
 2636.03     .07       0 8868.79     .06       0 11286.5     .07       0
11833.59     .07       013257.32     .15       014580.29    .055       0
14880.75     .15       016589.78     .06       024176.62      .1       0
24802.88     .08       0 25470.9     .06       0
Levee=-1,11531.94,399.81,-1,15849.58,392.27,,
#XS Ineff= 2 ,-1
       011531.94     41015849.58 25884.1     410
Permanent Ineff=
       F       F
Bank Sta=14580.29,14880.75
XS Rating Curve= 0 ,0
Exp/Cntr=0.3,0.1

Type RM Length L Ch R = 1 ,200569  ,2068.54,2056.32,2002.94
BEGIN DESCRIPTION:
LOB - Southside WWTP, ROB - Dallas LID1/2
END DESCRIPTION:
XS GIS Cut Line= 2
2544594.042023046931842.514654862531312.792023046908578.62576596
#Sta/Elev= 30
       0  423.94 1788.99  385.37 3724.12  369.43 5165.31  381.06  5282.7  402.49
 5537.92  384.29 7008.09  373.54 9204.36   379.8 12092.6  384.4712186.52  398.09
12405.92   375.513135.77  374.4413197.04   346.313309.94   346.313339.14  374.67
14376.03  377.98 14528.7  357.2114570.62  373.3715078.25  377.1915978.95     377
16723.98  388.1718297.74  379.9318776.03   396.820669.98  378.2320898.87  393.83
23784.09  389.9225396.01  401.3725770.55  426.6825998.04  430.8526788.13  444.13
#Mann= 12 ,-1 , 0
       0     .07       0 1788.99     .06       0 9204.36     .07       0
12405.92     .15       013135.77    .055       013339.14     .15       0
15078.25     .05       015978.95     .15       016723.98     .06       0
18776.03      .1       025770.55     .06       025998.04      .1       0
Levee=-1,12186.52,398.09,-1,15042.98,389.42,,
#XS Ineff= 2 , 0
       012186.52     41015042.98       0     410
Permanent Ineff=
       F       F
Bank Sta=13135.77,13339.14
XS Rating Curve= 0 ,0
Exp/Cntr=0.3,0.1

Type RM Length L Ch R = 1 ,198513  ,1460.65,1522.21,1546.82
BEGIN DESCRIPTION:
LOB - Southside WWTP, ROB - Dallas LID1/2
END DESCRIPTION:
XS GIS Cut Line= 2
2546593.000356376930554.320210412533259.667023046908470.98687708
#Sta/Elev= 30
       0  425.75  245.08  428.46  785.82  392.24  884.58  389.01 3538.59  378.86
  8028.9  386.64 9344.62  376.19 9422.44  388.4810284.69  389.2911812.69   377.8
11895.24  395.8312090.23  376.6313062.88  369.8413170.69  345.8413290.24  369.79
13815.75  369.1113876.77  387.6313931.21  368.8614077.49  374.6714487.86   377.6
14545.98  363.8614774.24  378.0915737.73  374.9816333.56  373.4416753.99  372.62
17607.92  367.8717730.47  378.9121616.22  372.5124872.14   393.325796.39  433.69
#Mann= 14 ,-1 , 0
       0     .07       0  785.82     .06       0  884.58     .07       0
 3538.59     .06       0 9344.62     .07       012090.23     .15       0
13062.88    .055       013290.24     .15       014077.49     .05       0
15737.73     .15       016333.56     .05       016753.99      .1       0
17730.47      .1       024872.14     .06       0
Levee=-1,11895.24,395.83,-1,13876.77,387.63,,
#XS Ineff= 2 , 0
       011895.24     41013876.77       0     410
Permanent Ineff=
       F       F
Bank Sta=13062.88,13290.24
XS Rating Curve= 0 ,0
Exp/Cntr=0.3,0.1

Type RM Length L Ch R = 1 ,196991  ,1114.91,1119.14,1044.18
BEGIN DESCRIPTION:
LOB - Southside WWTP, ROB - Dallas LID1/2
END DESCRIPTION:
XS GIS Cut Line= 4
2547677.578059796929952.10407455 2541957.4391709 6920324.0658801
2540764.383615346917785.437407882533997.022504236907764.60407454
#Sta/Elev= 30
       0  421.27  839.66  386.38 1815.93  372.72 3409.48  376.06 5723.11  381.43
 6699.35  376.02 6823.04  363.35 8563.77  363.47  8634.5  374.9611265.75  384.84
11744.94  382.4611797.07   395.811940.64  380.0711963.21  382.48 12885.5  373.39
12935.15   345.513068.07   345.513127.74   373.213659.69  366.5713720.65  387.01
13977.28  362.2714158.97  373.0917457.43  371.09 21480.1  375.8323024.23  377.41
24609.89  375.1424711.78  389.4725256.73  388.1325623.98  404.8926096.06  434.11
#Mann= 14 ,-1 , 0
       0     .07       0 3409.48     .06       011265.75     .07       0
11940.64     .06       011963.21     .15       0 12885.5    .055       0
13127.74     .15       013977.28     .05       017457.43     .07       0
 21480.1      .1       023024.23     .06       024609.89      .1       0
25256.73     .06       025623.98     .08       0
Levee=-1,11797.07,395.8,-1,13720.65,387.01,,
#XS Ineff= 2 , 0
       011797.07     41013720.65       0     410
Permanent Ineff=
       F       F
Bank Sta=12885.5,13127.74
XS Rating Curve= 0 ,0
Exp/Cntr=0.3,0.1

Type RM Length L Ch R = 1 ,195872  ,1736.76,1726.95,2123
BEGIN DESCRIPTION:
LOB - Southside WWTP, ROB - Dallas LID1/2
END DESCRIPTION:
XS GIS Cut Line= 4
2550259.667023046929359.875765962543024.453059796920010.14805602
2541811.258615346917361.536944912534173.275757926907095.38516339
#Sta/Elev= 30
       0  423.88  287.75  394.24 1757.09  387.42    1835  369.77 3310.85  391.32
 4278.01  384.05 4365.39   369.1 7505.83  365.35 7698.96  376.54    7781  363.13
 9095.51  386.19 9791.23  348.7511425.27  362.49   12588  394.9912765.73  374.72
13710.48  374.1513764.86   344.813843.92   344.813925.96  373.8214455.32  365.69
14525.15  386.3414592.48  363.9514693.44   369.718740.62  370.7222588.93  374.38
24027.44   377.426140.25  374.4126332.27  397.2426951.71  400.66 27531.3  425.12
#Mann= 9 ,-1 , 0
       0     .06       012765.73     .15       013710.48    .055       0
13925.96     .15       014693.44     .05       018740.62     .07       0
22588.93      .1       024027.44     .06       026951.71     .08       0
Levee=-1,12588,394.99,-1,14525.15,386.34,,
#XS Ineff= 2 , 0
       0   12588     40514525.15       0     405
Permanent Ineff=
       F       F
#Block Obstruct= 1 ,-1
 6197.83 8582.22  376.44
Bank Sta=13710.48,13925.96
XS Rating Curve= 0 ,0
Exp/Cntr=0.3,0.1

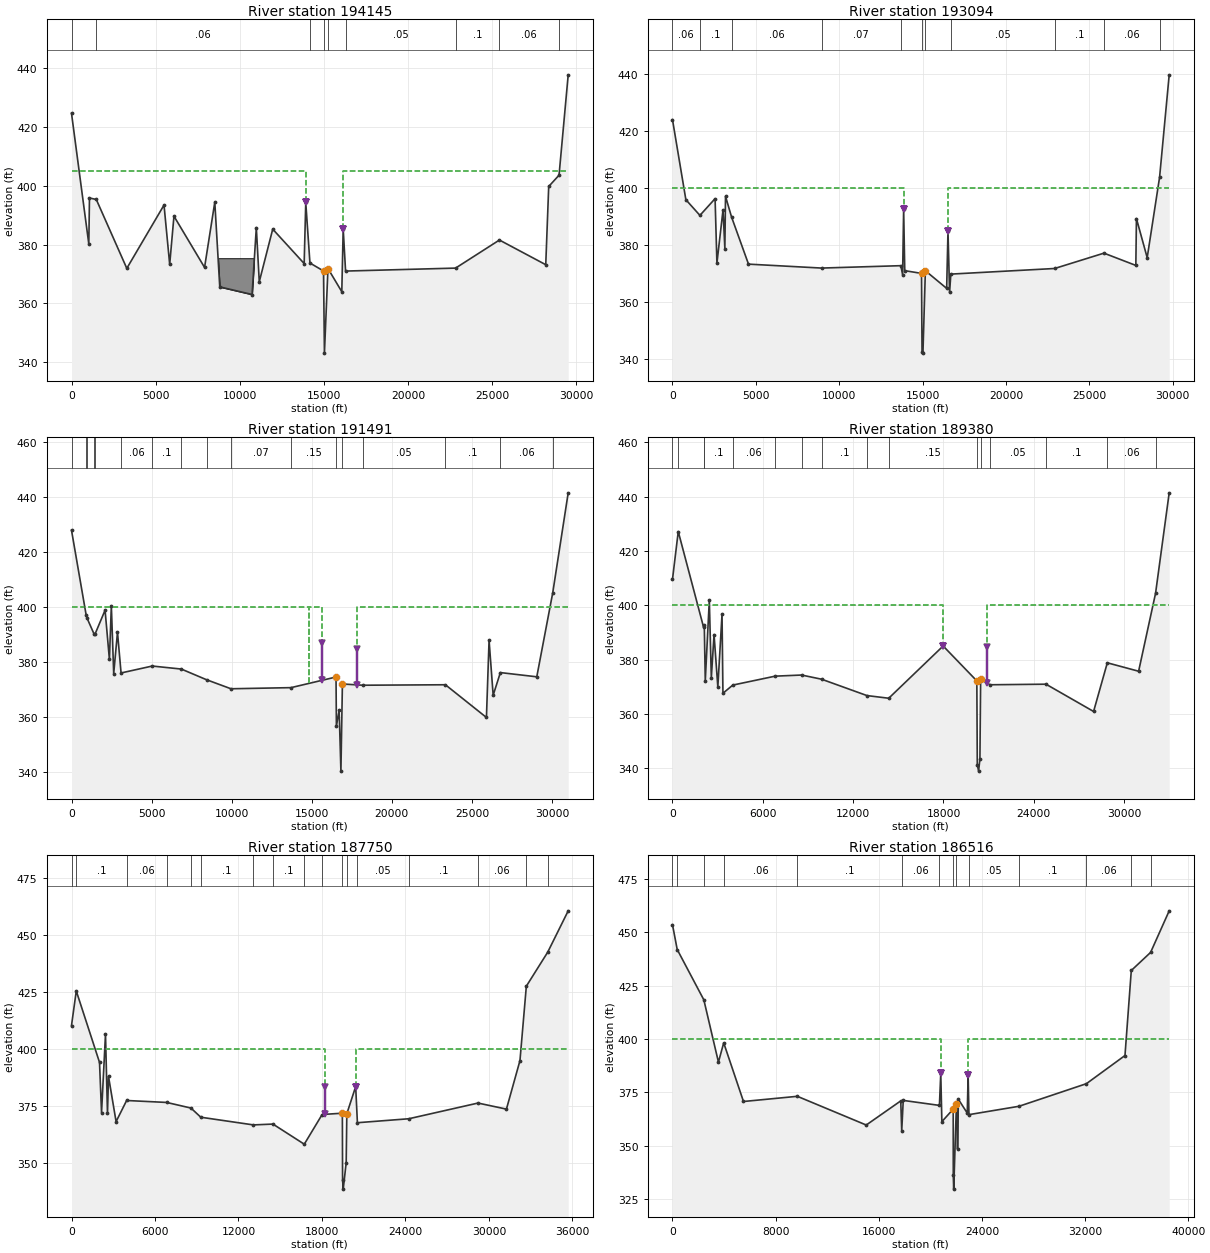
Type RM Length L Ch R = 1 ,194145  ,1483.79,1050.49,556.86
BEGIN DESCRIPTION:
LOB - Southside WWTP, ROB - Dallas LID1/2
END DESCRIPTION:
XS GIS Cut Line= 5
2552414.114273316929855.474110522544790.00861534 6919633.0184264
2543243.394032016916393.348287512539391.885627386911180.48068715
2534234.039646816906904.41294117
#Sta/Elev= 30
       0  424.67 1028.49  380.19 1068.58  395.85 1474.56  395.33 3287.19  371.88
 5499.11  393.44 5836.23  373.24 6089.75  389.65 7909.14   372.2 8517.13  394.42
 8812.55  365.5710733.65  362.9810985.54  385.7711161.06  367.3211960.74  385.24
13829.32  373.5213923.92  394.3114172.83   373.714979.29     37115034.01  343.02
 15243.9  371.8316066.48  363.9316149.17  385.3316290.69  370.9622830.01  371.97
 25434.8  381.53 28189.1  373.1328364.93  399.7628979.39  403.6129523.59  437.78
#Mann= 9 ,-1 , 0
       0     .07       0 1474.56     .06       014172.83     .15       0
14979.29    .055       0 15243.9     .15       016290.69     .05       0
22830.01      .1       0 25434.8     .06       028979.39     .08       0
Levee=-1,13923.92,394.31,-1,16149.17,385.33,,
#XS Ineff= 2 ,-1
       013923.92     40516149.1729523.59     405
Permanent Ineff=
       F       F
#Block Obstruct= 1 ,-1
 8647.3510836.41  375.33
Bank Sta=14979.29,15243.9
XS Rating Curve= 0 ,0
Exp/Cntr=0.3,0.1

Type RM Length L Ch R = 1 ,193094  ,1345.47,1602.93,571.88
BEGIN DESCRIPTION:
LOB - Bois D'Arc, ROB - Dallas LID1/2
END DESCRIPTION:
XS GIS Cut Line= 6
2554287.822272766928551.859861582547075.160235726919489.91541714
2544537.150976466916846.084398622543603.168337566916029.93509307
2539605.679296536910746.672576352534260.081313476906748.16294117
#Sta/Elev= 30
       0  423.87  802.13  395.77 1644.45  390.26 2553.75  396.14  2664.1  373.49
 3030.79  392.22 3140.18  378.62 3179.36  396.96 3542.33  389.68  4557.8  373.14
 8938.06  371.7613693.36   372.613800.43  369.4313862.06  392.4913928.82  370.85
14934.28  369.8914965.13  342.1215019.17  341.8915165.17  370.8216441.82  364.63
16521.31  384.7516617.88  363.1916691.96  369.6422916.42  371.6125874.64     377
27787.39  372.6927822.69  389.1528468.09  375.4129211.55  403.6529787.92  439.62
#Mann= 11 ,-1 , 0
       0     .06       0 1644.45      .1       0 3542.33     .06       0
 8938.06     .07       013693.36     .15       014934.28    .055       0
15165.17     .15       016691.96     .05       022916.42      .1       0
25874.64     .06       029211.55     .08       0
Levee=-1,13862.06,392.49,-1,16521.31,384.75,,
#XS Ineff= 2 ,-1
       013862.06     40016521.3129787.92     400
Permanent Ineff=
       F       F
Bank Sta=14934.28,15165.17
XS Rating Curve= 0 ,0
Exp/Cntr=0.3,0.1

Type RM Length L Ch R = 1 ,191491  ,988.29,2111.36,567.8
BEGIN DESCRIPTION:
LOB - Bois D'Arc, ROB - Dallas LID1/2
END DESCRIPTION:
XS GIS Cut Line= 5
2555578.266717196928321.341343082545553.422500736916302.54581884
2543740.689258426915107.066156172539778.685944756910550.30158257
 2534060.42853576906262.05183006
#Sta/Elev= 30
       0  427.89   914.4  397.07     958  396.09 1394.34  390.33 1462.77  390.03
 2095.76  398.81 2366.84  380.92 2487.11  400.45 2634.68  375.75  2870.8   390.8
 3094.27  375.98 5041.25   378.5 6856.41   377.4 8429.85  373.52 9956.04  370.23
13701.74  370.6416513.88  374.5116536.92  356.6116709.25  362.4516819.04  340.27
16912.14  371.9718190.28  371.5223342.01  371.6925903.58  359.7926067.98  387.88
26323.71  367.8826773.42  376.1229046.65  374.58 30044.5  405.21 31008.1  441.51
#Mann= 17 ,-1 , 0
       0     .08       0   914.4     .06       0     958     .08       0
 1394.34     .06       0 1462.77      .1       0 3094.27     .06       0
 5041.25      .1       0 6856.41     .06       0 8429.85      .1       0
 9956.04     .07       013701.74     .15       016513.88    .055       0
16912.14     .15       018190.28     .05       023342.01      .1       0
26773.42     .06       0 30044.5     .08       0
Levee=-1,15621.35,387.06,-1,17812.09,384.81,,
#XS Ineff= 3 ,-1
       0 14856.5     400 14856.515621.35     40017812.09 31008.1     400
Permanent Ineff=
       F       F       F
Bank Sta=16513.88,16912.14
XS Rating Curve= 0 ,0
Exp/Cntr=0.3,0.1

Type RM Length L Ch R = 1 ,189380  ,205.4,1630.38,1758.4
BEGIN DESCRIPTION:
LOB - Bois D'Arc, ROB - Dallas LID1/2
END DESCRIPTION:
XS GIS Cut Line= 6
  2557557.278625 6928809.5192494 2546769.9681061 6916304.8598616
  2544756.513245 6913938.4536116 2543350.9576894 6913718.6098616
 2539995.6050314 6910162.3039914 2534109.9081669 6906263.9017463
#Sta/Elev= 30
       0  409.66  382.37  427.22 2066.09  391.96 2111.19  392.75 2177.07  372.26
 2445.48  401.93 2579.32  373.42 2759.69   389.3 3011.42  370.03 3290.06  396.77
 3350.78  367.69 4004.94   370.7 6821.75  373.99 8574.54   374.4 9904.93  372.86
12916.52  366.8414364.36  365.8617978.65  385.0920215.37  372.2420245.75  341.42
20332.55  339.0320420.69  343.5120468.97   372.921083.89  370.8224809.52  371.03
27970.71  360.9928882.99   378.9   30962   375.832088.22  404.51 32993.3  441.47
#Mann= 16 ,-1 , 0
       0     .07       0  382.37      .1       0 2066.09     .08       0
 2111.19      .1       0 4004.94     .06       0 6821.75      .1       0
 8574.54     .06       0 9904.93      .1       012916.52     .07       0
14364.36     .15       020215.37    .055       020468.97     .15       0
21083.89     .05       024809.52      .1       028882.99     .06       0
32088.22     .08       0
Levee=-1,17978.65,385.09,-1,20921.35,384.68,,
#XS Ineff= 2 ,-1
       017978.65     40020921.35 32993.3     400
Permanent Ineff=
       F       F
Bank Sta=20215.37,20468.97
XS Rating Curve= 0 ,0
Exp/Cntr=0.3,0.1

Type RM Length L Ch R = 1 ,187750  ,1654.61,1233.35,710.34
BEGIN DESCRIPTION:
LOB - Bois D'Arc, ROB - Dallas LID1/2
END DESCRIPTION:
XS GIS Cut Line= 5
2557577.386206416928797.378293492547009.279724936916245.27181201
2544761.617613766912088.929152132540023.244450286909687.41087415
2532045.813894736904999.91087415
#Sta/Elev= 30
       0  410.26  342.82  425.39 2013.52  394.14 2158.93  372.18 2443.22  406.42
 2586.02  371.87 2660.15  387.99    3205  368.22  3962.1  377.46 6839.49  376.61
 8585.85  374.15  9293.2  370.1413071.24  366.7814477.86  367.14 16729.9  358.34
18015.08  371.3319466.71   371.919483.08  342.7219528.79  338.6819742.26  350.26
19786.89  371.6320423.79  383.5520548.26  367.7424238.57  369.4729214.57  376.34
31259.22  373.6932231.63  394.9232689.61  427.4734227.79  442.3835698.68  460.45
#Mann= 17 ,-1 , 0
       0     .07       0  342.82      .1       0  3962.1     .06       0
 6839.49      .1       0 8585.85     .06       0  9293.2      .1       0
13071.24     .07       014477.86      .1       0 16729.9     .06       0
18015.08     .15       019466.71    .055       019786.89     .15       0
20548.26     .05       024238.57      .1       029214.57     .06       0
32689.61     .08       034227.79     .06       0
Levee=-1,18193.79,383.19,-1,20423.79,383.55,,
#XS Ineff= 2 ,-1
       018193.79     40020423.7935698.68     400
Permanent Ineff=
       F       F
Bank Sta=19466.71,19786.89
XS Rating Curve= 0 ,0
Exp/Cntr=0.5,0.3

Type RM Length L Ch R = 1 ,186516  ,201.27,252.24,272.65
BEGIN DESCRIPTION:
US Bridge
LOB - Bois D'Arc, ROB - Dallas LID1/2
END DESCRIPTION:
XS GIS Cut Line= 6
2559712.908234356930276.007165022549247.630456586916657.95160946
2549126.428199636915812.501667332548110.369171856914455.29680621
2545486.671255186911894.532917332532205.312748246904802.37435251
#Sta/Elev= 30
       0  453.62  365.68  442.01 2431.77   418.4 3564.01  389.22 3972.03  398.26
 5505.96  370.77 9682.73   373.215027.22  359.7417703.92  371.05 17779.5  357.05
17897.26  371.2820703.97  368.9420807.66  383.9220893.23  361.3121773.35  367.22
21778.85 336.09421812.34 329.69622024.35  369.6822072.81  370.4222108.38  348.51
22174.81  371.7922863.36  365.3422930.59  383.1422993.09  364.61   26878  368.53
32104.46  379.1235096.33  392.3235586.17  432.1837082.52  440.6438526.05  460.14
#Mann= 14 ,-1 , 0
       0     .08       0  365.68     .07       0 2431.77      .1       0
 3972.03     .06       0 9682.73      .1       0 17779.5     .06       0
20703.97     .15       021773.35    .055       022024.35     .15       0
22993.09     .05       0   26878      .1       032104.46     .06       0
35586.17     .08       037082.52     .06       0
Levee=-1,20807.66,383.92,-1,22930.59,383.14,,
#XS Ineff= 2 ,-1
       020807.66     40022930.5938526.05     400
Permanent Ineff=
       F       F
Bank Sta=21773.35,22024.35
XS Rating Curve= 0 ,0
Exp/Cntr=0.5,0.3