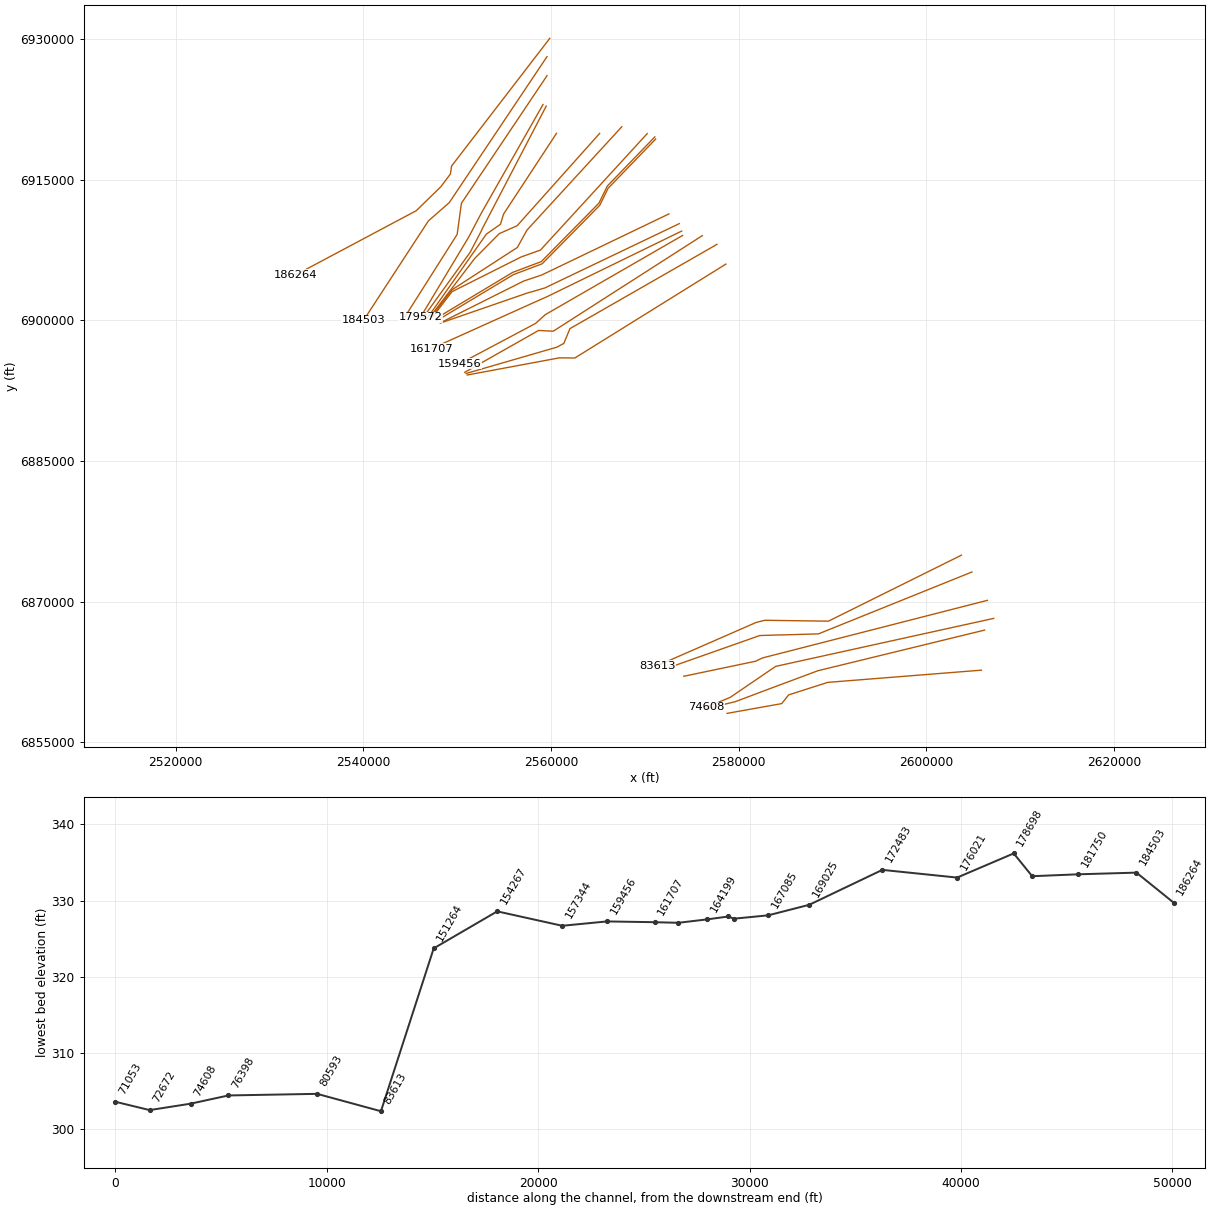
HEC-RAS study TR_FEMA.prj: Trinity_River_FEMA

--- TR_FEMA.g05 (geometry) --- (continued)

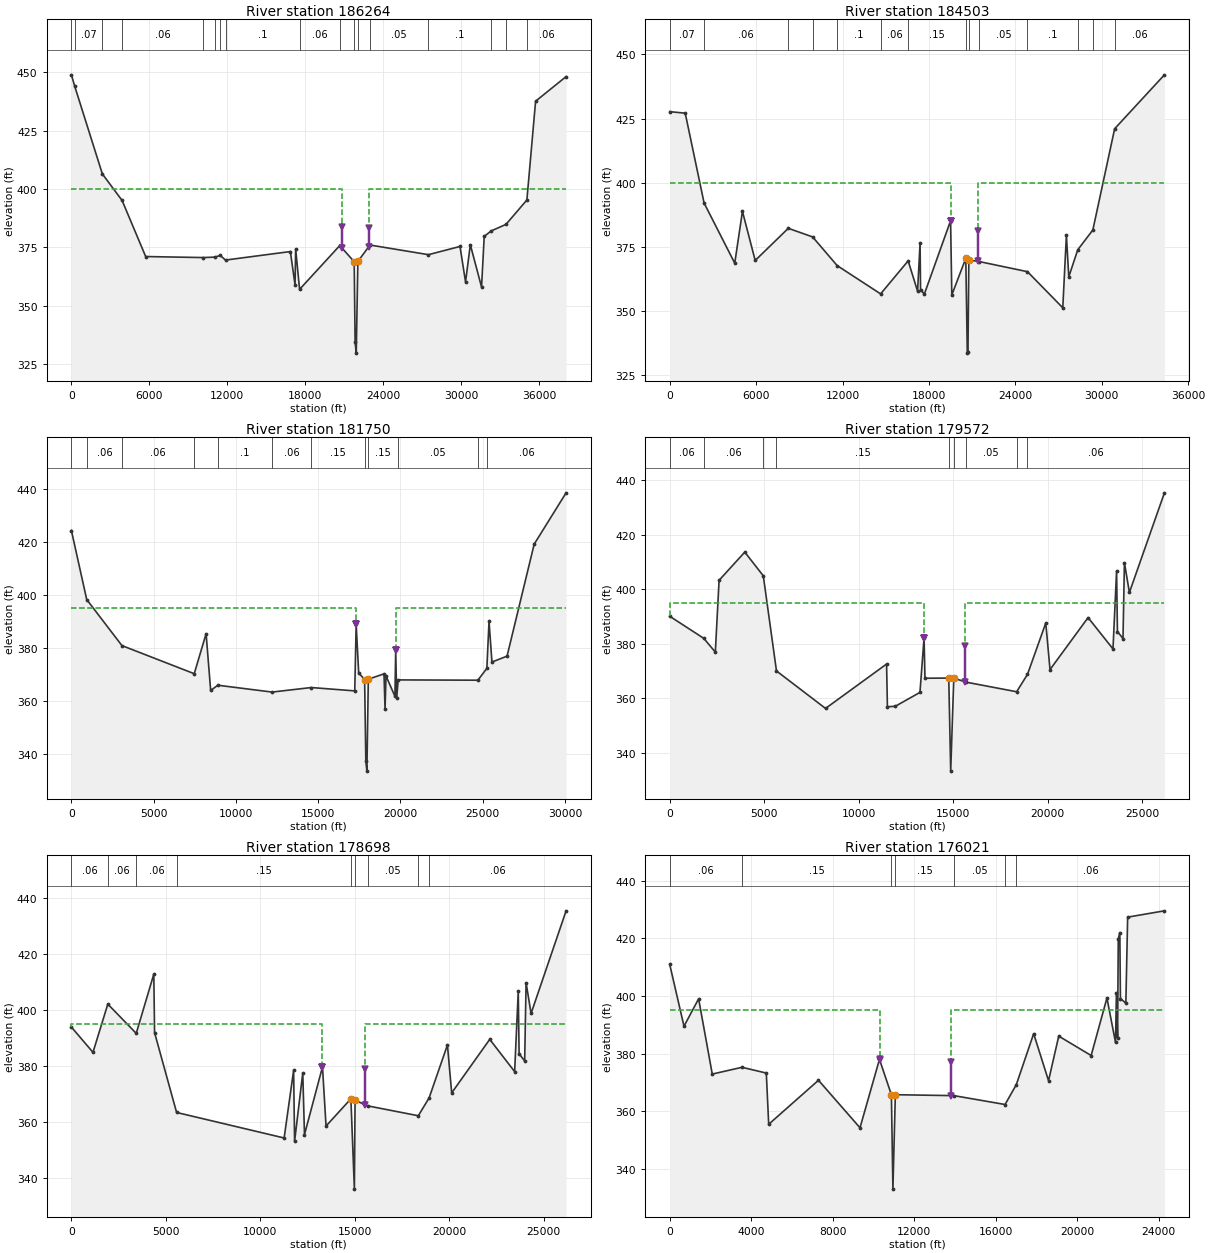
Type RM Length L Ch R = 1 ,186264  ,1855.44,1760.58,2233.35
BEGIN DESCRIPTION:
DS Bridge
LOB - Bois D'Arc, ROB - Dallas LID1/2
END DESCRIPTION:
XS GIS Cut Line= 6
2559871.226754126930085.983048982549405.948976346916467.92749342
2549284.746719396915622.477551292548268.687691616914265.27269018
2545644.989774956911704.508801292532761.29377277 6904841.7347546
#Sta/Elev= 30
       0  448.92  256.68     444 2382.59  406.47 3900.85  395.11  5715.6  371.09
10141.44  370.6511031.58  370.8411457.67  371.5511859.16  369.5816849.34  373.23
17208.86  358.9817256.36  374.3717558.05  357.03 20653.4   375.821761.57  368.87
21831.52 334.34321919.58  329.7222043.92  368.9822975.62  376.0227475.03  371.89
29902.81  375.4130329.89  360.2330698.82  376.1531561.26  358.0231766.54  379.73
32307.07  382.0733443.98  384.8735049.96  395.3135720.62  437.6238066.94  448.16
#Mann= 17 ,-1 , 0
       0     .08       0  256.68     .07       0 2382.59      .1       0
 3900.85     .06       010141.44      .1       011031.58     .06       0
11457.67     .06       011859.16      .1       017558.05     .06       0
 20653.4     .15       021761.57    .055       022043.92     .15       0
22975.62     .05       027475.03      .1       032307.07     .06       0
33443.98     .05       035049.96     .06       0
Levee=-1,20792.77,383.68,-1,22865.83,383.32,,
#XS Ineff= 2 ,-1
       020792.77     40022865.8338066.94     400
Permanent Ineff=
       F       F
Bank Sta=21761.57,22043.92
XS Rating Curve= 0 ,0
Exp/Cntr=0.5,0.3

Type RM Length L Ch R = 1 ,184503  ,1141.76,2752.93,3502.22
BEGIN DESCRIPTION:
LOB - Bois D'Arc, ROB - Dallas LID1/2
END DESCRIPTION:
XS GIS Cut Line= 4
2559572.852699236928131.371101242549158.807805166912562.74643566
2546939.363360716910618.301991212540024.241588126900006.37110124
#Sta/Elev= 30
       0  427.72 1075.28  427.13 2384.82  392.14 4513.55   368.7 5048.05  388.89
 5933.32  369.75 8231.53  382.28 9920.58  378.9311625.88  367.7514641.38  356.74
16553.76   369.617207.45   357.8 17381.7  376.6117415.02  358.4217676.22  356.63
19500.41  385.2519585.37  356.3320555.35  370.5920659.95  333.6620707.16  334.17
20767.44  369.9621487.21  369.3324838.63  365.3927289.81  351.3227541.37  379.56
27706.21  363.3828329.32  373.9129377.92  381.64 30890.8  421.0634347.37  442.07
#Mann= 14 ,-1 , 0
       0     .07       0 2384.82     .06       0 8231.53     .06       0
 9920.58     .06       011625.88      .1       014641.38     .06       0
16553.76     .15       020555.35    .055       020767.44     .15       0
21487.21     .05       024838.63      .1       028329.32     .06       0
29377.92     .05       0 30890.8     .06       0
Levee=-1,19500.41,385.25,-1,21379.67,381.19,,
#XS Ineff= 2 ,-1
       019500.41     40021379.6734347.37     400
Permanent Ineff=
       F       F
Bank Sta=20555.35,20767.44
XS Rating Curve= 0 ,0
Exp/Cntr=0.3,0.1

Type RM Length L Ch R = 1 ,181750  ,2178.07,2178.36,1237.92
BEGIN DESCRIPTION:
LOB - Bois D'Arc, ROB - Dallas LID1/2
END DESCRIPTION:
XS GIS Cut Line= 4
2559575.33418071 6926100.72295312550454.46752738 6912496.2533801
2550002.664865346909181.624907882544471.167514056900441.00073088
#Sta/Elev= 30
       0  424.22  930.84  398.19 3070.86  380.81 7466.12   370.2 8187.52   385.3
 8464.59  363.87 8900.14  365.8512198.84  363.2714578.21  364.9817222.38  363.72
 17308.4  388.8417461.85  370.4717822.88  368.0117896.15  337.1317960.37  333.44
18047.38  368.1219001.08  370.1519063.98   356.819122.93  369.3519665.02  361.68
19711.52  379.2819771.51  361.0919861.27  367.8624706.16  367.7525251.92  372.21
25384.35  389.9225562.23   374.626480.27  376.8328128.73  419.0830068.09  438.45
#Mann= 12 ,-1 , 0
       0     .07       0  930.84     .06       0 3070.86     .06       0
 7466.12     .06       0 8900.14      .1       012198.84     .06       0
14578.21     .15       017822.88    .055       018047.38     .15       0
19861.27     .05       024706.16      .1       025251.92     .06       0
Levee=-1,17308.4,388.84,-1,19711.52,379.28,,
#XS Ineff= 2 ,-1
       0 17308.4     39519711.5230068.09     395
Permanent Ineff=
       F       F
Bank Sta=17822.88,18047.38
XS Rating Curve= 0 ,0
Exp/Cntr=0.3,0.1

Type RM Length L Ch R = 1 ,179572  ,766.97,874.08,934.72
BEGIN DESCRIPTION:
LOB - Bois D'Arc, ROB - Dallas LID1/2
END DESCRIPTION:
XS GIS Cut Line= 4
2559148.762421456923029.18128644 2552593.20686596911473.62573088
2551232.095754796908890.29239755 2546093.20686596900334.73684199
#Sta/Elev= 30
       0  390.02 1798.58  381.93 2413.01  376.87 2611.82  403.22  3971.5  413.57
 4951.44  404.86 5649.14  369.95 8245.78   356.211476.02  372.4911520.72  356.82
 11935.7  356.9813243.16  362.0813460.08  382.12 13508.2  367.2814767.13  367.34
14869.71  333.1915033.64  367.3215676.41  365.8518360.13  362.3218932.91  368.69
19901.66  387.5420125.82  370.4622140.59  389.5323458.89  378.0423649.71  406.69
23694.22  384.41   23989  381.8524063.88   409.724327.84  398.75 26181.2  435.32
#Mann= 9 ,-1 , 0
       0     .06       0 1798.58     .06       0 4951.44     .06       0
 5649.14     .15       014767.13    .055       015033.64     .15       0
15676.41     .05       018360.13      .1       018932.91     .06       0
Levee=-1,13460.08,382.12,-1,15617.55,378.97,,
#XS Ineff= 2 ,-1
       013460.08     39515617.55 26181.2     395
Permanent Ineff=
       F       F
Bank Sta=14767.13,15033.64
XS Rating Curve= 0 ,0
Exp/Cntr=0.3,0.1

Type RM Length L Ch R = 1 ,178698  ,1580.48,2677.02,409.08
BEGIN DESCRIPTION:
LOB - Bois D'Arc, ROB - Dallas LID1/2
END DESCRIPTION:
XS GIS Cut Line= 5
2559490.928754236922857.666574542552647.425477186909725.03967755
2552552.475919656909494.523410582551369.969250626907246.30085465
2546356.22769924  6900280.049342
#Sta/Elev= 30
       0  393.92 1141.95   384.9 1926.79  402.09 3431.82  391.67 4360.95  412.76
 4402.37  391.92 5567.51  363.4911258.94   354.411761.14   378.511812.03  353.22
12245.06  377.5412336.06   355.613289.19  379.7313476.76  358.6514791.64  368.36
 14976.7  336.1815012.84  367.8315676.41  365.8518360.13  362.3218932.91  368.69
19901.66  387.5420125.82  370.4622140.59  389.5323458.89  378.0423649.71  406.69
23694.22  384.41   23989  381.8524063.88   409.724327.84  398.75 26181.2  435.32
#Mann= 9 ,-1 , 0
       0     .06       0 1926.79     .06       0 3431.82     .06       0
 5567.51     .15       014791.64    .055       015012.84     .15       0
15676.41     .05       018360.13      .1       018932.91     .06       0
Levee=-1,13289.19,379.73,-1,15534.78,379,,
#XS Ineff= 2 ,-1
       013289.19     39515534.56 26181.2     395
Permanent Ineff=
       F       F
Bank Sta=14791.64,15012.84
XS Rating Curve= 0 ,0
Exp/Cntr=0.3,0.1

Type RM Length L Ch R = 1 ,176021  ,2531.23,3537.5,700.82
BEGIN DESCRIPTION:
LOB - Bois D'Arc, ROB - Dallas LID1/2
END DESCRIPTION:
XS GIS Cut Line= 5
2560588.416356656919955.471795722554947.803754236911347.82861158
2554613.081532016910254.773056032553119.24968998 6909210.7495735
2546787.65131034 6900195.8479531
#Sta/Elev= 30
       0   410.9   699.4  389.49 1417.12     399 2086.31   372.9 3545.85  375.25
 4738.33  373.25 4855.57  355.49 7298.32  370.75 9335.43  354.28 10291.1     378
10875.75  365.7410950.68  333.0111069.77  365.7513947.64  365.4216453.32  362.35
17004.74  369.21 17856.7  386.9118586.62   370.619087.61  386.0720677.71  379.33
21452.25  399.2821873.21  383.8621917.79  401.1421974.12  385.3622008.61  419.78
22084.37  421.9722114.88  399.0922380.36   397.522468.47  427.3124273.08   429.5
#Mann= 7 ,-1 , 0
       0     .06       0 3545.85     .15       010875.75    .055       0
11069.77     .15       013947.64     .05       016453.32      .1       0
17004.74     .06       0
Levee=-1,10296.09,378,-1,13805.69,376.97,,
#XS Ineff= 2 ,-1
       010296.09     39513805.6924273.08     395
Permanent Ineff=
       F       F
Bank Sta=10875.75,11069.77
XS Rating Curve= 0 ,0
Exp/Cntr=0.3,0.1

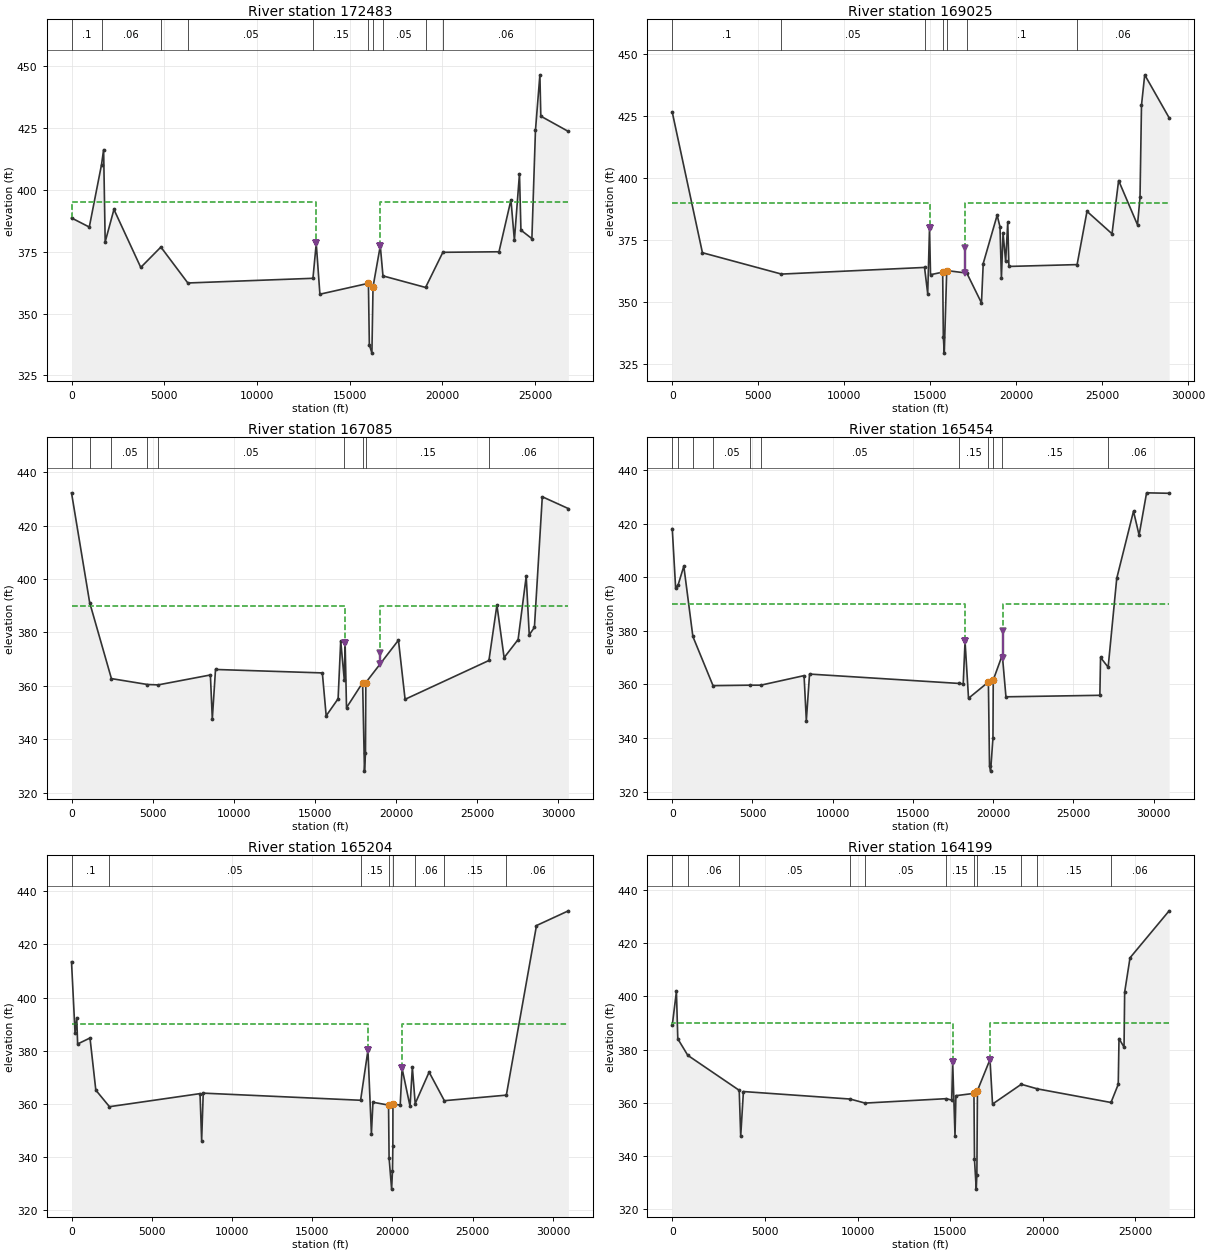
Type RM Length L Ch R = 1 ,172483  ,1181.15,3458.81,1936.55
BEGIN DESCRIPTION:
LOB - Bois D'Arc, ROB - Dallas LID1/2
END DESCRIPTION:
XS GIS Cut Line= 5
2565182.616588126919946.716008662556391.389458526910099.22201427
2554487.454273346909257.208125382551870.984643686906612.51461977
2547148.762421456900418.07017533
#Sta/Elev= 30
       0  388.58  959.04   384.9 1619.23  410.13  1731.1  416.16 1815.83  378.93
 2287.92  392.01 3734.32  368.61 4818.85  376.83 6272.44  362.33 13018.8  364.22
13195.63  378.2713393.67   357.8 16009.4   362.216059.69  337.3716197.71  334.02
16257.81  360.7516649.41  377.3216794.36  365.1919091.59  360.5320022.87  374.71
23050.08  374.9323695.19  395.8623880.43  379.5724155.03  406.4524233.05  383.67
24823.93  380.2325016.31  423.9125255.74  446.3425304.65  429.6626791.89  423.49
#Mann= 10 ,-1 , 0
       0      .1       0 1619.23     .06       0 4818.85      .1       0
 6272.44     .05       0 13018.8     .15       0 16009.4    .055       0
16257.81     .15       016794.36     .05       019091.59      .1       0
20022.87     .06       0
Levee=-1,13195.63,378.27,-1,16649.41,377.32,,
#XS Ineff= 2 ,-1
       013195.63     39516649.4126791.89     395
Permanent Ineff=
       F       F
Bank Sta=16009.4,16257.81
XS Rating Curve= 0 ,0
Exp/Cntr=0.3,0.1

Type RM Length L Ch R = 1 ,169025  ,2540.16,1939.9,813.21
BEGIN DESCRIPTION:
LOB - Bois D'Arc, ROB - Dallas LID1/2
END DESCRIPTION:
XS GIS Cut Line= 5
2567543.277467766920656.860684622557438.775976456909634.40268566
2556412.387087566907779.541574552549440.672143686903262.27156422
2547322.616588126900463.66045311
#Sta/Elev= 30
       0  426.44 1754.32  369.86 6351.27  361.2614668.24  363.9414853.24  353.36
14957.67  379.6315017.11  361.02 15723.6  362.0415760.87  336.0915816.71  329.44
 15958.5  362.68 17127.3  361.6617979.41  349.6518080.67  365.5218889.65  384.95
19055.78  380.2919138.18  359.6719233.91  377.7519385.28  366.4119506.69  382.12
19574.07  364.3423539.21  365.0824114.59  386.5125569.27  377.4925952.78  398.93
27051.51  381.0927197.13  392.1327283.32  429.2327470.32  441.4828889.98  424.18
#Mann= 7 ,-1 , 0
       0      .1       0 6351.27     .05       014668.24     .15       0
 15723.6    .055       0 15958.5     .15       0 17127.3      .1       0
23539.21     .06       0
Levee=-1,14957.67,379.63,-1,17013.93,371.76,,
#XS Ineff= 2 ,-1
       014957.67     39017013.9328889.98     390
Permanent Ineff=
       F       F
Bank Sta=15723.6,15958.5
XS Rating Curve= 0 ,0
Exp/Cntr=0.3,0.1

Type RM Length L Ch R = 1 ,167085  ,1087.43,1630.75,1236.82
BEGIN DESCRIPTION:
LOB - Bois D'Arc, ROB - Dallas LID1/2
END DESCRIPTION:
XS GIS Cut Line= 5
2570255.574362936919925.554734122558876.389719376907504.55343791
2556828.766274576906773.46139785 2549444.14436596903060.88267533
 2547409.58254826900405.39565756
#Sta/Elev= 30
       0  432.25 1118.92  391.17 2460.13   362.7 4683.68  360.49 5344.28  360.35
 8561.69  364.06 8679.91  347.56 8876.83  366.1215463.17  364.8315699.37  348.77
16434.24  355.1416595.36  376.8116816.95  362.1816867.19  375.9816952.58  351.81
17946.58  361.1718059.61  328.0618122.12  334.7618143.76  361.2220154.42  377.07
20563.17  354.9525732.03  369.4826224.28  390.22 26668.4  370.5427530.81  377.32
28030.26  400.9828217.71  379.07 28536.5  381.8929022.37  430.7830630.34  426.35
#Mann= 9 ,-1 , 0
       0     .07       0 1118.92      .1       0 2460.13     .05       0
 4683.68      .1       0 5344.28     .05       016816.95     .15       0
17946.58    .055       018143.76     .15       025732.03     .06       0
Levee=-1,16867.19,375.98,-1,19010.01,372.34,,
#XS Ineff= 2 ,-1
       016867.19     39019010.0130630.34     390
Permanent Ineff=
       F       F
Bank Sta=17946.58,18143.76
XS Rating Curve= 0 ,0
Exp/Cntr=0.5,0.3

Type RM Length L Ch R = 1 ,165454  ,224.76,250.22,261.43
BEGIN DESCRIPTION:
US Bridge
LOB - Bois D'Arc, ROB - Dallas LID1/2
END DESCRIPTION:
XS GIS Cut Line= 6
2571064.517439086919575.161277432566003.753550186914334.01544409
2565110.003550176912511.793221862558975.281327946906277.24461073
2555912.086883486905121.68905517 2547692.46882796900176.72377738
#Sta/Elev= 30
       0  418.17  211.42  395.93  370.27  397.26  720.46  404.15 1284.49  377.89
 2541.58  359.53 4832.33  359.715517.479  359.718214.539  363.28 8355.23  346.47
 8555.71  363.8617874.37  360.36 18132.3  360.19 18246.3  376.0918463.09  354.82
19701.56   360.9 19770.9 329.645 19839.7 327.61719985.68  340.0420003.09  361.65
20568.99  370.9820795.05  355.3726647.99  355.9326690.77  370.0627164.25  366.42
   27700  399.6128744.54  424.6729092.81  415.7529559.32  431.5430964.49  431.37
#Mann= 11 ,-1 , 0
       0      .1       0  370.27     .07       0 1284.49      .1       0
 2541.58     .05       0 4832.33      .1       05517.479     .05       0
17874.37     .15       019701.56    .055       020003.09     .15       0
20568.99     .15       027164.25     .06       0
Levee=-1,18246.3,376.09,-1,20585.91,380,,
#XS Ineff= 2 ,-1
       0 18246.3     39020585.9130964.49     390
Permanent Ineff=
       F       F
Bank Sta=19701.56,20003.09
XS Rating Curve= 0 ,0
Exp/Cntr=0.5,0.3

Type RM Length L Ch R = 1 ,165204  ,2833.82,1004.45,1013.94
BEGIN DESCRIPTION:
DS Bridge
LOB - Bois D'Arc, ROB - Dallas LID1/2
END DESCRIPTION:
XS GIS Cut Line= 6
2571148.471632786919340.467399712566087.707743886914099.32156637
2565193.957743886912277.099344142559059.235521646906042.55073301
2555996.041077196904886.995177452547776.423021616899942.02989966
#Sta/Elev= 30
       0  413.48  221.23  386.66  325.28  392.45  381.49  382.53 1152.41  384.78
 1514.88  365.17 2364.41  358.93 8009.12  363.85 8110.32  346.16 8208.18  364.03
18015.71  361.3518473.14  380.1618689.36  348.7918785.87   360.619757.48  359.53
19790.41   339.7 19948.8 327.90720003.44 334.86320025.39  344.1720031.36  359.91
20484.38  359.5520599.72  373.3721096.56  359.0721240.92  373.6921417.91   360.1
   22285  371.9423235.21  361.1927098.06  363.2828976.79   427.1 30964.4  432.64
#Mann= 8 ,-1 , 0
       0      .1       0 2364.41     .05       018015.71     .15       0
19757.48    .055       020031.36     .15       021417.91     .06       0
23235.21     .15       027098.06     .06       0
Levee=-1,18473.14,380.16,-1,20599.72,373.37,,
#XS Ineff= 2 ,-1
       018473.14     39020599.72 30964.4     390
Permanent Ineff=
       F       F
Bank Sta=19757.48,20031.36
XS Rating Curve= 0 ,0
Exp/Cntr=0.5,0.3

Type RM Length L Ch R = 1 ,164199  ,1428.2,1367.21,1058.58
BEGIN DESCRIPTION:
LOB - Bois D'Arc, ROB - Dallas LID1/2
END DESCRIPTION:
XS GIS Cut Line= 4
2572565.59443196 6911360.62073692559008.077070836904842.65198688
2557098.354848616904203.763097992548372.084459926899827.39656934
#Sta/Elev= 30
       0  389.12  224.44  401.91   299.2  384.07  838.45  377.86 3614.19   364.7
 3694.54   347.4 3840.79  364.24 9599.25  361.4210407.14   359.914797.07  361.56
15084.37     36115135.94  375.3115261.81  347.5815310.66  362.6816284.31  363.55
16312.96  338.6816407.93  327.5316441.75  332.9916473.03  364.6117150.04  376.29
17287.03  359.5318838.98  366.9719705.71  365.2523681.46  360.1224072.29  366.94
24113.22  384.1624385.24  380.9324418.55  401.6124708.18  414.55 26818.9  432.22
#Mann= 11 ,-1 , 0
       0     .07       0  838.45     .06       0 3614.19     .05       0
 9599.25      .1       010407.14     .05       014797.07     .15       0
16284.31    .055       016473.03     .15       018838.98     .06       0
19705.71     .15       023681.46     .06       0
Levee=-1,15135.94,375.31,-1,17150.04,376.29,,
#XS Ineff= 2 ,-1
       015135.94     39017150.04 26818.9     390
Permanent Ineff=
       F       F
Bank Sta=16284.31,16473.03
XS Rating Curve= 0 ,0
Exp/Cntr=0.3,0.1

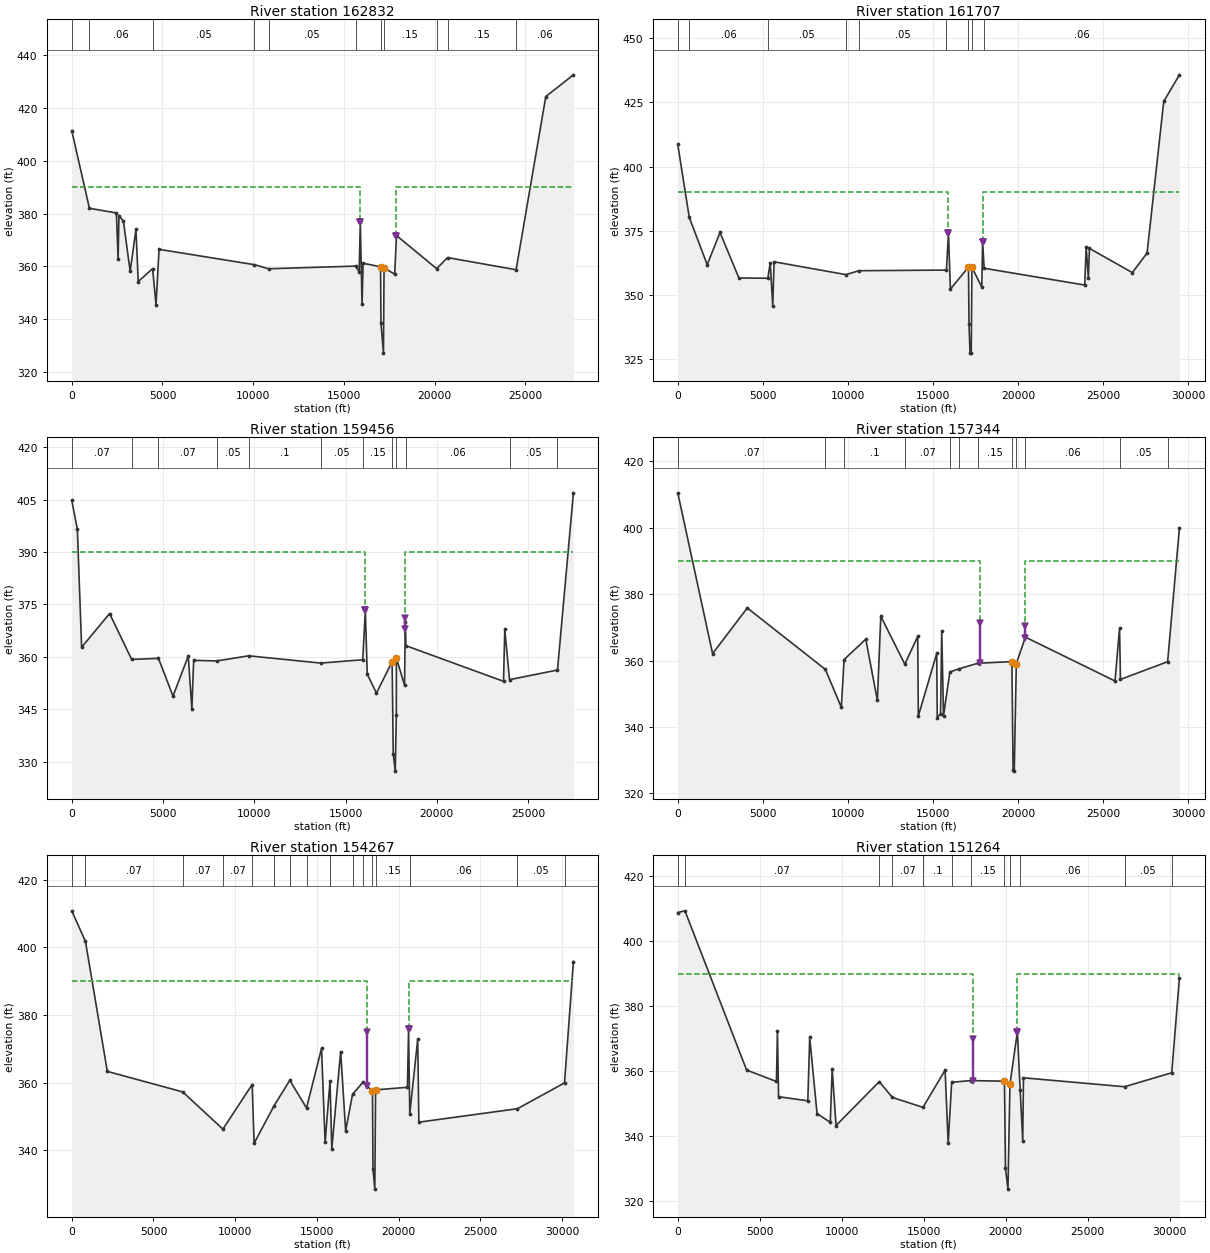
Type RM Length L Ch R = 1 ,162832  ,930.2,1125.12,1407.97
BEGIN DESCRIPTION:
LOB - Bois D'Arc, ROB - Dallas LID1/2
END DESCRIPTION:
XS GIS Cut Line= 4
2573672.057226476910324.489491232559342.144032026903463.29157455
2557416.102365356902900.791574552548203.307226456899716.85060233
#Sta/Elev= 30
       0  411.45  972.85  382.03 2460.75  380.24 2553.94  362.85 2600.63  379.25
 2848.45  377.07 3218.18  358.12 3539.16   374.1 3661.86  354.22 4454.66  359.13
 4643.12  345.45 4809.96  366.4510064.97  360.6210841.67  359.0815640.54  360.09
 15836.7  357.9115899.03  376.7915994.62  345.6716055.16  361.1517016.16  359.83
17037.44  338.4917175.73  327.0817207.69  359.4217793.92  357.0317892.38  371.69
20104.77  359.1220707.46  363.3224483.67   358.726120.06   424.427641.74  432.64
#Mann= 11 ,-1 , 0
       0     .07       0  972.85     .06       0 4454.66     .05       0
10064.97      .1       010841.67     .05       015640.54     .15       0
17016.16    .055       017207.69     .15       020104.77     .06       0
20707.46     .15       024483.67     .06       0
Levee=-1,15899.03,376.79,-1,17892.38,371.69,,
#XS Ineff= 2 ,-1
       015899.03     39017892.3827641.74     390
Permanent Ineff=
       F       F
Bank Sta=17016.16,17207.69
XS Rating Curve= 0 ,0
Exp/Cntr=0.3,0.1

Type RM Length L Ch R = 1 ,161707  ,1287.44,2251.17,2226.65
BEGIN DESCRIPTION:
LOB - Bois D'Arc, ROB - Dallas LID1/2
END DESCRIPTION:
XS GIS Cut Line= 4
 2573919.27944876909528.308935682559622.057226476902553.30893567
2557775.182226466901729.35060234 2547235.25167096896976.22560234
#Sta/Elev= 30
       0  408.66  673.33  380.22 1730.72  361.68 2484.87  374.25 3593.53   356.5
  5294.1  356.39 5435.28  362.36 5583.78  345.73 5662.01  362.81 9889.96   357.8
10646.13  359.3315796.61  359.5815913.21  374.1116027.77  352.1317091.24  360.75
17121.09  338.5217183.35  327.1617253.35  327.1617293.04  360.6817871.87  352.93
17921.79  370.6318010.71  360.2923925.79  353.7324009.32  368.6724137.73  356.47
24200.98  368.0426724.05  358.5927590.31  366.2428570.23  425.41 29492.4  435.79
#Mann= 9 ,-1 , 0
       0     .07       0  673.33     .06       0  5294.1     .05       0
 9889.96      .1       010646.13     .05       015796.61     .15       0
17091.24    .055       017293.04     .15       018010.71     .06       0
Levee=-1,15913.21,374.11,-1,17921.79,370.63,,
#XS Ineff= 2 ,-1
       015913.21     39017921.79 29492.4     390
Permanent Ineff=
       F       F
Bank Sta=17091.24,17293.04
XS Rating Curve= 0 ,0
Exp/Cntr=0.3,0.1

Type RM Length L Ch R = 1 ,159456  ,1796.97,2111.7,856.13
BEGIN DESCRIPTION:
LOB - Bois D'Arc, ROB - Dallas LID1/2
END DESCRIPTION:
XS GIS Cut Line= 4
2574022.578059816909063.899213462559391.791022766900614.24643568
2558348.966948696899676.746435672550237.855837576895365.98254678
#Sta/Elev= 30
       0  404.85   307.8  396.52  540.76  362.74 2072.69   372.4  3282.1  359.26
 4750.08  359.57  5546.9  348.75 6383.02  360.23 6580.04  345.05  6680.2  358.99
  7953.6  358.83 9688.69  360.2913642.18  358.2115942.82  359.1716083.73  373.43
16189.08  355.0216691.93  349.6317550.99  358.5817613.52  332.1917722.64  327.26
17780.74  343.2917786.32  359.6118232.31  351.8818272.77  369.9518310.25  363.19
23654.16  352.9823722.66  367.87 23983.2  353.4626610.13  356.2227483.23  406.98
#Mann= 12 ,-1 , 0
       0     .07       0  3282.1     .06       0 4750.08     .07       0
  7953.6     .05       0 9688.69      .1       013642.18     .05       0
15942.82     .15       017550.99    .055       017786.32     .15       0
18310.25     .06       0 23983.2     .05       026610.13     .06       0
Levee=-1,16083.73,373.43,-1,18283.99,371.07,,
#XS Ineff= 2 ,-1
       016083.73     39018283.9927483.23     390
Permanent Ineff=
       F       F
Bank Sta=17550.99,17786.32
XS Rating Curve= 0 ,0
Exp/Cntr=0.3,0.1

Type RM Length L Ch R = 1 ,157344  ,948.05,3077.14,2486.59
BEGIN DESCRIPTION:
LOB - Bois D'Arc, ROB - Dallas LID1/2
END DESCRIPTION:
XS GIS Cut Line= 4
2576124.256300566909043.413102352560240.402133886898849.66310234
2558682.068800546898932.996435672550808.120060356894467.16161053
#Sta/Elev= 30
       0  410.53 2046.93  362.09 4085.18  375.84 8675.15  357.34 9612.65  345.92
 9776.27   360.311051.82  366.4511732.16  347.9811932.42  373.3613343.42  358.91
14104.43  367.2614140.35  343.2815220.16  362.1415252.47  342.7815444.82  344.04
   15515   368.915619.05  343.3915994.19  356.5616544.95  357.5317624.69  359.18
19638.15  359.6919708.99  327.0119777.38  326.6919898.87  359.0920434.58  367.06
 25698.6  353.8425966.05  369.68 26020.1  354.3228793.51  359.66 29486.2  399.98
#Mann= 12 ,-1 , 0
       0     .07       0 8675.15     .07       0 9776.27      .1       0
13343.42     .07       015994.19     .05       016544.95     .07       0
17624.69     .15       019638.15    .055       019898.87     .15       0
20434.58     .06       0 26020.1     .05       028793.51     .06       0
Levee=-1,17774.12,371.28,-1,20414.93,370.51,,
#XS Ineff= 2 ,-1
       017774.15     39020414.93 29486.2     390
Permanent Ineff=
       F       F
Bank Sta=19638.15,19898.87
XS Rating Curve= 0 ,0
Exp/Cntr=0.3,0.1

Type RM Length L Ch R = 1 ,154267  ,2928.63,3003.32,1020.6
BEGIN DESCRIPTION:
LOB - Bois D'Arc, ROB - Dallas LID1/2
END DESCRIPTION:
XS GIS Cut Line= 5
2577683.119930486908112.994882482562017.311695226899122.99645831
2561369.395340146897553.204650392560632.806918296897148.53059098
2550948.498531046894340.13036789
#Sta/Elev= 30
       0   410.8  837.14  401.79 2176.36  363.36 6785.31   357.3 9245.48  346.31
11036.79  359.4911152.87  342.1312375.82  353.2213335.26  360.7214359.38  352.55
15278.67  370.1915496.36  342.3815796.75  360.5815905.35  340.5616448.28  369.19
 16753.2  345.7617172.32  356.5717799.81   360.118394.04  357.59 18423.7  334.59
18536.48  328.5818584.13  357.9120530.15  358.6620600.43  375.7620675.41  350.89
21160.32  372.8521230.31  348.3627259.18  352.3430138.64  359.9630683.54  395.82
#Mann= 16 ,-1 , 0
       0     .07       0  837.14     .07       0 6785.31     .07       0
 9245.48     .07       011036.79      .1       012375.82     .07       0
13335.26      .1       014359.38     .07       015796.75      .1       0
17172.32     .07       017799.81     .15       018394.04    .055       0
18584.13     .15       020675.41     .06       027259.18     .05       0
30138.64     .06       0
Levee=-1,18057.04,375.03,-1,20600.43,375.76,,
#XS Ineff= 2 ,-1
       018057.04     39020600.4330683.54     390
Permanent Ineff=
       F       F
Bank Sta=18394.04,18584.13
XS Rating Curve= 0 ,0
Exp/Cntr=0.3,0.1

Type RM Length L Ch R = 1 ,151264  ,621.55,2495.98,3306.68
BEGIN DESCRIPTION:
LOB - Bois D'Arc, ROB - Dallas LID1/2
END DESCRIPTION:
XS GIS Cut Line= 5
 2578634.50910386906008.828159062562540.853627156895992.51026523
2560824.186784896896009.176898552560782.641592386895987.49255873
2551073.515013316894178.02144015
#Sta/Elev= 30
       0  408.76  437.28  409.29 4197.57  360.34 6017.73  356.82 6077.77   372.2
 6148.51  352.14 7931.23  350.88 8046.75  370.36 8495.57  346.93  9301.6  344.28
 9417.25  360.68 9653.25  343.2912288.91  356.7713090.76  351.9214954.12  348.87
16304.17  360.3216491.45  337.9316705.35  356.5817869.34   357.119925.13  356.92
19985.24  330.1520138.63  323.7320258.42  355.9620714.75  372.1520879.38  354.32
21039.31  338.5921084.29  357.9627246.89  355.2130125.76   359.530595.58  388.68
#Mann= 12 ,-1 , 0
       0     .07       0  437.28     .07       012288.91      .1       0
13090.76     .07       014954.12      .1       016705.35     .07       0
17869.34     .15       019925.13    .055       020258.42     .15       0
20879.38     .06       027246.89     .05       030125.76     .06       0
Levee=-1,17986.26,369.76,-1,20714.75,372.15,,
#XS Ineff= 2 ,-1
       017986.26     39020714.7530595.58     390
Permanent Ineff=
       F       F
Bank Sta=19925.13,20258.42
XS Rating Curve= 0 ,0
Exp/Cntr=0.3,0.1

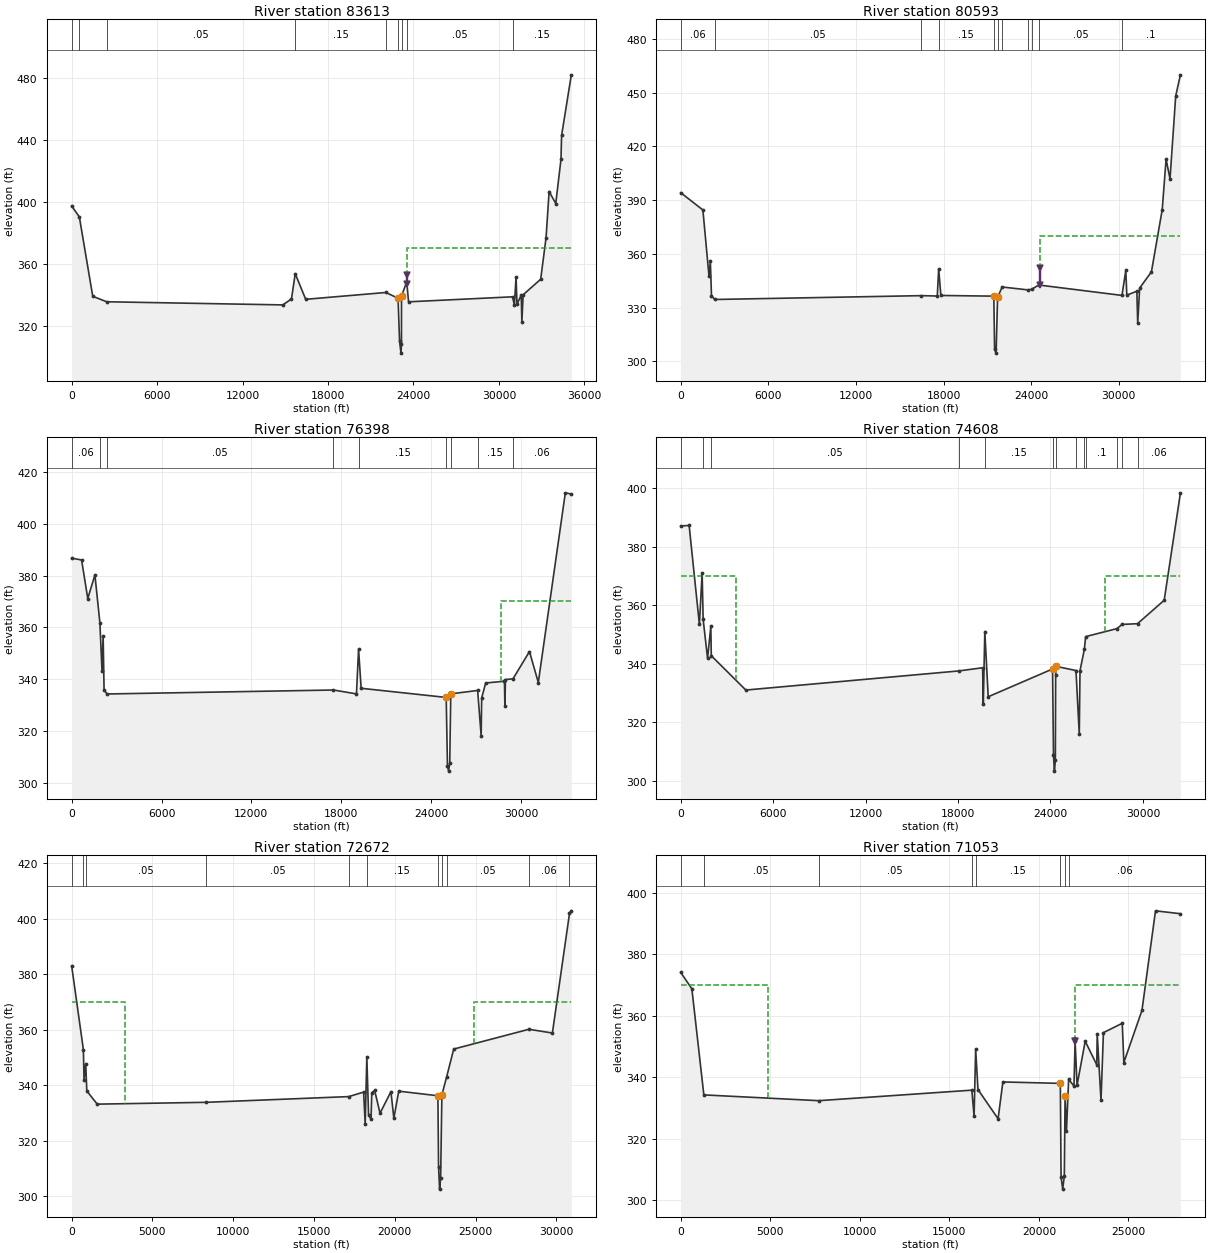
Type RM Length L Ch R = 1 ,83613   ,1518.94,3020.05,1285.42
BEGIN DESCRIPTION:
ROB - Dallas LID14/Ellis LID3
END DESCRIPTION:
XS GIS Cut Line= 5
 2603730.71705116874962.430372162589554.058159446867922.78274316
2582787.478298336868020.815150572581851.714409446867784.70403946
2571296.158853886863163.17626168
#Sta/Elev= 30
       0  397.32  540.81  390.23 1480.71  339.04 2461.87   335.514828.84  333.48
15435.57  337.3415698.16  353.6316433.92  337.09 22060.2  341.4922918.43  337.78
23023.94  310.1423124.06  302.3723156.99  308.27 23160.3  339.2523528.43  348.36
23656.09  335.47 30958.4   338.7 31086.6  333.2431202.91   351.431269.87  333.96
31565.77  339.7931610.92  322.4731700.83  340.0332932.54  350.0433309.22  376.78
33524.86  406.6433991.07  398.8934357.37  427.3634400.71   442.835083.67  481.91
#Mann= 9 ,-1 , 0
       0     .05       0  540.81     .06       0 2461.87     .05       0
15698.16     .15       0 22060.2     .15       022918.43    .055       0
 23160.3     .15       023528.43     .05       0 30958.4     .15       0
Levee=0,,,-1,23541.78,353,,
#XS Ineff= 2 , 0
       0                23541.72       0     370
Permanent Ineff=
       F       F
Bank Sta=22918.43,23160.3
XS Rating Curve= 0 ,0
Exp/Cntr=0.3,0.1

Type RM Length L Ch R = 1 ,80593   ,1304.95,4194.89,2623.31
BEGIN DESCRIPTION:
ROB - Dallas LID14/Ellis LID3
END DESCRIPTION:
XS GIS Cut Line= 6
2604850.392977026873169.60629808 2588498.97540486866569.52707184
2584746.024015916866460.15207184 2584447.41290486866460.15207184
2582244.114293696866392.443738512572504.492187216862954.84292834
#Sta/Elev= 30
       0  394.15  1516.1  384.52 1932.41  347.79  2026.7   355.8 2104.64   336.7
 2330.28  334.5816478.23  336.7217568.33  336.5117663.45  351.74 17813.6  336.82
 21439.5  336.4421493.62   306.721595.69  304.6521696.77  335.7322009.81  341.55
23755.07  339.9524019.96  340.2224517.68  342.6630214.87  336.8530477.93  350.79
30547.66  337.0131235.09  339.1931292.71  321.24 31428.5  340.9732233.27  350.02
 32971.5  384.6633237.13  412.85 33505.8  401.8833895.88  448.14 34219.2  459.92
#Mann= 11 ,-1 , 0
       0     .06       0 2330.28     .05       016478.23     .15       0
17663.45     .15       0 21439.5    .055       021696.77     .15       0
22009.81     .06       023755.07     .15       024019.96     .06       0
24517.68     .05       030214.87      .1       0
Levee=0,,,-1,24580.11,352,,
#XS Ineff= 2 , 0
       0                24580.11       0     370
Permanent Ineff=
       F       F
Bank Sta=21439.5,21696.77
XS Rating Curve= 0 ,0
Exp/Cntr=0.3,0.1

Type RM Length L Ch R = 1 ,76398   ,1366.66,1790.14,1812.24
BEGIN DESCRIPTION:
ROB IFA station 28654: flow expansion due to Dallas LID14/Ellis LID3 levee upstream
LOB IFA station 1699: flow contraction due to Kaufman LID1/Henderson LID1 levee downstream
END DESCRIPTION:
XS GIS Cut Line= 4
2606496.303529836870144.903692242582555.794270566864008.95461815
2581795.377603896863650.621284822574149.081307596862047.68147001
#Sta/Elev= 30
       0  386.75  664.16  386.05 1075.59  371.15 1553.77  380.26 1887.39  361.67
 2028.38     343 2102.55  356.67 2165.46  335.77 2369.57  334.26 17484.7  335.79
19019.32  334.2919159.68  351.5219332.29  336.4625011.92  332.9225095.98  306.48
25173.32  304.4425249.32   307.725316.97  334.3127111.45  335.6227346.03  318.15
27381.17  332.7527648.06  338.5128902.27  339.1828930.64  329.4228969.84  339.84
29472.69  340.1130572.04  350.6631162.57  338.6932967.12     41233367.44  411.53
#Mann= 9 ,-1 , 0
       0     .06       0 1887.39      .1       0 2369.57     .05       0
 17484.7     .15       019159.68     .15       025011.92    .055       0
25316.97     .06       027111.45     .15       029472.69     .06       0
#XS Ineff= 2 , 0
       0    1699     370   28654       0     370
Permanent Ineff=
       F       F
Bank Sta=25011.92,25316.97
XS Rating Curve= 0 ,0
Exp/Cntr=0.3,0.1

Type RM Length L Ch R = 1 ,74608   ,1431.86,1935.4,1883.95
BEGIN DESCRIPTION:
ROB IFA station 27520: flow contraction due to Ellis LID2 levee downstream
LOB IFA station 3583: flow contraction due to Kaufman LID1/Henderson LID1 levee downstream
END DESCRIPTION:
XS GIS Cut Line= 4
2607172.70399279 6868220.89906262583937.460937236863102.84350704
2579097.669270566859799.892118152576528.224826116858723.50322926
#Sta/Elev= 30
       0  386.99  544.02  387.21 1209.35  353.46 1387.84  371.06  1453.2   355.2
 1739.91  341.83 1952.79   352.8 1981.77  342.74 4224.41  331.0318049.59  337.55
19598.54  338.6419639.09  326.3419738.14  350.9919959.74  328.7424137.05  338.22
24196.64  308.8824256.73  303.3624317.16  307.0724337.97  336.15 24351.3  339.12
25656.08  337.6925870.55  315.9925918.44  337.6326199.21  344.8826285.54  349.26
28312.69  351.9928652.85  353.4329650.73  353.6731383.55  361.6732437.45  398.33
#Mann= 13 ,-1 , 0
       0     .06       0  1453.2      .1       0 1981.77     .05       0
18049.59     .15       019738.14     .15       024137.05    .055       0
 24351.3     .06       025656.08     .15       026199.21     .06       0
26285.54      .1       028312.69     .06       028652.85     .05       0
29650.73     .06       0
#XS Ineff= 2 , 0
       0    3583     370   27520       0     370
Permanent Ineff=
       F       F
Bank Sta=24137.05,24351.3
XS Rating Curve= 0 ,0
Exp/Cntr=0.3,0.1

Type RM Length L Ch R = 1 ,72672   ,1501.06,1619.39,1672.71
BEGIN DESCRIPTION:
ROB IFA station 24899: flow contraction due to Ellis LID2 levee downstream
LOB IFA station 3276: flow contraction due to Kaufman LID1/Henderson LID1 levee downstream
END DESCRIPTION:
XS GIS Cut Line= 5
2606198.363715026866971.767118162588441.419270566862638.43378482
2583873.020374556860934.26640181  2579635.8637156859339.82267371
2576476.141492786858575.93378482
#Sta/Elev= 30
       0  383.01   727.2  352.74  766.89  341.94  871.99  347.76  937.51  337.91
 1582.58  333.15 8340.55  333.8117154.88  335.8718074.57  337.4918170.86  326.06
18272.61  350.1918379.52  329.3318533.11  327.6518579.39  337.2818758.24  338.07
19091.29  329.8819765.68  337.6719945.51  328.0220247.72  337.8322673.05  336.17
22712.98  310.65 22777.3  302.5222842.09  306.6622918.57  336.4623219.55   343.1
23651.49     353 28308.2  360.1329760.24  358.7830818.87  401.8830931.89  402.82
#Mann= 11 ,-1 , 0
       0     .06       0   727.2      .1       0  871.99     .05       0
 8340.55     .05       017154.88     .15       018272.61     .15       0
22673.05    .055       022918.57     .15       023219.55     .05       0
 28308.2     .06       030818.87     .06       0
#XS Ineff= 2 , 0
       0    3276     370   24899       0     370
Permanent Ineff=
       F       F
Bank Sta=22673.05,22918.57
XS Rating Curve= 0 ,0
Exp/Cntr=0.3,0.1

Type RM Length L Ch R = 1 ,71053   ,2459.34,3024.49,2512.9
BEGIN DESCRIPTION:
ROB - Ellis LID2
LOB IFA station 4880: flow contraction due to Kaufman LID1/Henderson LID1 levee downstream
END DESCRIPTION:
XS GIS Cut Line= 5
2605863.33767335 6862699.80531262589491.809895566861397.72197927
2585316.462673346860060.916423712584586.601562236859133.13864593
2578762.64322889 6858090.4303126
#Sta/Elev= 30
       0  374.05  619.76  368.76 1289.43  334.25 7702.91  332.3716253.83  335.79
16381.42  327.3416468.21  349.1416598.92  335.9817721.62  326.4917989.07  338.46
21197.53  337.9921239.12  307.5521329.45  303.6121420.01  307.87 21462.5  333.79
21539.34  322.4721661.53  339.3521958.48  337.1222022.37  351.7122131.22  337.35
22586.16   351.723233.27  344.0223256.45  354.0823468.82   332.5 23604.2   354.5
24655.53  357.5324743.94  344.7825755.54  361.7126512.19   394.127904.46  393.16
#Mann= 8 ,-1 , 0
       0     .06       0 1289.43     .05       0 7702.91     .05       0
16253.83     .15       016468.21     .15       021197.53    .055       0
 21462.5     .15       021661.53     .06       0
Levee=0,,,-1,22022.37,351.71,,
#XS Ineff= 2 , 0
       0    4880     37022022.37       0     370
Permanent Ineff=
       F       F
Bank Sta=21197.53,21462.5
XS Rating Curve= 0 ,0
Exp/Cntr=0.3,0.1