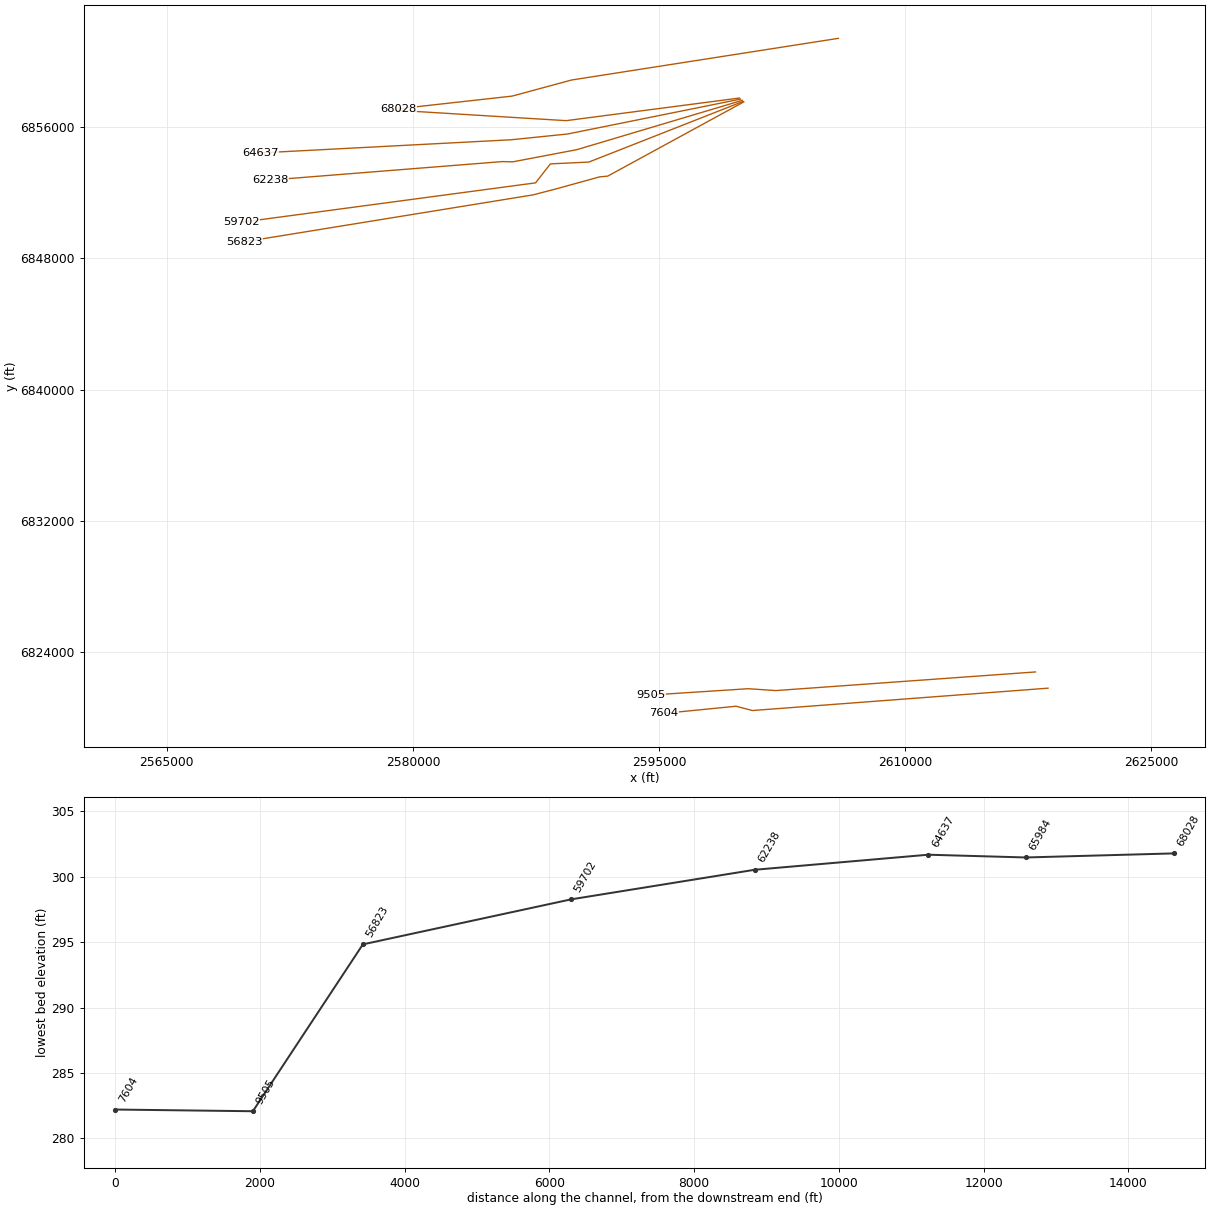
HEC-RAS study TR_FEMA.prj: Trinity_River_FEMA

--- TR_FEMA.g05 (geometry) --- (continued)

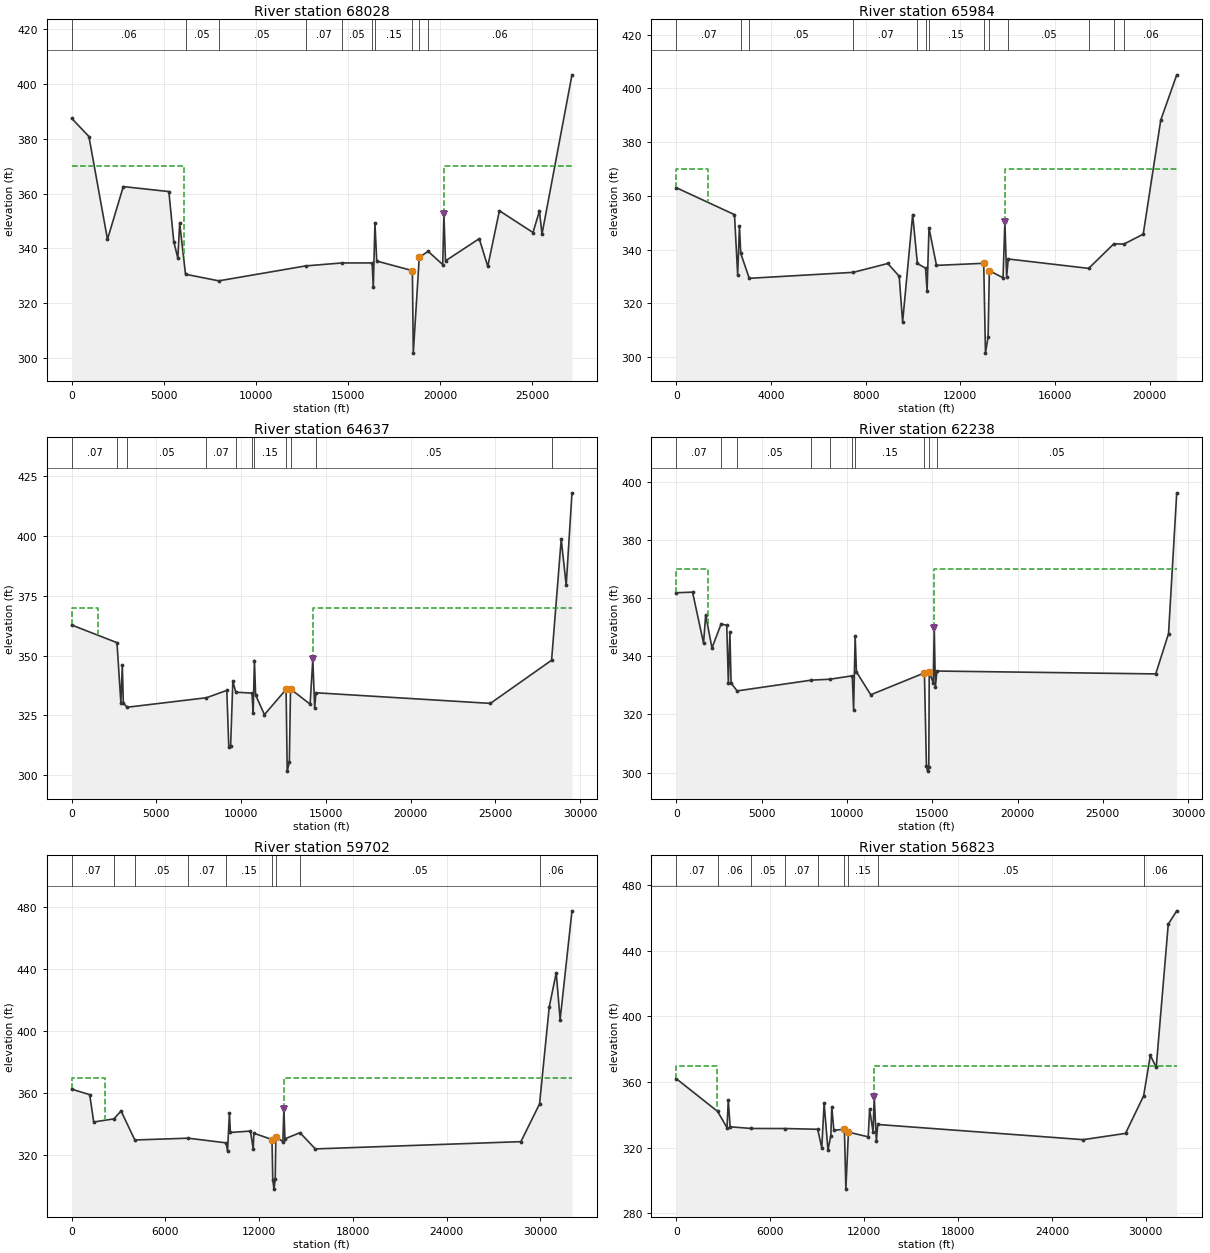
Type RM Length L Ch R = 1 ,68028   ,2550.09,2044.38,1660.23
BEGIN DESCRIPTION:
ROB - Ellis LID2
LOB IFA station 6083: flow contraction due to Kaufman LID1/Henderson LID1 levee downstream
END DESCRIPTION:
XS GIS Cut Line= 4
2605931.785011316861423.225451462589668.590566876858881.67452554
2586047.062789096857900.771747762579138.035011316857129.47545146
#Sta/Elev= 30
       0   387.5  935.94  380.86 1943.46  343.33 2802.54  362.58 5277.51  360.76
 5543.05  342.47  5763.6  336.46 5863.55  349.23 6180.16  330.58 7986.68  328.17
12702.35  333.6214668.17   334.716313.76  334.7116376.19  325.7416466.15  349.24
16563.36   335.418498.82  331.8918547.94  301.7818871.39  336.7219352.53  338.95
20145.87  334.1120209.69   352.620296.95  335.4722128.28  343.5722591.26  333.46
23223.39  353.76 25046.8  345.81 25397.3  353.6525536.06  345.2527164.56  403.38
#Mann= 10 ,-1 , 0
       0     .06       0 6180.16     .05       0 7986.68     .05       0
12702.35     .07       014668.17     .05       016313.76     .15       0
16466.15     .15       018498.82    .055       018871.39     .15       0
19352.53     .06       0
Levee=0,,,-1,20209.69,352.6,,
#XS Ineff= 2 ,-1
       0    6083     37020209.7127164.56     370
Permanent Ineff=
       F       F
Bank Sta=18498.82,18871.39
XS Rating Curve= 0 ,0
Exp/Cntr=0.3,0.1

Type RM Length L Ch R = 1 ,65984   ,761.4,1346.66,1829.69
BEGIN DESCRIPTION:
ROB - Ellis LID2
LOB IFA station 1349: flow contraction due to Kaufman LID1/Henderson LID1 levee downstream
END DESCRIPTION:
XS GIS Cut Line= 4
2599899.674578646857782.477761572589338.451606636856402.66982564
2586149.562643236856597.114318642578859.972563656857045.02648056
#Sta/Elev= 30
       0  363.01 2454.07  353.01 2589.02  330.55 2663.99  348.86 2718.96  338.58
 3078.82  329.31 7477.09  331.54 8936.51  334.83 9416.33  330.09 9561.27  313.02
  9986.1  353.0310186.02  334.8310530.89  333.0710595.86  324.7510676.33  348.07
10993.27  334.1312989.66   334.913063.81  301.4713175.51  307.5413227.37  332.13
13807.24  329.5313884.37  350.3313958.72  329.8914025.36   336.517427.05  333.01
18489.29  342.1518916.26  342.0519732.17  345.7420473.26  388.1821149.13  405.04
#Mann= 13 ,-1 , 0
       0     .07       0 2718.96     .06       0 3078.82     .05       0
 7477.09     .07       010186.02     .05       010530.89     .15       0
10676.33     .15       012989.66    .055       013227.37     .06       0
14025.36     .05       017427.05     .06       018489.29     .05       0
18916.26     .06       0
Levee=0,,,-1,13884.37,350.33,,
#XS Ineff= 2 ,-1
       0    1349     37013884.3221149.13     370
Permanent Ineff=
       F       F
Bank Sta=12989.66,13227.37
XS Rating Curve= 0 ,0
Exp/Cntr=0.3,0.1

Type RM Length L Ch R = 1 ,64637   ,1009.07,2399.06,1604.33
BEGIN DESCRIPTION:
ROB - Ellis LID2
LOB IFA station 1544: flow contraction due to Kaufman LID1/Henderson LID1 levee downstream
END DESCRIPTION:
XS GIS Cut Line= 4
2599965.936913316857716.215426892589427.340536486855588.78103347
2585969.007230046855236.003195732570686.948883476854434.65768556
#Sta/Elev= 30
       0  362.84 2674.05  355.45 2903.96  330.26 2988.93  346.18 3048.91  330.12
 3273.83  328.42 7947.17  332.39 9156.71  335.47 9271.66  311.98 9381.62  312.13
 9511.57  339.22  9691.5  334.7110641.13  334.34 10711.1  326.1910786.73  347.98
10856.94  333.5711375.03  325.32 12655.1  335.8812722.57  301.6812847.47  305.35
12917.21  336.05   14074  329.7114232.38  348.5214343.15  328.1414416.02  334.48
24712.42  330.0328326.19  348.0828895.17  398.7729188.35  379.4529530.52  418.16
#Mann= 11 ,-1 , 0
       0     .07       0 2674.05     .06       0 3273.83     .05       0
 7947.17     .07       0  9691.5     .05       010641.13     .15       0
10786.73     .15       0 12655.1    .055       012917.21     .06       0
14416.02     .05       028326.19     .06       0
Levee=0,,,-1,14232.38,348.52,,
#XS Ineff= 2 ,-1
       0    1544     37014233.2229530.52     370
Permanent Ineff=
       F       F
Bank Sta=12655.1,12917.21
XS Rating Curve= 0 ,0
Exp/Cntr=0.3,0.1

Type RM Length L Ch R = 1 ,62238   ,934.88,2536.56,1721.21
BEGIN DESCRIPTION:
ROB - Ellis LID2
LOB IFA station 1823: flow contraction due to Kaufman LID1/Henderson LID1 levee downstream
END DESCRIPTION:
XS GIS Cut Line= 5
 2600070.0630174 6857640.48723192589996.437823476854635.30885907
2586090.592944896853892.311001232585441.287484976853906.20008107
2571292.502462396852779.63737357
#Sta/Elev= 30
       0   361.8  944.76  362.01  1589.6   344.5 1714.56  354.18 2084.47  342.84
 2619.34  351.08 2949.25  350.62 3044.23  330.72 3134.21  348.27 3204.19  330.77
  3559.1  328.08 7917.97  331.79 8987.74  332.0910307.48  333.2710387.47  321.62
10477.67  346.8610552.87  334.6311392.43  326.76   14538  334.2714657.47  302.21
14722.48  300.5314793.15  301.8814821.85  334.5615054.51  330.8615115.79  349.72
15180.49  329.3515272.27  334.9128099.84  333.9228850.59  347.7729331.23  396.12
#Mann= 10 ,-1 , 0
       0     .07       0 2619.34     .06       0  3559.1     .05       0
 7917.97     .07       0 8987.74     .05       010307.48     .15       0
10477.67     .15       0   14538    .055       014821.85     .06       0
15272.27     .05       0
Levee=0,,,-1,15115.79,349.72,,
#XS Ineff= 2 ,-1
       0    1823     37015115.5229331.23     370
Permanent Ineff=
       F       F
Bank Sta=14538,14821.85
XS Rating Curve= 0 ,0
Exp/Cntr=0.3,0.1

Type RM Length L Ch R = 1 ,59702   ,1056.97,2878.56,838.01
BEGIN DESCRIPTION:
ROB - Ellis LID2
LOB IFA station 2141: flow contraction due to Kaufman LID1/Henderson LID1 levee downstream
END DESCRIPTION:
XS GIS Cut Line= 5
 2600117.39330336857574.224897222590721.588932226853876.65125564
2588378.092963076853766.616698822587474.751265796852609.13804264
2569517.328847386850204.46371815
#Sta/Elev= 30
       0  362.63 1154.68  359.07 1409.61  341.48 2704.25   343.5 3159.13  348.59
 4043.89   329.9 7452.94  331.07 9882.27  328.06 9977.25  322.8510099.32  347.32
10159.24  334.7711445.83  335.6411621.68  324.0511661.96  334.2612824.23   330.2
12873.03  304.45 12951.6  298.2713031.31  304.8513070.14  332.0213518.94  328.85
13585.21  350.0913652.52  330.6514614.64   334.6   15599  324.1628757.88  328.84
29952.04   353.130574.18  415.67 31020.4  437.5131270.17  407.4132029.23  477.42
#Mann= 9 ,-1 , 0
       0     .07       0 2704.25     .06       0 4043.89     .05       0
 7452.94     .07       0 9882.27     .15       012824.23    .055       0
13070.14     .15       014614.64     .05       029952.04     .06       0
Levee=0,,,-1,13585.21,350.09,,
#XS Ineff= 2 ,-1
       0    2141     37013584.9632029.23     370
Permanent Ineff=
       F       F
Bank Sta=12824.23,13070.14
XS Rating Curve= 0 ,0
Exp/Cntr=0.3,0.1

Type RM Length L Ch R = 1 ,56823   ,1814.93,1520.67,905.82
BEGIN DESCRIPTION:
ROB - Ellis LID2
LOB IFA station 2614: flow contraction due to Kaufman LID1/Henderson LID1 levee downstream
END DESCRIPTION:
XS GIS Cut Line= 6
2600164.723589216857545.826660072591868.659144646853018.84982164
2591375.143071296852974.125173552588772.712580656852253.63908173
2587328.241060146851877.223824052569716.981663326849015.22790764
#Sta/Elev= 30
       0  362.01 2628.83  342.19 3233.56  332.27 3313.52  349.09 3433.47  332.78
 4782.89  331.77    6952  331.73 9031.16  331.28 9291.06  319.89 9441.28  347.18
 9686.46  318.71 9869.48  327.38 9931.25  344.8610063.92  330.6410737.48  331.34
10830.73  294.8310995.67  329.5612257.78  326.6612349.83  343.4212568.44  329.76
12644.66  351.0612780.08  324.0812869.66   334.226003.58  324.9628707.25  328.77
29865.42  351.6430294.22  376.3130669.65  369.0431440.07   456.2 31981.7  464.31
#Mann= 9 ,-1 , 0
       0     .07       0 2628.83     .06       0 4782.89     .05       0
    6952     .07       0 9031.16     .15       010737.48    .055       0
10995.67     .15       012869.66     .05       029865.42     .06       0
Levee=0,,,-1,12644.66,351.06,,
#XS Ineff= 2 ,-1
       0    2614     370 12642.8 31981.7     370
Permanent Ineff=
       F       F
Bank Sta=10737.48,10995.67
XS Rating Curve= 0 ,0
Exp/Cntr=0.3,0.1

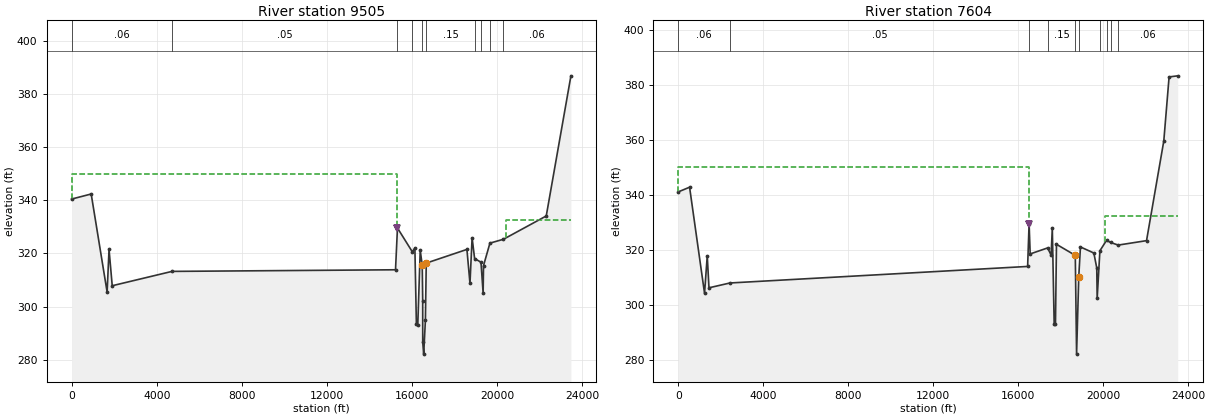
Type RM Length L Ch R = 1 ,9505    ,1134.79,1900.98,1032.38
BEGIN DESCRIPTION:
LOB - Kaufman LID1/Henderson LID1
END DESCRIPTION:
XS GIS Cut Line= 4
  2617943.653671  6822780.116724 2602120.2802758  6821643.751677
 2600430.9125433 6821757.1829476 2594525.7712673 6821374.0195375
#Sta/Elev= 30
       0   340.5  919.31  342.41  1668.9  305.46 1758.73  321.51 1908.43  307.85
 4718.92  313.25 15227.5  313.8615319.42  329.5916014.85  320.6716138.72  322.04
16208.93  293.4216274.19  293.01 16389.1  321.1916483.71  315.5916505.97  302.11
16507.06   286.616552.25  282.0816633.09  294.9316672.79  316.3718584.62  321.53
18728.66  308.7218828.48  325.8918946.26  318.0919245.89  316.7119346.87  305.02
19365.78  315.4519666.52   323.920300.58  325.3522314.28  334.1323474.79  386.93
#Mann= 10 ,-1 , 0
       0     .06       0 4718.92     .05       015319.42     .06       0
16014.85     .15       016483.71    .055       016672.79     .15       0
18946.26     .05       019245.89     .15       019666.52     .05       0
20300.58     .06       0
Levee=-1,15319.42,329.59,0,,,,
#XS Ineff= 2 , 0
       015319.21     35020419.34       0   332.5
Permanent Ineff=
       F       F
Bank Sta=16483.71,16672.79
XS Rating Curve= 0 ,0
Exp/Cntr=0.3,0.1

Type RM Length L Ch R = 1 ,7604    ,1109.26,1315.69,1024.77
BEGIN DESCRIPTION:
LOB - Kaufman LID1/Henderson LID1
END DESCRIPTION:
XS GIS Cut Line= 4
  2618706.625802  6821790.315041 2600688.1924188 6820426.8980209
  2599694.164641 6820689.1896876 2595306.2479743 6820253.2869098
#Sta/Elev= 30
       0  341.11  524.17  342.78 1228.28   304.3 1355.65  317.87 1437.33  306.28
 2425.82  308.0316439.61  314.0316509.06  329.6116559.86  318.5717380.66  320.75
17546.34  318.1217601.51  327.9817689.72  293.1217750.21  292.9817797.94  322.06
18683.77  318.0518744.51  282.2118846.83  310.2818926.93   321.119558.28   318.9
19694.32  313.4819714.03  302.4719842.43  319.7220153.77  323.4920349.21  322.72
20704.53  321.7822037.77  323.3922850.49  359.5523099.93   382.823507.45   383.2
#Mann= 10 ,-1 , 0
       0     .06       0 2425.82     .05       016509.06     .06       0
17380.66     .15       018683.77    .055       018846.83     .15       0
19842.43     .05       020153.77     .15       020349.21     .05       0
20704.53     .06       0
Levee=-1,16509.06,329.61,0,,,,
#XS Ineff= 2 , 0
       0   16509     35020091.76       0   332.5
Permanent Ineff=
       F       F
Bank Sta=18683.77,18846.83
XS Rating Curve= 0 ,0
Exp/Cntr=0.3,0.1

--- TR_FEMA.g06 (geometry) ---

Geom Title=Trinity_NV_DallasLID14_EllisLID3
Program Version=5.06
BEGIN GEOM DESCRIPTION:
Scenario D
END GEOM DESCRIPTION:

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
River Reach=Trinity River   ,1

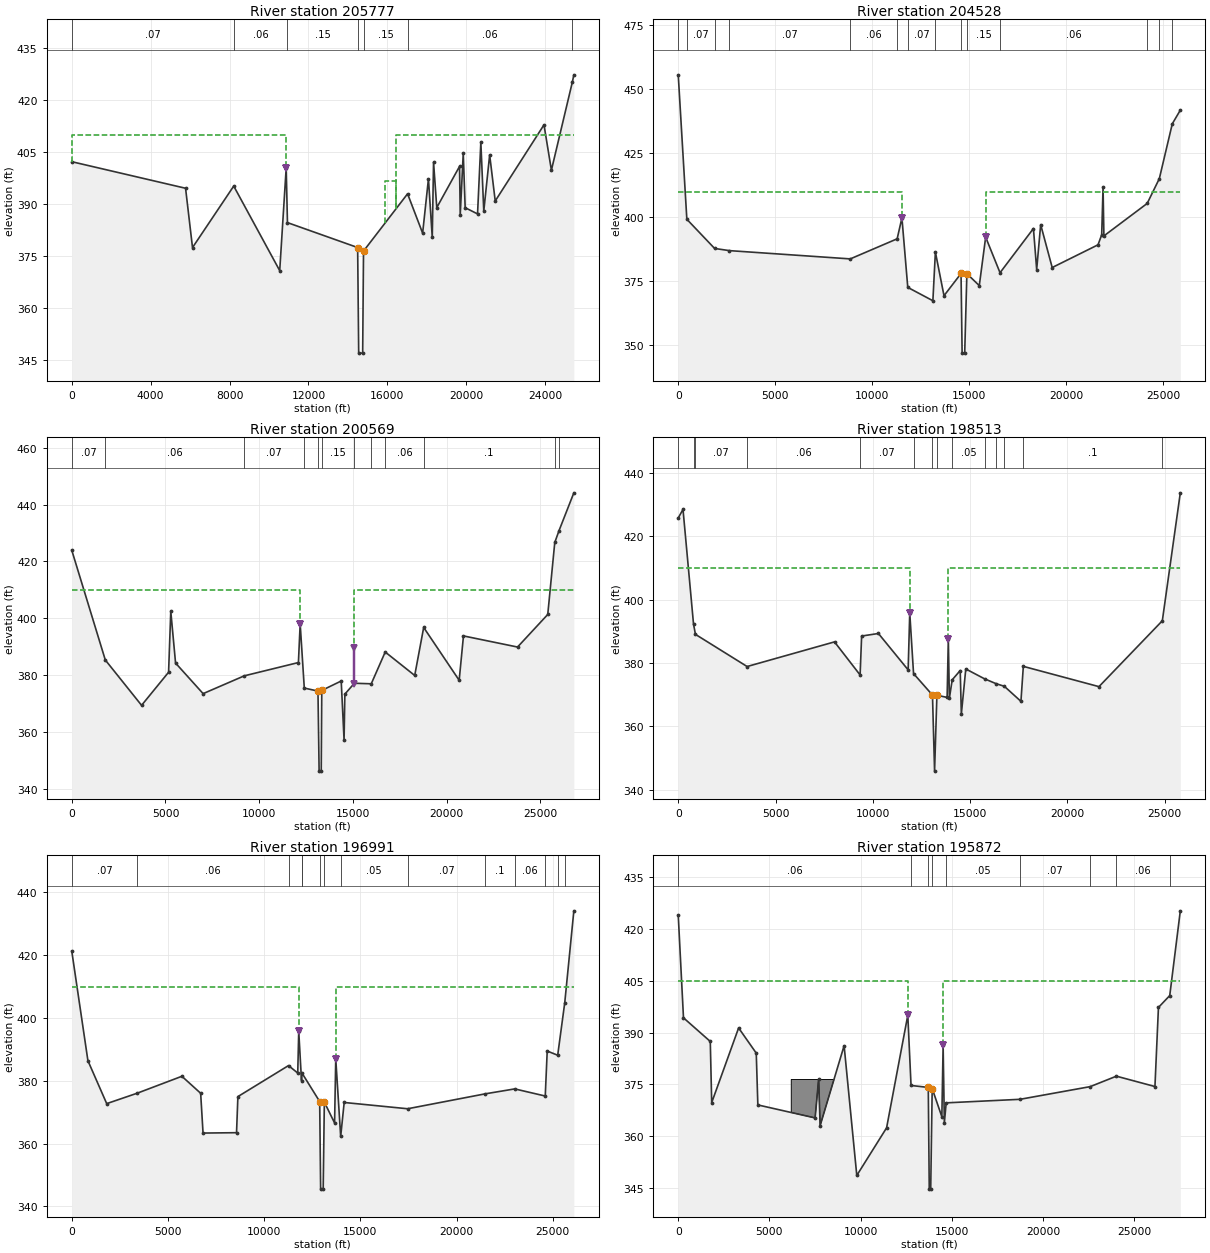
Type RM Length L Ch R = 1 ,205777  ,1262.75,1248.24,1229.51
BEGIN DESCRIPTION:
LOB - Southside WWTP
ROB IFA station 16416: flow contraction due to Dallas LID1/2 levee downstream
END DESCRIPTION:
XS GIS Cut Line= 6
2540980.83019298 6933539.73664742535497.477602626924208.30611411
2533614.000070366920921.000024692533600.635923866920903.28221235
 2529903.70565376914444.53364694 2528203.05241526911525.84775851
#Sta/Elev= 30
       0  402.32 5769.27  394.66 6121.02  377.55 8210.64  395.2910542.62  370.89
10870.96  400.54 10934.7  384.7514493.46  377.5614546.29   347.114748.07   347.1
14791.42  376.5417024.34  393.0617788.14  381.7118082.62  397.3718276.12  380.47
18341.35  402.1718504.74  389.0819659.18  400.9719693.92  387.0319847.13  404.74
19944.42  389.0520572.06  387.2620739.04  407.9220887.76  388.0721186.02  404.29
21468.32  390.9923940.48  412.9624316.52  399.8725381.49  425.37 25454.1  427.38
#Mann= 7 ,-1 , 0
       0     .07       0 8210.64     .06       0 10934.7     .15       0
14493.46    .055       014791.42     .15       017024.34     .06       0
25381.49     .08       0
Levee=-1,10870.96,400.54,0,,,,
#XS Ineff= 3 ,-1
       010870.96     41015871.74   16416  396.63   16416 25454.1     410
Permanent Ineff=
       F       F       F
Bank Sta=14493.46,14791.42
XS Rating Curve= 0 ,0
Exp/Cntr=0.3,0.1

Type RM Length L Ch R = 1 ,204528  ,2887.05,3959.05,2930.12
BEGIN DESCRIPTION:
LOB - Southside WWTP, ROB - Dallas LID1/2
END DESCRIPTION:
XS GIS Cut Line= 2
2542141.897480176933195.790666072529164.466924626910799.95733273
#Sta/Elev= 30
       0  455.63  443.94  399.25 1874.77  387.86 2636.03  387.01 8868.79  383.78
 11286.5  391.6211531.94  399.8111833.59  372.66   13128  367.4513257.32  386.45
13701.35  369.4114580.29  378.0914635.11     34714768.51     34714880.75  378.02
 15520.2  373.3515849.58  392.2716589.78  378.3818311.86  395.6418478.88  379.64
18685.27  397.1519279.01  380.4121641.73  389.2821830.52  393.1621901.42  411.66
21944.71  392.7524176.62  405.4324802.88  415.12 25470.9  436.52 25884.1  441.84
#Mann= 14 ,-1 , 0
       0     .06       0  443.94     .07       0 1874.77     .06       0
 2636.03     .07       0 8868.79     .06       0 11286.5     .07       0
11833.59     .07       013257.32     .15       014580.29    .055       0
14880.75     .15       016589.78     .06       024176.62      .1       0
24802.88     .08       0 25470.9     .06       0
Levee=-1,11531.94,399.81,-1,15849.58,392.27,,
#XS Ineff= 2 ,-1
       011531.94     41015849.58 25884.1     410
Permanent Ineff=
       F       F
Bank Sta=14580.29,14880.75
XS Rating Curve= 0 ,0
Exp/Cntr=0.3,0.1

Type RM Length L Ch R = 1 ,200569  ,2068.54,2056.32,2002.94
BEGIN DESCRIPTION:
LOB - Southside WWTP, ROB - Dallas LID1/2
END DESCRIPTION:
XS GIS Cut Line= 2
2544594.042023046931842.514654862531312.792023046908578.62576596
#Sta/Elev= 30
       0  423.94 1788.99  385.37 3724.12  369.43 5165.31  381.06  5282.7  402.49
 5537.92  384.29 7008.09  373.54 9204.36   379.8 12092.6  384.4712186.52  398.09
12405.92   375.513135.77  374.4413197.04   346.313309.94   346.313339.14  374.67
14376.03  377.98 14528.7  357.2114570.62  373.3715078.25  377.1915978.95     377
16723.98  388.1718297.74  379.9318776.03   396.820669.98  378.2320898.87  393.83
23784.09  389.9225396.01  401.3725770.55  426.6825998.04  430.8526788.13  444.13
#Mann= 12 ,-1 , 0
       0     .07       0 1788.99     .06       0 9204.36     .07       0
12405.92     .15       013135.77    .055       013339.14     .15       0
15078.25     .05       015978.95     .15       016723.98     .06       0
18776.03      .1       025770.55     .06       025998.04      .1       0
Levee=-1,12186.52,398.09,-1,15042.98,389.42,,
#XS Ineff= 2 , 0
       012186.52     41015042.98       0     410
Permanent Ineff=
       F       F
Bank Sta=13135.77,13339.14
XS Rating Curve= 0 ,0
Exp/Cntr=0.3,0.1

Type RM Length L Ch R = 1 ,198513  ,1460.65,1522.21,1546.82
BEGIN DESCRIPTION:
LOB - Southside WWTP, ROB - Dallas LID1/2
END DESCRIPTION:
XS GIS Cut Line= 2
2546593.000356376930554.320210412533259.667023046908470.98687708
#Sta/Elev= 30
       0  425.75  245.08  428.46  785.82  392.24  884.58  389.01 3538.59  378.86
  8028.9  386.64 9344.62  376.19 9422.44  388.4810284.69  389.2911812.69   377.8
11895.24  395.8312090.23  376.6313062.88  369.8413170.69  345.8413290.24  369.79
13815.75  369.1113876.77  387.6313931.21  368.8614077.49  374.6714487.86   377.6
14545.98  363.8614774.24  378.0915737.73  374.9816333.56  373.4416753.99  372.62
17607.92  367.8717730.47  378.9121616.22  372.5124872.14   393.325796.39  433.69
#Mann= 14 ,-1 , 0
       0     .07       0  785.82     .06       0  884.58     .07       0
 3538.59     .06       0 9344.62     .07       012090.23     .15       0
13062.88    .055       013290.24     .15       014077.49     .05       0
15737.73     .15       016333.56     .05       016753.99      .1       0
17730.47      .1       024872.14     .06       0
Levee=-1,11895.24,395.83,-1,13876.77,387.63,,
#XS Ineff= 2 , 0
       011895.24     41013876.77       0     410
Permanent Ineff=
       F       F
Bank Sta=13062.88,13290.24
XS Rating Curve= 0 ,0
Exp/Cntr=0.3,0.1

Type RM Length L Ch R = 1 ,196991  ,1114.91,1119.14,1044.18
BEGIN DESCRIPTION:
LOB - Southside WWTP, ROB - Dallas LID1/2
END DESCRIPTION:
XS GIS Cut Line= 4
2547677.578059796929952.10407455 2541957.4391709 6920324.0658801
2540764.383615346917785.437407882533997.022504236907764.60407454
#Sta/Elev= 30
       0  421.27  839.66  386.38 1815.93  372.72 3409.48  376.06 5723.11  381.43
 6699.35  376.02 6823.04  363.35 8563.77  363.47  8634.5  374.9611265.75  384.84
11744.94  382.4611797.07   395.811940.64  380.0711963.21  382.48 12885.5  373.39
12935.15   345.513068.07   345.513127.74   373.213659.69  366.5713720.65  387.01
13977.28  362.2714158.97  373.0917457.43  371.09 21480.1  375.8323024.23  377.41
24609.89  375.1424711.78  389.4725256.73  388.1325623.98  404.8926096.06  434.11
#Mann= 14 ,-1 , 0
       0     .07       0 3409.48     .06       011265.75     .07       0
11940.64     .06       011963.21     .15       0 12885.5    .055       0
13127.74     .15       013977.28     .05       017457.43     .07       0
 21480.1      .1       023024.23     .06       024609.89      .1       0
25256.73     .06       025623.98     .08       0
Levee=-1,11797.07,395.8,-1,13720.65,387.01,,
#XS Ineff= 2 , 0
       011797.07     41013720.65       0     410
Permanent Ineff=
       F       F
Bank Sta=12885.5,13127.74
XS Rating Curve= 0 ,0
Exp/Cntr=0.3,0.1

Type RM Length L Ch R = 1 ,195872  ,1736.76,1726.95,2123
BEGIN DESCRIPTION:
LOB - Southside WWTP, ROB - Dallas LID1/2
END DESCRIPTION:
XS GIS Cut Line= 4
2550259.667023046929359.875765962543024.453059796920010.14805602
2541811.258615346917361.536944912534173.275757926907095.38516339
#Sta/Elev= 30
       0  423.88  287.75  394.24 1757.09  387.42    1835  369.77 3310.85  391.32
 4278.01  384.05 4365.39   369.1 7505.83  365.35 7698.96  376.54    7781  363.13
 9095.51  386.19 9791.23  348.7511425.27  362.49   12588  394.9912765.73  374.72
13710.48  374.1513764.86   344.813843.92   344.813925.96  373.8214455.32  365.69
14525.15  386.3414592.48  363.9514693.44   369.718740.62  370.7222588.93  374.38
24027.44   377.426140.25  374.4126332.27  397.2426951.71  400.66 27531.3  425.12
#Mann= 9 ,-1 , 0
       0     .06       012765.73     .15       013710.48    .055       0
13925.96     .15       014693.44     .05       018740.62     .07       0
22588.93      .1       024027.44     .06       026951.71     .08       0
Levee=-1,12588,394.99,-1,14525.15,386.34,,
#XS Ineff= 2 , 0
       0   12588     40514525.15       0     405
Permanent Ineff=
       F       F
#Block Obstruct= 1 ,-1
 6197.83 8582.22  376.44
Bank Sta=13710.48,13925.96
XS Rating Curve= 0 ,0
Exp/Cntr=0.3,0.1