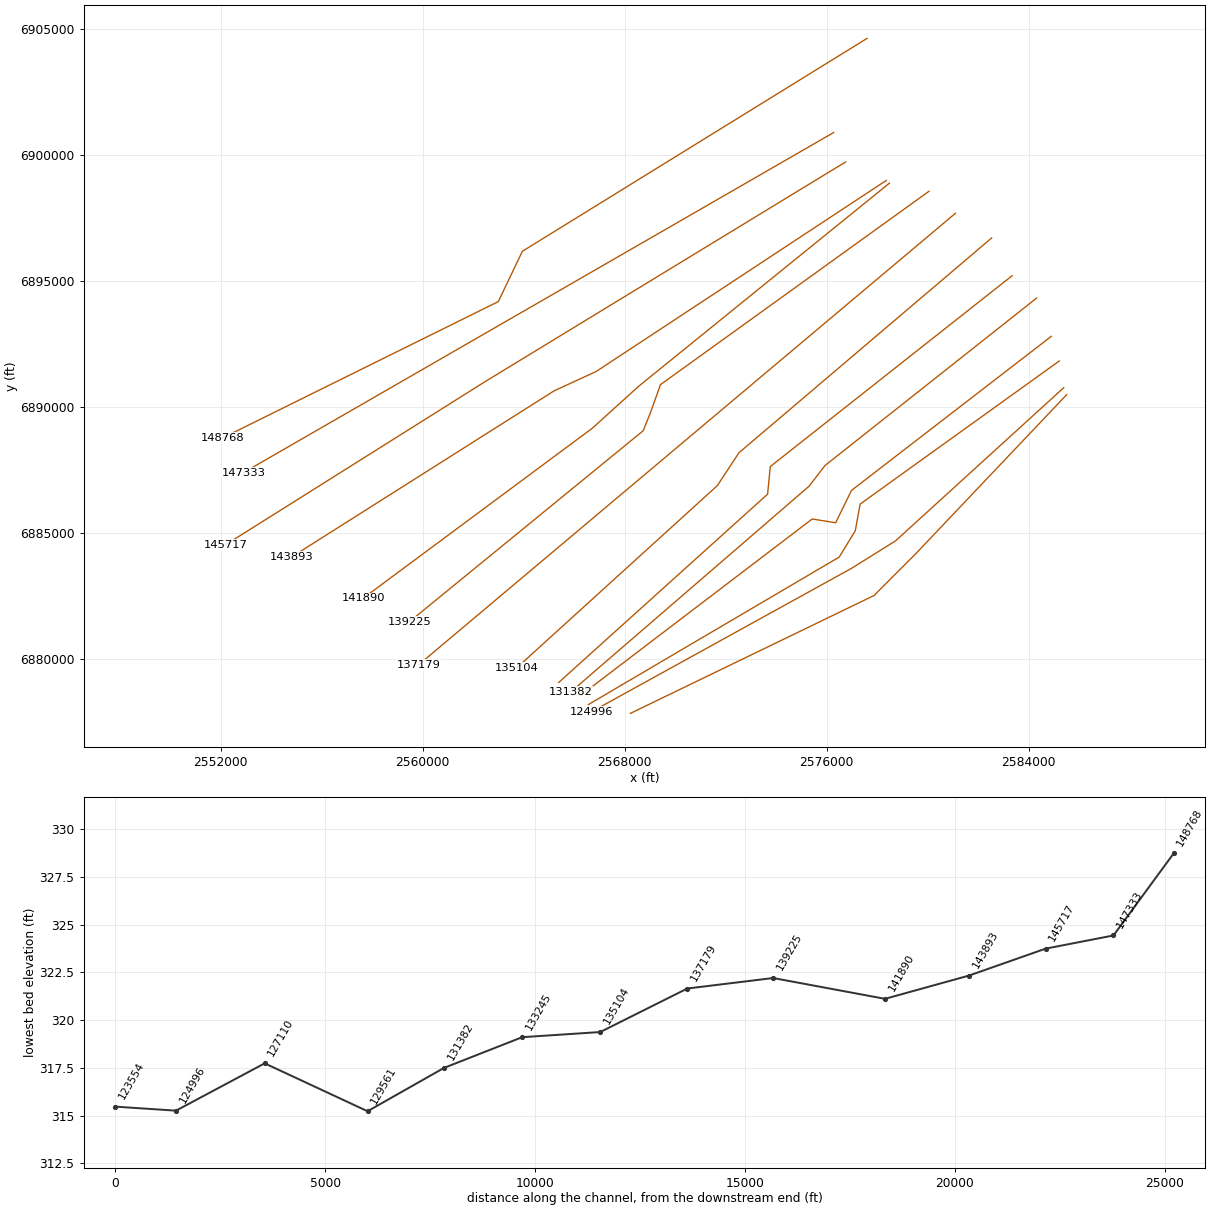
HEC-RAS study TR_FEMA.prj: Trinity_River_FEMA

--- TR_FEMA.g06 (geometry) --- (continued)

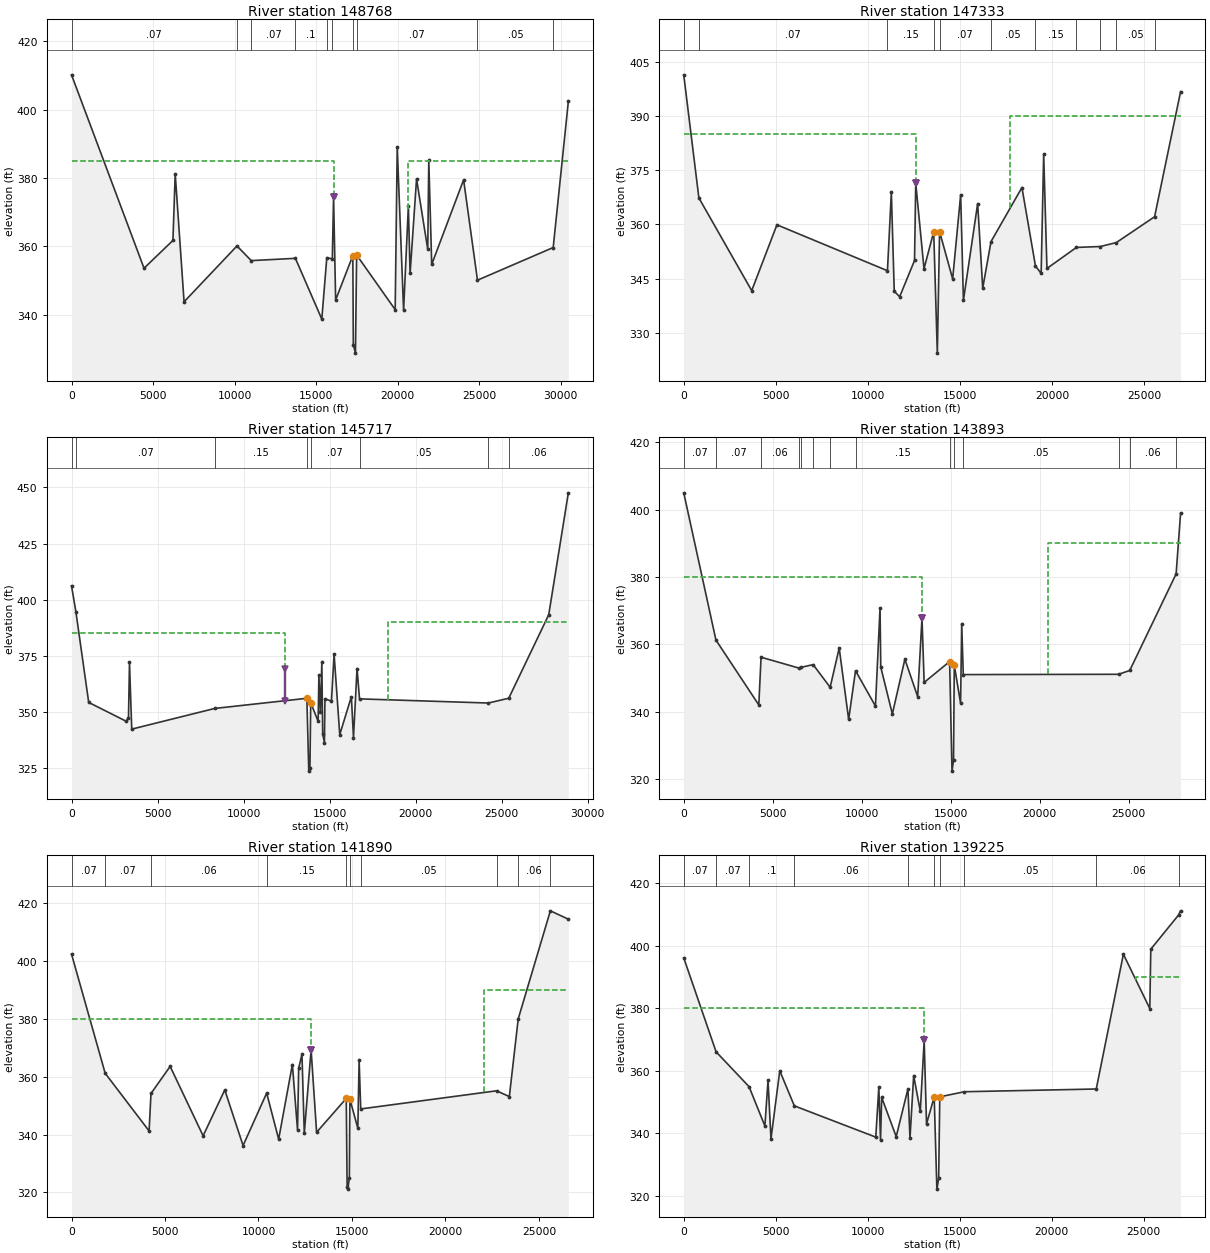
Type RM Length L Ch R = 1 ,148768  ,2180.3,1434.55,1008.26
BEGIN DESCRIPTION:
LOB - Bois D'Arc
ROB IFA station 20644: flow expansion due to Dallas LID1/2 levee upstream
END DESCRIPTION:
XS GIS Cut Line= 4
2577606.524819086904625.264954192563948.885930186896182.44088012
 2562996.10815246894187.996435672552068.006300556888778.94550974
#Sta/Elev= 30
       0   410.2 4445.82  353.59 6217.95  361.73 6357.72  381.24 6900.93  343.76
10144.33  360.1111018.73  355.8213727.42  356.4915344.99  338.6915651.79  356.69
15990.23  356.33 16066.7  374.5416193.44   344.317248.37  357.3117277.84  331.16
17408.81  328.7417480.52  357.4719844.38  341.4719969.15     38920360.09  341.27
 20652.3  371.7820758.15  352.0521154.15  379.7221840.75  359.1421903.79  385.29
22083.69  354.7224039.39  379.4624889.55  350.0929531.82  359.6530460.41  402.43
#Mann= 10 ,-1 , 0
       0     .07       010144.33      .1       011018.73     .07       0
13727.42      .1       015651.79     .07       015990.23     .15       0
17248.37    .055       017480.52     .07       024889.55     .05       0
29531.82     .06       0
Levee=-1,16066.7,374.54,0,,,,
#XS Ineff= 2 ,-1
       0 16066.7     385   2064430460.41     385
Permanent Ineff=
       F       F
Bank Sta=17248.37,17480.52
XS Rating Curve= 0 ,0
Exp/Cntr=0.3,0.1

Type RM Length L Ch R = 1 ,147333  ,1522.48,1615.72,1708.82
BEGIN DESCRIPTION:
LOB - Bois D'Arc
ROB IFA station 17728: flow expansion due to Dallas LID1/2 levee upstream
END DESCRIPTION:
XS GIS Cut Line= 2
2576276.933184796900889.164637482552908.284078336887410.88995419
#Sta/Elev= 30
       0  401.37  822.29  367.34 3690.28  341.71  5060.3  359.9111061.22  347.22
11272.42  368.9211430.28  341.5411723.82  340.0312531.27  350.0512596.91  371.45
13046.23  347.7713573.14  357.9713769.15  324.44 13891.7  358.0314601.28  344.96
15036.43  368.2115185.93  339.0415959.54  365.7716234.04   342.416684.98  355.28
18363.08  370.2119098.34  348.5219406.18  346.4919544.29  379.3819721.06  347.84
21322.53  353.6622624.37  353.9123487.85     35525566.94  362.1426977.04  396.71
#Mann= 11 ,-1 , 0
       0     .07       0  822.29     .07       011061.22     .15       0
13573.14    .055       0 13891.7     .07       016684.98     .05       0
19098.34     .15       021322.53     .05       022624.37     .08       0
23487.85     .05       025566.94     .06       0
Levee=-1,12596.91,371.45,0,,,,
#XS Ineff= 2 , 0
       012596.91     385   17728       0     390
Permanent Ineff=
       F       F
Bank Sta=13573.14,13891.7
XS Rating Curve= 0 ,0
Exp/Cntr=0.3,0.1

Type RM Length L Ch R = 1 ,145717  ,2352.85,1824.58,1766.13
BEGIN DESCRIPTION:
LOB - Bois D'Arc
ROB IFA station 18413: flow expansion due to Dallas LID1/2 levee upstream
END DESCRIPTION:
XS GIS Cut Line= 3
2576750.617863126899723.127008332562501.812617966891032.92161155
2552179.679563736884538.09631899
#Sta/Elev= 30
       0   406.2  255.83  394.59  999.97  354.31 3176.04  345.95 3312.42  347.44
 3370.76  372.11 3501.63  342.43 8331.41  351.6413682.74  356.1513794.34  323.75
13862.02  325.09 13907.7  354.1414338.01  345.9414382.71   366.314470.26  349.86
14554.33  372.1914603.38  340.3214704.13  336.4414734.37   355.9 15112.4  354.91
15266.05  375.7215595.33  339.9916270.53  356.8516393.24  338.6316600.02  369.38
16744.27  355.8924236.03  354.0425420.18  356.1827744.78  393.3128885.25  447.54
#Mann= 8 ,-1 , 0
       0     .07       0  255.83     .07       0 8331.41     .15       0
13682.74    .055       0 13907.7     .07       016744.27     .05       0
24236.03     .15       025420.18     .06       0
Levee=-1,12408.07,369.23,0,,,,
#XS Ineff= 2 , 0
       012408.07     385   18413       0     390
Permanent Ineff=
       F       F
Bank Sta=13682.74,13907.7
XS Rating Curve= 0 ,0
Exp/Cntr=0.3,0.1

Type RM Length L Ch R = 1 ,143893  ,1386.21,2002.89,2192.25
BEGIN DESCRIPTION:
LOB - Bois D'Arc
ROB IFA station 20433: flow expansion due to Dallas LID1/2 levee upstream
END DESCRIPTION:
XS GIS Cut Line= 4
2578362.103522786898989.489491232566872.207689446891416.57282456
2565204.464633896890648.517269012554808.631300566884061.71171345
#Sta/Elev= 30
       0  405.02  1809.1  361.27 4215.91  342.01 4343.07  356.18 6490.13  352.93
 6578.34  353.16 7266.71  353.98 8222.76  347.25 8731.12   358.9 9262.43  337.71
 9648.58  352.1610767.26  341.6611025.21  370.8311066.73  353.24 11716.3  339.32
12420.42  355.5813139.14  344.4713381.12  367.8213503.12  348.69   14933   354.9
15066.51  322.34 15152.1  325.5115195.09  353.8415548.36  342.5115611.78  366.16
15700.22  351.0224423.11  351.1125048.71  352.2427653.42  380.9327904.03  398.92
#Mann= 14 ,-1 , 0
       0     .07       0  1809.1     .07       0 4343.07     .06       0
 6490.13     .07       0 6578.34     .06       0 7266.71     .07       0
 8222.76     .06       0 9648.58     .15       0   14933    .055       0
15195.09     .15       015700.22     .05       024423.11      .1       0
25048.71     .06       027653.42     .06       0
Levee=-1,13381.12,367.82,0,,,,
#XS Ineff= 2 , 0
       013381.12     380   20433       0     390
Permanent Ineff=
       F       F
Bank Sta=14933,15195.09
XS Rating Curve= 0 ,0
Exp/Cntr=0.3,0.1

Type RM Length L Ch R = 1 ,141890  ,652.55,2664.82,1441.16
BEGIN DESCRIPTION:
LOB - Bois D'Arc
ROB IFA station 22057: flow expansion due to Dallas LID1/2 levee upstream
END DESCRIPTION:
XS GIS Cut Line= 4
2578488.353522786898883.58671344 2568553.35641636890829.58063706
2566718.041022786889165.878380122557641.131300556882425.25338011
#Sta/Elev= 30
       0  402.43 1800.06   361.2 4150.41  341.24 4251.12   354.2  5275.6  363.58
 7039.13  339.56 8196.75  355.43 9176.52  336.19 10438.1  354.3411079.09   338.4
11813.32  364.2312088.64  341.5712149.99  362.9412325.52  367.7812449.91  340.47
12814.72  369.3113108.45  340.7814693.74  352.4914741.93  321.7114782.41  321.12
14860.21  325.1114888.41  352.25   15314  342.1715382.57  365.6215468.64  348.86
22731.81  355.1323416.95  353.1423891.33  379.9925611.27  417.39 26572.7   414.5
#Mann= 10 ,-1 , 0
       0     .07       0 1800.06     .07       0 4251.12     .06       0
 10438.1     .15       014693.74    .055       014888.41     .15       0
15468.64     .05       022731.81     .06       023891.33     .06       0
25611.27     .06       0
Levee=-1,12814.72,369.31,0,,,,
#XS Ineff= 2 , 0
       012814.72     380   22057       0     390
Permanent Ineff=
       F       F
Bank Sta=14693.74,14888.41
XS Rating Curve= 0 ,0
Exp/Cntr=0.3,0.1

Type RM Length L Ch R = 1 ,139225  ,2176.74,2045.8,1473.69
BEGIN DESCRIPTION:
LOB - Bois D'Arc
ROB IFA station 24579: flow expansion due to Dallas LID1/2 levee upstream
END DESCRIPTION:
XS GIS Cut Line= 5
2580054.216385846898561.619567212569420.297967226890896.57282456
2569022.728522786889783.725602332568733.911971856889067.08063706
2559482.337673346881500.95068294
#Sta/Elev= 30
       0  396.08 1759.93  366.06 3551.36  354.94 4412.54  342.38  4582.4  356.97
 4742.74  338.24 5221.17  360.01 6013.33  348.8110441.95  338.8210607.14   354.7
10700.41  337.8110761.86  351.4911552.72  338.9912190.13  354.2212301.86  338.47
 12501.8  358.4812862.34   347.113073.38  369.7213201.59  343.0413618.32  351.66
13764.12  322.2113861.47  325.6113921.57  351.6915260.04  353.3222429.54  354.19
23905.14  397.2425342.24  379.8825395.36  398.8526903.19  409.7527014.43   411.1
#Mann= 10 ,-1 , 0
       0     .07       0 1759.93     .07       0 3551.36      .1       0
 6013.33     .06       012190.13     .15       013618.32    .055       0
13921.57     .15       015260.04     .05       022429.54     .06       0
26903.19     .05       0
Levee=-1,13073.38,369.72,0,,,,
#XS Ineff= 2 , 0
       013073.38     380   24579       0     390
Permanent Ineff=
       F       F
Bank Sta=13618.32,13921.57
XS Rating Curve= 0 ,0
Exp/Cntr=0.3,0.1

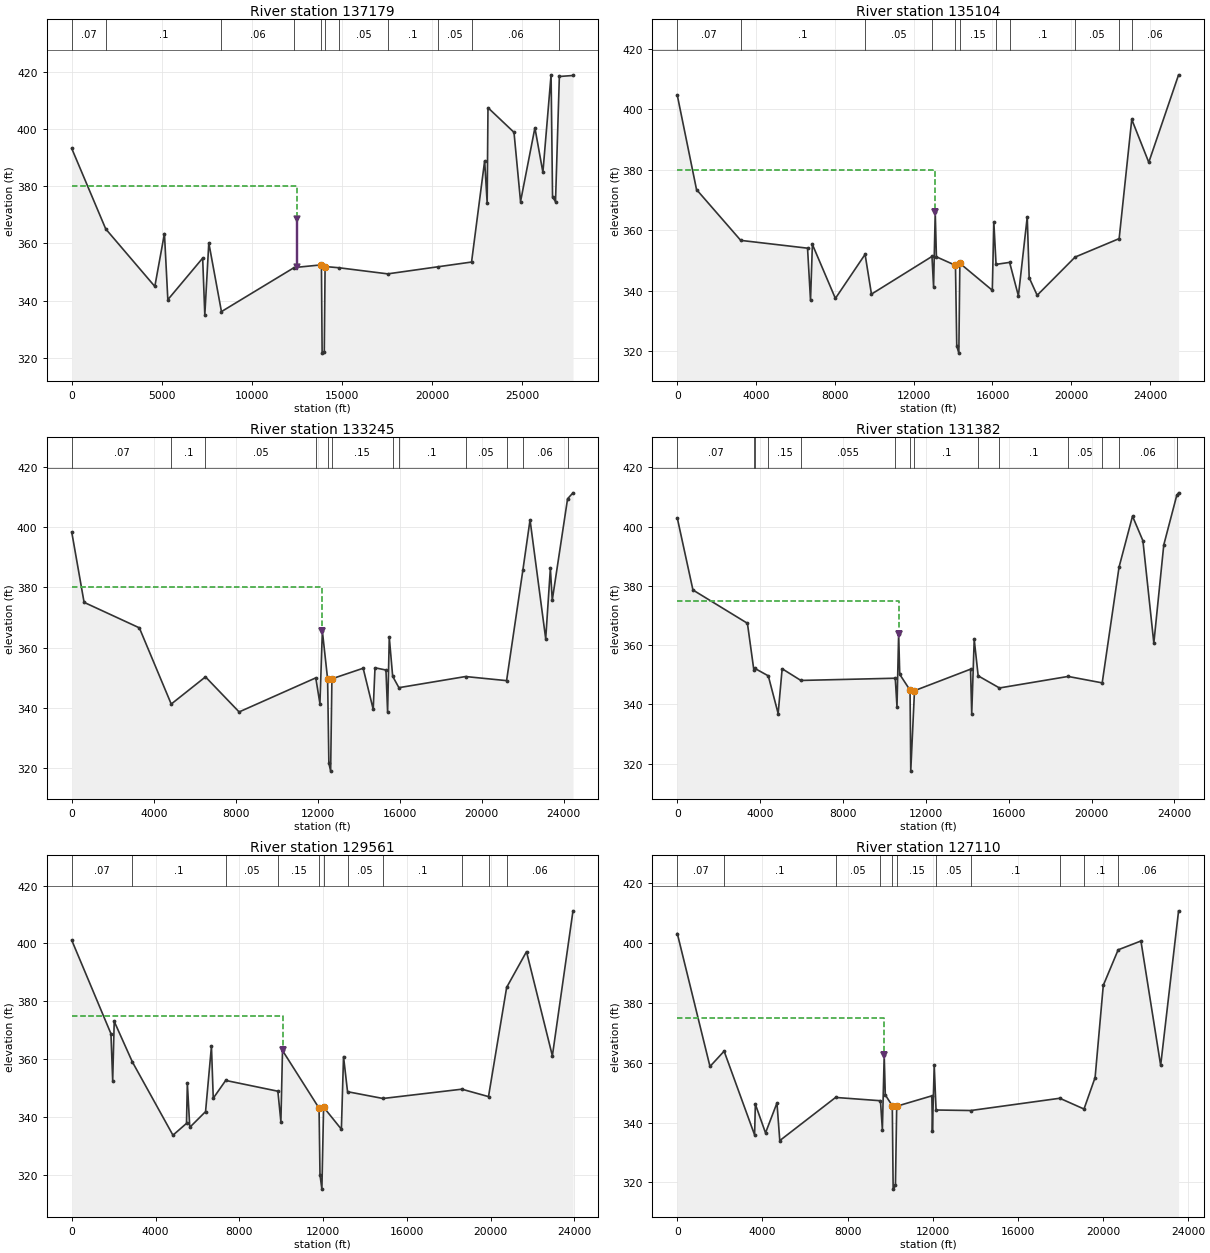
Type RM Length L Ch R = 1 ,137179  ,1988.3,2074.85,2404.85
BEGIN DESCRIPTION:
LOB - Bois D'Arc
ROB IFA station 25644: flow expansion due to Dallas LID1/2 levee upstream
END DESCRIPTION:
XS GIS Cut Line= 2
2581101.955804856897688.613708642559828.689956316879779.65028662
#Sta/Elev= 30
       0  393.14 1885.94  365.03  4609.3  344.95 5143.27   363.4 5331.64  340.32
  7263.9  354.84 7382.41  334.95 7604.47  360.17 8305.71  336.1612339.54  351.54
13851.67  352.4913891.11  321.66 14010.4  322.04 14055.2   351.914829.02  351.47
17529.78  349.3420308.99  351.8122180.46  353.4722907.18  388.8323046.43  374.04
23091.54  407.3724534.58  398.7724898.53  374.5825694.94  400.35 26138.2   384.8
26591.84  418.8526673.43  376.2526837.38  374.5127051.21  418.2727807.95  418.62
#Mann= 11 ,-1 , 0
       0     .07       0 1885.94      .1       0 8305.71     .06       0
12339.54     .15       013851.67    .055       0 14055.2     .15       0
14829.02     .05       017529.78      .1       020308.99     .05       0
22180.46     .06       027051.21     .05       0
Levee=-1,12479.5,368.33,0,,,,
#XS Ineff= 2 , 0
       0 12479.5     380   25644       0     390
Permanent Ineff=
       F       F
Bank Sta=13851.67,14055.2
XS Rating Curve= 0 ,0
Exp/Cntr=0.3,0.1

Type RM Length L Ch R = 1 ,135104  ,1573.64,1859.49,1698.1
BEGIN DESCRIPTION:
LOB - Bois D'Arc
END DESCRIPTION:
XS GIS Cut Line= 4
 2582536.83044336896710.411491352572529.409657046888196.18943335
2571674.374934826886894.974155572563718.53002741 6879660.5412852
#Sta/Elev= 30
       0  404.66  975.72  373.49 3219.69  356.68 6611.98   354.1 6763.34  336.82
 6858.08  355.34 8025.49  337.48 9533.62  352.06 9856.99   338.912929.63  351.36
13010.82  341.3113094.66  366.0913154.63  351.2414122.17  348.4214187.93  321.73
14293.16  319.3814345.25  349.1115992.55  340.1716070.54   362.716182.41  348.74
16871.52   349.417316.75  338.3417766.38  364.4717864.29  344.3418269.85  338.52
20196.52  351.1622432.12  357.2623072.47   396.723936.33   382.525449.53  411.45
#Mann= 11 ,-1 , 0
       0     .07       0 3219.69      .1       0 9533.62     .05       0
12929.63     .15       014122.17    .055       014345.25     .15       0
16182.41     .05       016871.52      .1       020196.52     .05       0
22432.12     .06       023072.47     .06       0
Levee=-1,13094.66,366.09,0,,,,
#XS Ineff= 2 , 0
       013094.66     380               0
Permanent Ineff=
       F       F
Bank Sta=14122.17,14345.25
XS Rating Curve= 0 ,0
Exp/Cntr=0.3,0.1

Type RM Length L Ch R = 1 ,133245  ,1421.06,1862.89,859.67
BEGIN DESCRIPTION:
LOB - Bois D'Arc
END DESCRIPTION:
XS GIS Cut Line= 4
2583349.971217766895215.749990182573768.877249636887647.78086853
2573663.182805196886553.753090752565391.637884436879090.74999018
#Sta/Elev= 30
       0  398.35   602.8  375.05  3297.8   366.6 4852.94  341.34 6522.78  350.35
  8164.1  338.7311903.46  350.0212105.59  341.4712224.68  365.5512480.25  349.65
12541.74  321.7812628.18  319.1112690.26  349.7114214.83  353.2114704.48  339.59
14791.81  353.3615326.07  352.62 15406.5  338.6415488.41  363.4615653.89  350.54
15958.05  346.7719208.68  350.4621210.16   349.122006.64  385.8322354.15  402.38
 23118.1  362.9723345.48   386.323437.44  375.7524184.88  409.3824449.29  411.35
#Mann= 12 ,-1 , 0
       0     .07       0 4852.94      .1       0 6522.78     .05       0
11903.46     .15       012480.25    .055       012690.26     .15       0
15653.89     .05       015958.05      .1       019208.68     .05       0
21210.16      .1       022006.64     .06       024184.88     .05       0
Levee=-1,12224.68,365.55,0,,,,
#XS Ineff= 2 , 0
       012224.68     380               0
Permanent Ineff=
       F       F
Bank Sta=12480.25,12690.26
XS Rating Curve= 0 ,0
Exp/Cntr=0.3,0.1

Type RM Length L Ch R = 1 ,131382  ,1497.01,1820.98,1004.37
BEGIN DESCRIPTION:
LOB - Bois D'Arc
END DESCRIPTION:
XS GIS Cut Line= 4
2584317.349471856894327.364201862575937.488360746887689.86420186
2575304.155027416886867.64197964 2565867.59982616878713.40774316
#Sta/Elev= 30
       0  402.91  754.96  378.64 3384.72   367.4 3691.95   351.8 3726.55  352.24
 4392.35  349.66 4867.98  336.94  5061.3  352.06 5964.83  348.11 10522.3  348.86
 10605.5  339.1910685.22  363.9510738.01  350.1611235.91  344.8311269.98   317.5
11450.27  344.6514155.48  351.91 14213.2  336.8814333.52  361.9514524.14  349.67
15552.36  345.57 18867.2  349.4620512.32  347.2921326.36  386.3821975.55  403.56
22477.45  395.2823005.03  360.7223485.15  393.8724110.71  410.5624199.55  411.44
#Mann= 14 ,-1 , 0
       0     .07       0 3691.95      .1       0 3726.55     .07       0
 4392.35     .15       0 5964.83    .055       0 10522.3     .15       0
11235.91    .055       011450.27      .1       014524.14     .05       0
15552.36      .1       0 18867.2     .05       020512.32      .1       0
21326.36     .06       024110.71     .05       0
Levee=-1,10685.22,363.95,0,,,,
#XS Ineff= 2 , 0
       010685.22     375               0
Permanent Ineff=
       F       F
Bank Sta=11235.91,11450.27
XS Rating Curve= 0 ,0
Exp/Cntr=0.3,0.1

Type RM Length L Ch R = 1 ,129561  ,712.19,2450.97,1729.68
BEGIN DESCRIPTION:
LOB - Bois D'Arc
END DESCRIPTION:
XS GIS Cut Line= 5
2584901.377249636892811.391979632576986.909657046886702.86188705
2576359.13187926 6885420.91744262575429.270768156885568.83410927
2566232.183159436878557.15774316
#Sta/Elev= 30
       0  401.13 1872.04  368.87 1955.56  352.69 2028.68  373.11 2893.87  359.14
 4832.74  333.84 5479.59  337.92 5519.86  351.82 5635.94  336.55  6389.1  341.98
 6670.49  364.54 6757.04   346.6  7350.2  352.74 9841.16  349.02 9985.82  338.51
10062.62  363.0711808.27  343.1711852.09  320.22 11943.3  315.23 12024.1  343.53
12874.15  335.8912976.12  360.9713167.68  348.8514860.51  346.5118624.95  349.72
19897.79  347.1620764.35  384.8521712.11  397.1922946.95  361.2223931.62  411.27
#Mann= 11 ,-1 , 0
       0     .07       0 2893.87      .1       0  7350.2     .05       0
 9841.16     .15       011808.27    .055       0 12024.1     .15       0
13167.68     .05       014860.51      .1       018624.95     .05       0
19897.79      .1       020764.35     .06       0
Levee=-1,10062.62,363.07,0,,,,
#XS Ineff= 2 , 0
       010062.62     375               0
Permanent Ineff=
       F       F
Bank Sta=11808.27,12024.1
XS Rating Curve= 0 ,0
Exp/Cntr=0.3,0.1

Type RM Length L Ch R = 1 ,127110  ,1790.05,2113.72,648.82
BEGIN DESCRIPTION:
LOB - Bois D'Arc
END DESCRIPTION:
XS GIS Cut Line= 5
2585217.20479592 6891834.55748892577327.50572185 6886159.7600352
2577136.649240376885103.446377792576497.76035148 6884058.3074889
2566562.044270546878209.93552094
#Sta/Elev= 30
       0  403.21 1534.94  358.75 2198.55  363.88 3630.38  335.86 3665.79  346.14
 4143.58  336.54 4681.18  346.55 4813.25  333.97 7434.72   348.4 9542.72   347.3
  9632.6  337.64 9718.61  362.54 9769.52  349.2510098.13  345.6210139.04  317.74
10246.55  318.9810305.39  345.4611956.64  348.9411983.88   337.112068.25  359.18
12153.81   344.213789.35  344.0317966.64  348.1319103.62  344.5319625.18  355.07
20009.36  385.8920708.11  397.7721777.79  400.7222704.35  359.1223546.05  410.81
#Mann= 11 ,-1 , 0
       0     .07       0 2198.55      .1       0 7434.72     .05       0
 9542.72     .15       010098.13    .055       010305.39     .15       0
12153.81     .05       013789.35      .1       017966.64     .05       0
19103.62      .1       020708.11     .06       0
Levee=-1,9718.61,362.54,0,,,,
#XS Ineff= 2 , 0
       0 9718.61     375               0
Permanent Ineff=
       F       F
Bank Sta=10098.13,10305.39
XS Rating Curve= 0 ,0
Exp/Cntr=0.3,0.1

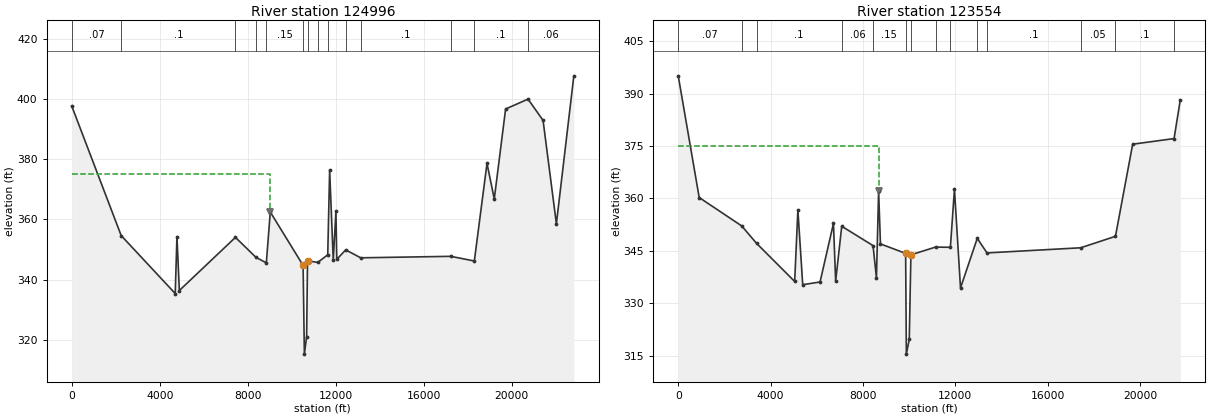
Type RM Length L Ch R = 1 ,124996  ,778.22,1442.73,1331.79
BEGIN DESCRIPTION:
LOB - Bois D'Arc
END DESCRIPTION:
XS GIS Cut Line= 4
2585394.264981116890775.946377792578735.931647786884706.50193334
2576979.681647776883608.585266682566700.933159436877932.15774316
#Sta/Elev= 30
       0  397.63 2246.66  354.63 4703.32  335.38 4780.89  354.32 4889.73  336.39
 7439.97  354.04 8370.86  347.41 8843.92  345.57 9024.18  362.4510515.38  344.73
10573.38  315.2610675.89  321.0910716.75  346.2511183.85  345.72 11635.3  348.25
11722.04  376.3411886.44  346.5212008.34  362.7912045.16  346.7412453.64  349.88
13134.25  347.2517225.42  347.7418299.05  346.1918875.03  378.5919205.62   366.8
19720.69  396.6720740.13  399.9621423.72  392.8822028.93  358.5722822.69  407.69
#Mann= 14 ,-1 , 0
       0     .07       0 2246.66      .1       0 7439.97     .06       0
 8370.86     .05       0 8843.92     .15       010515.38    .055       0
10716.75     .15       011183.85     .05       0 11635.3      .1       0
12453.64     .05       013134.25      .1       017225.42     .05       0
18299.05      .1       020740.13     .06       0
Levee=-1,9024.18,362.44,0,,,,
#XS Ineff= 2 , 0
       0 9024.18     375               0
Permanent Ineff=
       F       F
Bank Sta=10515.38,10716.75
XS Rating Curve= 0 ,0
Exp/Cntr=0.3,0.1

Type RM Length L Ch R = 1 ,123554  ,223.62,1398.9,1040.15
BEGIN DESCRIPTION:
LOB - Bois D'Arc
END DESCRIPTION:
XS GIS Cut Line= 4
2585509.000037216890498.497733262579526.932805186884187.75193334
2577877.627249636882534.974155562568228.710937216877862.71329872
#Sta/Elev= 30
       0  395.08  907.75  360.27 2748.21  352.15 3397.43  347.13 5044.32  336.26
 5183.41   356.7 5393.26  335.33  6143.7  336.11 6724.73  352.85 6819.31  336.34
 7083.41  352.05 8438.49  346.51 8586.94   337.3 8680.47  362.07 8760.93     347
 9851.44  344.29  9882.4  315.4710008.54   319.710079.93  343.8811146.16  346.09
11790.33  346.0311965.99  362.6212228.57   334.412954.43  348.5813375.61  344.42
17435.15  345.8918941.52  349.1719687.33  375.5221480.53  377.1321750.92  388.22
#Mann= 14 ,-1 , 0
       0     .07       0 2748.21     .06       0 3397.43      .1       0
 7083.41     .06       0 8438.49     .15       0 9851.44    .055       0
10079.93     .15       011146.16     .05       011790.33      .1       0
12954.43     .05       013375.61      .1       017435.15     .05       0
18941.52      .1       021480.53     .06       0
Levee=-1,8680.47,362.07,0,,,,
#XS Ineff= 2 , 0
       0 8680.47     375               0
Permanent Ineff=
       F       F
Bank Sta=9851.44,10079.93
XS Rating Curve= 0 ,0
Exp/Cntr=0.3,0.1