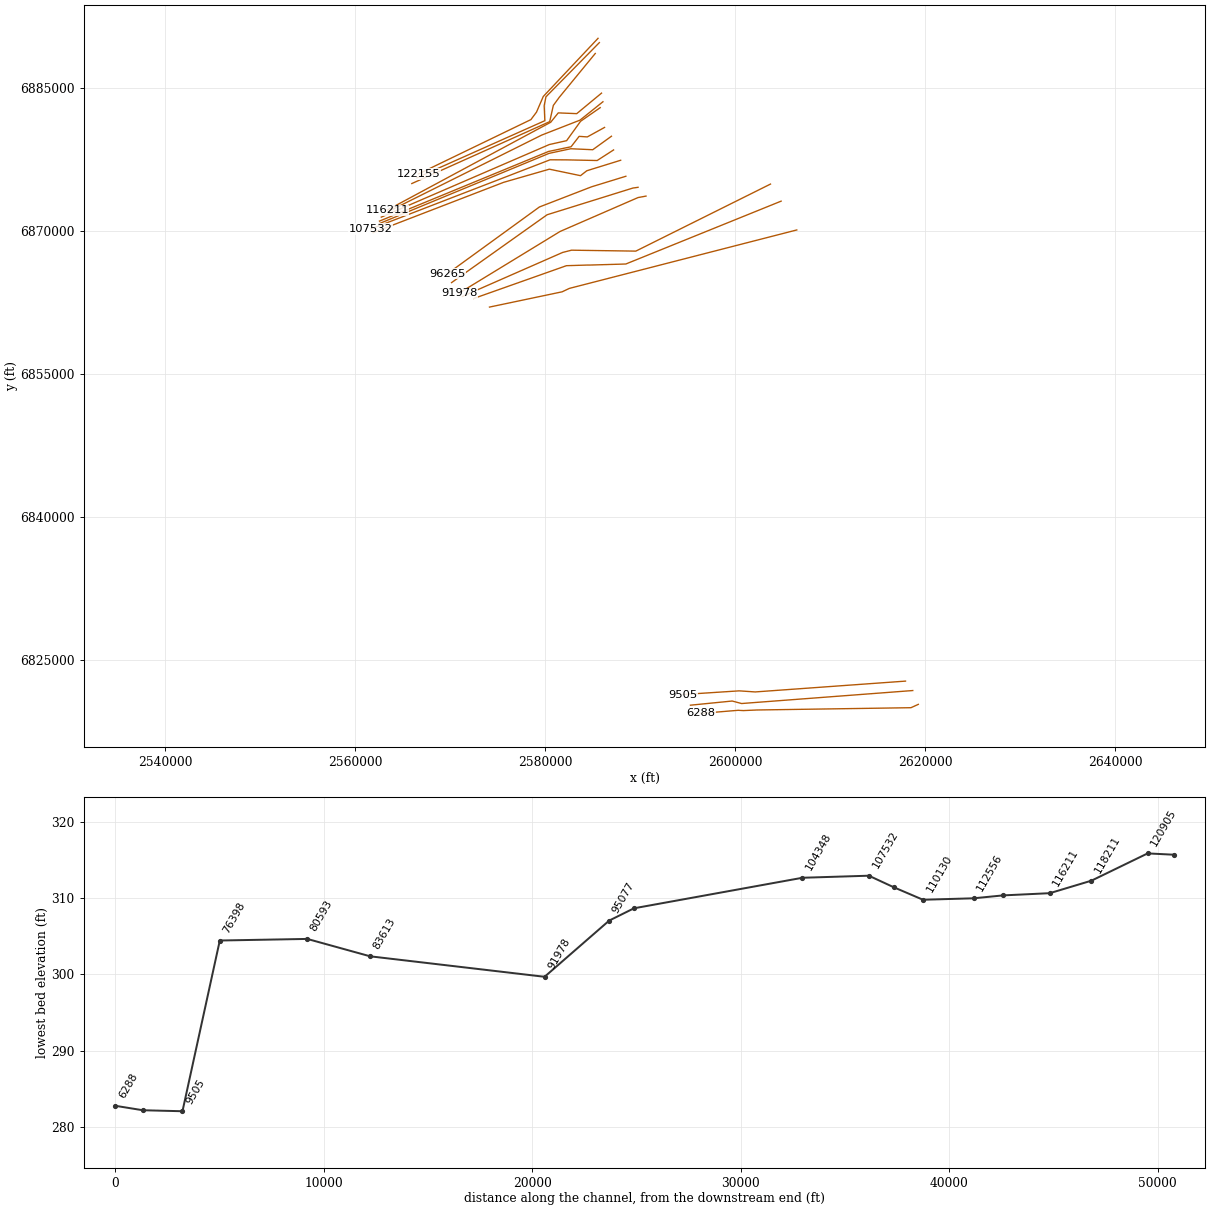
HEC-RAS study TR_FEMA.prj: Trinity_River_FEMA

--- TR_FEMA.g06 (geometry) --- (continued)

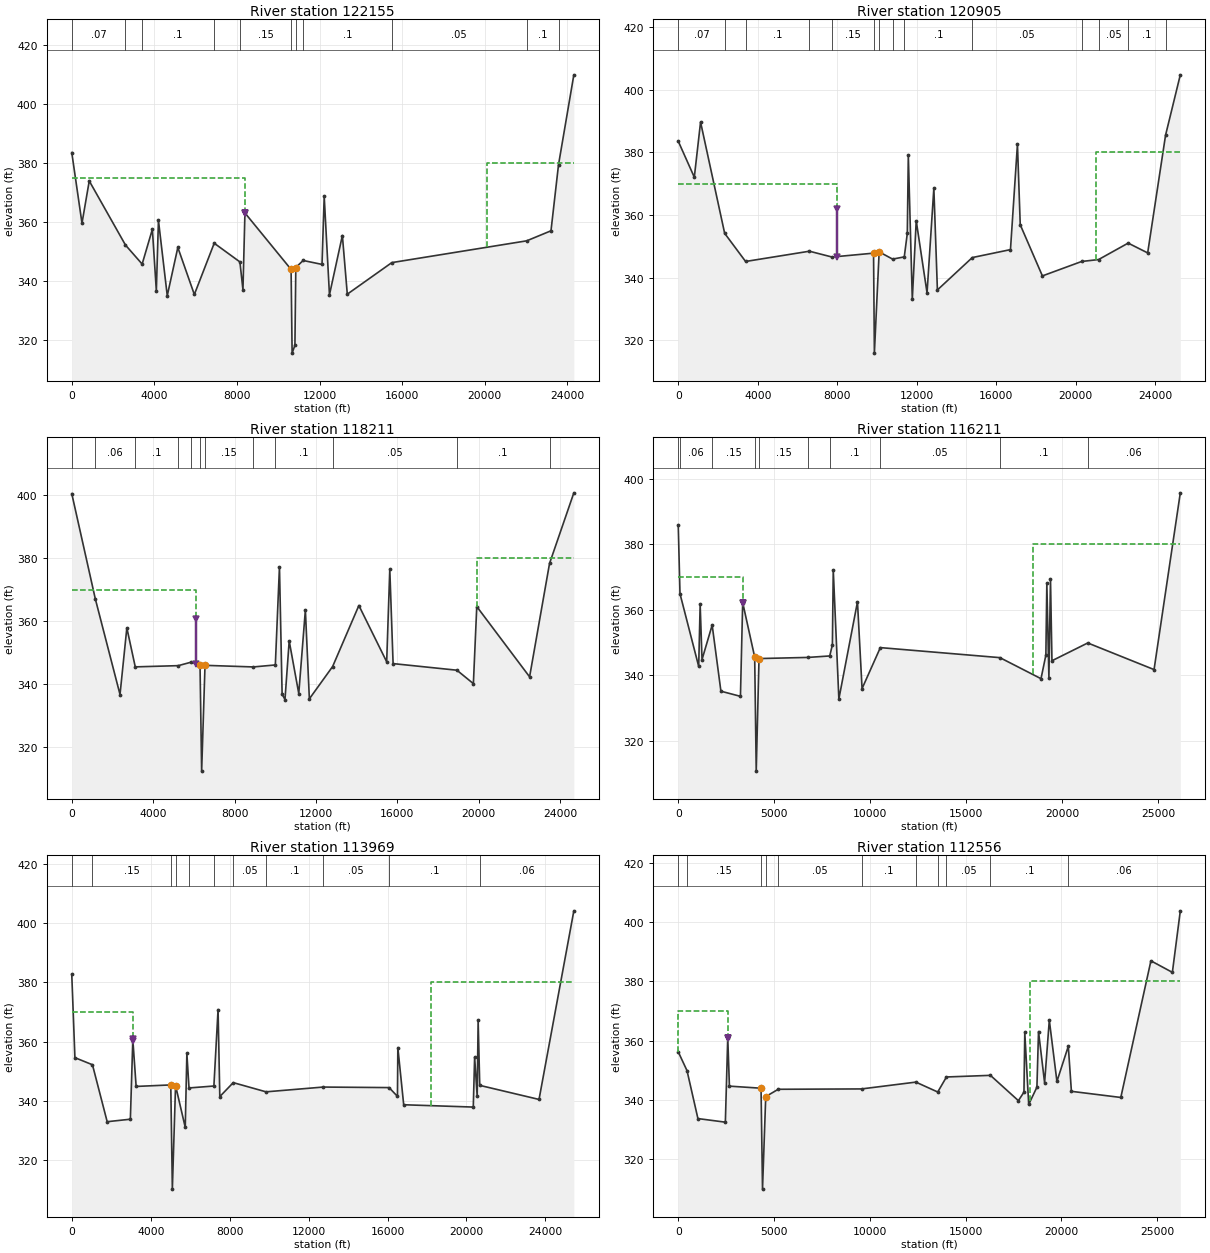
Type RM Length L Ch R = 1 ,122155  ,264.7,1249.35,675.81
BEGIN DESCRIPTION:
LOB - Bois D'Arc
ROB IFA station 20096: flow expansion due to natural high ground upstream
END DESCRIPTION:
XS GIS Cut Line= 5
2585574.994147786890261.849155572579808.489518156884154.81211854
2579098.767295936882514.534340762578508.489518156881729.81211854
2566666.210937216876022.43552094
#Sta/Elev= 30
       0  383.65  494.88  359.71  846.43  374.04 2600.82  352.31 3408.26  345.86
 3903.21  357.65 4095.35  336.83 4197.44  360.67  4624.4  335.14  5136.3   351.5
 5935.95  335.55 6898.27  352.93 8142.87  346.59 8289.74  337.15 8385.98  363.19
10621.02  344.0510670.96  315.6810806.46  318.3410849.79   344.711204.51  347.08
12118.58  345.7512224.99  368.7712479.21  335.4413104.59  355.5413343.22  335.66
15499.24  346.3622031.38  353.7423207.33  357.14 23572.3  379.5424314.35     410
#Mann= 11 ,-1 , 0
       0     .07       0 2600.82     .06       0 3408.26      .1       0
 6898.27     .06       0 8142.87     .15       010621.02    .055       0
10849.79     .15       011204.51      .1       015499.24     .05       0
22031.38      .1       0 23572.3     .06       0
Levee=-1,8385.98,363.19,0,,,,
#XS Ineff= 3 ,-1
       0 8385.98     375                           2009624314.35     380
Permanent Ineff=
       F       F       F
Bank Sta=10621.02,10849.79
XS Rating Curve= 0 ,0
Exp/Cntr=0.3,0.1

Type RM Length L Ch R = 1 ,120905  ,976.82,2694.7,313.19
BEGIN DESCRIPTION:
LOB - Bois D'Arc
ROB IFA station 21033: flow expansion due to natural high ground upstream
END DESCRIPTION:
XS GIS Cut Line= 5
2585714.392295936889812.555174092580091.614518156884120.88850743
2579906.058962596883189.013507422579976.886508896881615.51235001
2566509.960937216875623.12996538
#Sta/Elev= 30
       0  383.56  808.93  372.05 1123.59  389.67 2336.29  354.12 3389.41  345.13
 6601.08  348.41 7738.89  346.55 9828.58  347.79 9870.55  315.8510110.79   348.2
10786.36  345.8911374.55  346.5911527.09   354.111578.13  379.0811778.86  333.04
11975.94  358.1412520.65  335.1112863.31  368.5313041.78  336.0314797.73  346.38
16718.92  348.9217069.88  382.5617210.52  356.8618325.61  340.5220301.79  345.13
 21151.2  345.7422641.51     35123623.41  347.87 24524.3  385.4925265.88  404.76
#Mann= 14 ,-1 , 0
       0     .07       0 2336.29     .06       0 3389.41      .1       0
 6601.08     .06       0 7738.89     .15       0 9828.58    .055       0
10110.79     .15       010786.36     .05       011374.55      .1       0
14797.73     .05       020301.79      .1       0 21151.2     .05       0
22641.51      .1       0 24524.3     .06       0
Levee=-1,8005.69,361.93,0,,,,
#XS Ineff= 3 ,-1
       0 8005.69     370                           2103325265.88     380
Permanent Ineff=
       F       F       F
Bank Sta=9828.58,10110.79
XS Rating Curve= 0 ,0
Exp/Cntr=0.3,0.1

Type RM Length L Ch R = 1 ,118211  ,2761.13,1999.76,334.75
BEGIN DESCRIPTION:
LOB - Bois D'Arc
ROB IFA station 19915: flow expansion due to natural high ground upstream
END DESCRIPTION:
XS GIS Cut Line= 5
2585283.489518156888671.588738912581496.568221856884073.32485001
2580869.947851486883221.472998162580486.151555196881514.99151668
2565971.766492776875015.49107649
#Sta/Elev= 30
       0  400.54 1155.44   367.1 2369.85  336.65 2705.98  357.83 3119.07  345.44
  5232.5  345.83    5850  346.91 6300.75  345.99 6380.81  312.28 6546.02  345.93
 8921.03  345.42 10001.1  346.0510203.83  377.2710334.41  336.7610474.72  335.05
10681.82   353.711152.35  336.9611476.65  363.5511672.77  335.2712815.94  345.55
14105.39  364.9615471.42  347.0615624.14  376.4715786.65  346.4818921.67  344.38
19730.73  340.11 19897.3  364.6322492.53  342.2723472.56  378.3424666.69   400.8
#Mann= 12 ,-1 , 0
       0     .07       0 1155.44     .06       0 3119.07      .1       0
  5232.5     .06       0    5850     .15       0 6300.75    .055       0
 6546.02     .15       0 8921.03     .05       0 10001.1      .1       0
12815.94     .05       018921.67      .1       023472.56     .06       0
Levee=-1,6113.49,360.77,0,,,,
#XS Ineff= 3 ,-1
       0 6090.96     370                           1991524666.69     380
Permanent Ineff=
       F       F       F
Bank Sta=6300.75,6546.02
XS Rating Curve= 0 ,0
Exp/Cntr=0.3,0.1

Type RM Length L Ch R = 1 ,116211  ,785.21,2241.73,739.29
BEGIN DESCRIPTION:
LOB - Bois D'Arc
ROB IFA station 18461: flow expansion due to natural high ground upstream
END DESCRIPTION:
XS GIS Cut Line= 5
     2585944.032     6884510.862     2583333.374     6882355.269
     2581389.228     6882435.162     2580590.329     6881450.457
       2563367.6     6872220.352
#Sta/Elev= 30
       0  385.96   91.21  364.89 1065.04  342.66 1141.18  361.61 1238.75  344.76
 1766.31   355.3 2221.93  335.08 3238.73  333.51  3355.6  362.19 3980.32  345.52
 4060.59  310.64 4205.73  345.06    6757  345.41  7887.7  345.86 8025.89  349.25
 8071.31  372.13 8363.02   332.7 9331.79   362.4 9570.76  335.8810522.81  348.41
   16749  345.3418887.42  338.9119140.57   346.119191.16  368.1219299.06  339.21
19381.64  369.3819457.52  344.3921321.25  349.8324773.52  341.6926140.52  395.74
#Mann= 10 ,-1 , 0
       0     .06       0   91.21     .06       0 1766.31     .15       0
 3980.32    .055       0 4205.73     .15       0    6757     .05       0
  7887.7      .1       010522.81     .05       0   16749      .1       0
21321.25     .06       0
Levee=-1,3355.6,362.19,0,,,,
#XS Ineff= 3 ,-1
       0  3355.6     370                           1846126140.52     380
Permanent Ineff=
       F       F       F
Bank Sta=3980.32,4205.73
XS Rating Curve= 0 ,0
Exp/Cntr=0.3,0.1

Type RM Length L Ch R = 1 ,113969  ,147.93,1413.33,1346.26
BEGIN DESCRIPTION:
LOB - Bois D'Arc
ROB IFA station 18189: flow expansion due to natural high ground upstream
END DESCRIPTION:
XS GIS Cut Line= 4
     2586091.755     6883602.693      2583678.94     6881674.698
     2579642.858     6880103.664     2563506.489     6872081.463
#Sta/Elev= 30
       0  382.66   159.6  354.63  1048.5  352.24 1794.21  333.06 2969.13   333.9
  3093.5  360.77 3261.33  344.94 5016.81  345.45 5096.83  310.35 5258.88  345.24
 5750.62  331.14 5831.83  356.07  5940.4  344.43 7201.38  345.08 7412.86  370.84
 7501.14  341.52 8182.78  346.22 9844.37  343.1212740.14  344.7316078.38  344.55
16502.85   341.616522.41  358.0216819.29  338.7720344.84  337.9920413.57  354.79
 20542.7   341.620591.31  367.2820672.55   345.323676.91  340.5625440.86  404.09
#Mann= 11 ,-1 , 0
       0     .06       0  1048.5     .15       0 5016.81    .055       0
 5258.88     .15       0  5940.4     .05       0 7201.38      .1       0
 8182.78     .05       0 9844.37      .1       012740.14     .05       0
16078.38      .1       020672.55     .06       0
Levee=-1,3098.5,360.77,0,,,,
#XS Ineff= 3 ,-1
       0  3098.5     370                           1818925440.86     380
Permanent Ineff=
       F       F       F
Bank Sta=5016.81,5258.88
XS Rating Curve= 0 ,0
Exp/Cntr=0.3,0.1

Type RM Length L Ch R = 1 ,112556  ,1808.05,2425.98,739.38
BEGIN DESCRIPTION:
LOB - Bois D'Arc
ROB IFA station 18373: flow expansion due to natural high ground upstream
END DESCRIPTION:
XS GIS Cut Line= 5
       2585804.9     6882984.953     2583737.924     6881552.473
     2582268.896     6879518.792     2580440.598     6879109.695
     2562759.961     6871491.186
#Sta/Elev= 30
       0  356.27   458.5  349.92 1027.81  333.76 2459.89  332.55 2584.82  361.08
 2671.59   344.7 4322.59     344 4399.32  309.97 4567.55  341.17 5218.84  343.64
 9568.96  343.7612403.64  346.0613546.54  342.7214001.42  347.7916296.95  348.34
17757.01   339.818047.48  342.6918090.18  362.7918294.91  338.5318723.42  344.35
18807.48  363.1219124.28  345.8519370.51  366.9519768.17  346.2920362.28  358.15
20523.92  342.9523102.89  340.8824674.92  386.9625794.75  383.0726209.19  403.82
#Mann= 11 ,-1 , 0
       0     .06       0   458.5     .15       0 4322.59    .055       0
 4567.55     .15       0 5218.84     .05       0 9568.96      .1       0
12403.64     .05       013546.54      .1       014001.42     .05       0
16296.95      .1       020362.28     .06       0
Levee=-1,2584.82,361.08,0,,,,
#XS Ineff= 3 ,-1
       0 2584.82     370                           1837326209.19     380
Permanent Ineff=
       F       F       F
Bank Sta=4322.59,4567.55
XS Rating Curve= 0 ,0
Exp/Cntr=0.3,0.1

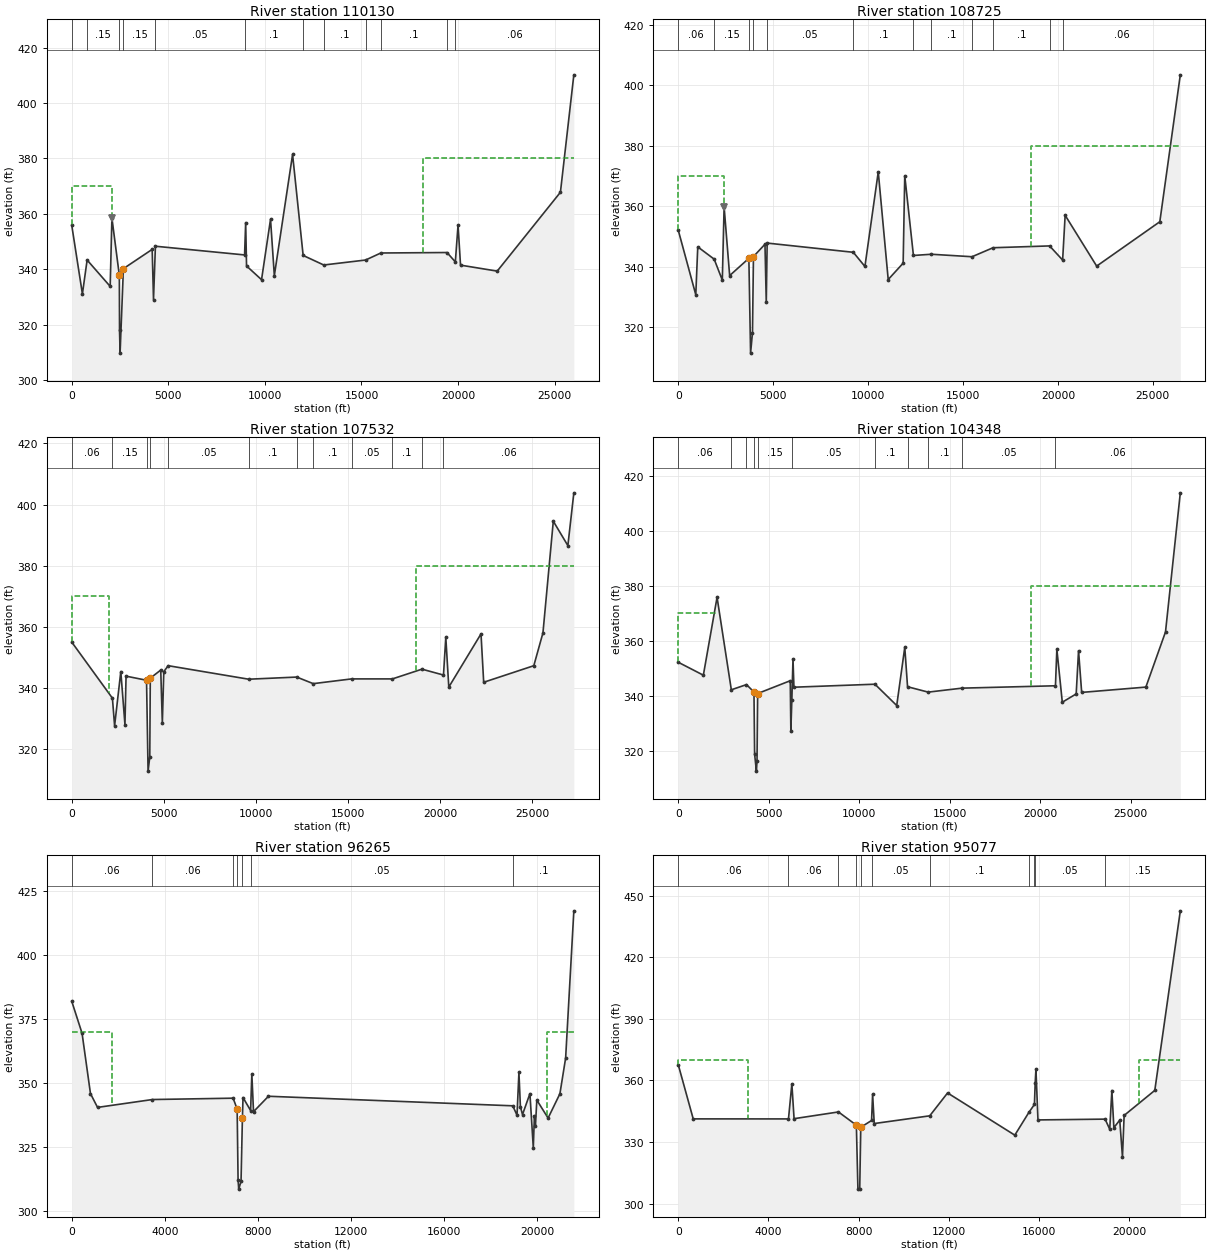
Type RM Length L Ch R = 1 ,110130  ,1466.65,1404.73,264.23
BEGIN DESCRIPTION:
LOB - Bois D'Arc
ROB IFA station 18172: flow expansion due to natural high ground upstream
END DESCRIPTION:
XS GIS Cut Line= 6
     2586262.889     6880907.974     2584444.605     6879911.516
     2583586.604     6879971.917     2582737.646     6878879.903
      2580370.91       6878386.5     2562568.989     6871074.519
#Sta/Elev= 30
       0  355.84  550.58  331.14  795.01  343.36 1988.81  333.85 2078.42   358.5
 2462.45  337.85 2472.91  318.02 2501.58  309.78 2673.18  340.25 4162.76   347.2
 4231.97   329.1 4330.13  348.34 8947.24   345.2 9003.47  356.86 9048.75  341.22
 9825.57  336.2710290.49  358.0610487.69  337.7411432.32  381.4411979.33  345.02
13046.22  341.5715210.35  343.3616001.13   345.919427.69  346.0719858.94  342.69
19999.03  355.9420127.81  341.5222026.83  339.3625299.58  367.8125994.54  410.17
#Mann= 12 ,-1 , 0
       0     .06       0  795.01     .15       0 2462.45    .055       0
 2673.18     .15       0 4330.13     .05       0 8947.24      .1       0
11979.33     .05       013046.22      .1       015210.35     .05       0
16001.13      .1       019427.69     .05       019858.94     .06       0
Levee=-1,2078.42,358.5,0,,,,
#XS Ineff= 3 ,-1
       0 2078.42     370                           1817225994.54     380
Permanent Ineff=
       F       F       F
Bank Sta=2462.45,2673.18
XS Rating Curve= 0 ,0
Exp/Cntr=0.3,0.1

Type RM Length L Ch R = 1 ,108725  ,1186.89,1193.33,695.83
BEGIN DESCRIPTION:
LOB - Bois D'Arc
ROB IFA station 18591: flow expansion due to natural high ground upstream
END DESCRIPTION:
XS GIS Cut Line= 5
     2586988.651     6879984.728     2585018.827      6878567.75
     2582706.327     6878671.917     2580424.382     6878185.459
     2562516.905     6870796.741
#Sta/Elev= 30
       0  352.13  924.84  330.74 1028.29  346.59 1893.33  342.52    2322  335.58
 2416.54  359.83  2708.8  337.08 3721.05  342.79  3811.2  311.42 3911.73  318.19
 3962.76  343.37 4569.42  347.46 4637.55  328.23 4684.98  347.84 9222.72  344.79
 9834.86   340.110537.58  371.4111061.39  335.7811848.95  341.1911932.97  370.14
 12390.1  343.7413336.15  344.1415477.19  343.3216586.04   346.319563.45   346.9
20250.32  342.2220382.85  357.0322043.72  340.2225369.97   354.926449.92  403.52
#Mann= 12 ,-1 , 0
       0     .06       0 1893.33     .15       0 3721.05    .055       0
 3962.76     .15       0 4684.98     .05       0 9222.72      .1       0
 12390.1     .05       013336.15      .1       015477.19     .05       0
16586.04      .1       019563.45     .05       020250.32     .06       0
Levee=-1,2416.54,359.83,0,,,,
#XS Ineff= 3 ,-1
       0 2416.54     370                           1859126449.92     380
Permanent Ineff=
       F       F       F
Bank Sta=3721.05,3962.76
XS Rating Curve= 0 ,0
Exp/Cntr=0.3,0.1

Type RM Length L Ch R = 1 ,107532  ,1037.27,3183.75,659.24
BEGIN DESCRIPTION:
LOB IFA station 2008: flow expansion due to Bois D'Arc levee upstream
ROB IFA station 18676: flow expansion due to natural high ground upstream
END DESCRIPTION:
XS GIS Cut Line= 5
     2587214.015     6878546.995     2585482.484     6877434.648
     2582272.183     6877502.519     2580529.243     6877510.806
      2561648.85     6870241.186
#Sta/Elev= 30
       0  355.06  2206.6  336.75 2324.95  327.73 2661.98  345.45 2886.92  328.11
 2946.88  343.95 4058.67  342.61 4141.97  312.93 4234.63  317.57 4262.58  343.29
 4830.06  345.94 4916.76   328.6  4995.3  345.38 5229.58  347.37 9602.06  342.95
12212.69  343.6513108.48   341.515191.19  343.0517405.58  343.05 19010.2  346.23
20178.41  344.3120304.07  356.6320466.76  340.3822215.42  357.75 22361.1  341.95
25081.37  347.3625577.96  358.0826139.72  394.5526930.64  386.5827255.17  403.82
#Mann= 12 ,-1 , 0
       0     .06       0  2206.6     .15       0 4058.67    .055       0
 4262.58     .15       0 5229.58     .05       0 9602.06      .1       0
12212.69     .05       013108.48      .1       015191.19     .05       0
17405.58      .1       0 19010.2     .05       020178.41     .06       0
#XS Ineff= 3 ,-1
       0    2008     370                           1867627255.17     380
Permanent Ineff=
       F       F       F
Bank Sta=4058.67,4262.58
XS Rating Curve= 0 ,0
Exp/Cntr=0.3,0.1

Type RM Length L Ch R = 1 ,104348  ,1720.81,8083.46,4276.21
BEGIN DESCRIPTION:
LOB IFA station 2091: flow blocked at natural high ground
ROB IFA station 19491: flow expansion due to natural high ground upstream
END DESCRIPTION:
XS GIS Cut Line= 6
     2587959.751      6877462.12     2584395.378     6876361.093
      2583731.07     6875844.172     2580450.933     6876525.908
      2575638.85     6875144.808     2561891.905     6869859.241
#Sta/Elev= 30
       0  352.26 1387.58  347.55 2144.66  375.87 2932.52  342.24 3769.51  344.13
  4183.4  341.42 4218.77  318.86 4317.71  312.66 4351.15  316.23 4386.78  340.88
 6187.54  345.54 6220.33  327.42 6275.76  338.64 6339.09  353.48 6389.68  343.18
 10865.3  344.2712068.66  336.5212513.24   357.712666.27  343.3513806.08  341.39
15676.84  342.8420836.46   343.720913.16  356.9821214.51  337.7221981.43  340.74
22111.55  356.4622284.05  341.2925829.78  343.2226914.69  363.28 27732.7  413.87
#Mann= 11 ,-1 , 0
       0     .06       0 2932.52     .06       0 3769.51     .15       0
  4183.4    .055       0 4386.78     .15       0 6275.76     .05       0
 10865.3      .1       012666.27     .05       013806.08      .1       0
15676.84     .05       020836.46     .06       0
#XS Ineff= 3 ,-1
       0    2091     370                           19491 27732.7     380
Permanent Ineff=
       F       F       F
Bank Sta=4183.4,4386.78
XS Rating Curve= 0 ,0
Exp/Cntr=0.3,0.1

Type RM Length L Ch R = 1 ,96265   ,1483.83,1188.02,1196.23
BEGIN DESCRIPTION:
ROB IFA station 20423: flow contraction due to Ellis LID2 levee downstream
END DESCRIPTION:
XS GIS Cut Line= 4
     2588505.007     6875781.772     2584879.573     6874669.972
     2579399.972     6872554.087     2569704.405     6865536.324
#Sta/Elev= 30
       0  381.97  442.56   369.5  803.83  345.96 1107.88  340.57 3464.47  343.64
 6936.88  344.17  7109.5  339.88 7148.95  312.28 7177.18  308.66 7276.27  311.65
 7335.69  336.59  7361.7  344.42 7687.49  339.35 7740.77  353.59  7812.9  338.89
 8454.78  344.9218958.26  341.1919139.77  337.5119221.88   354.219285.88  340.82
19375.95  337.7819694.72  345.9419839.85  324.8419888.09  337.3519931.03  333.18
19991.59  343.4320475.66   336.420983.95   345.921230.28  359.8721582.92  417.32
#Mann= 7 ,-1 , 0
       0     .06       0 3464.47     .06       0 6936.88     .15       0
  7109.5    .055       0 7335.69     .15       0 7687.49     .05       0
18958.26      .1       0
#XS Ineff= 2 , 0
       0    1717     370   20423       0     370
Permanent Ineff=
       F       F
Bank Sta=7109.5,7335.69
XS Rating Curve= 0 ,0
Exp/Cntr=0.3,0.1

Type RM Length L Ch R = 1 ,95077   ,1759.01,3098.93,2125.14
BEGIN DESCRIPTION:
ROB IFA station 20406: flow contraction due to Ellis LID2 levee downstream
END DESCRIPTION:
XS GIS Cut Line= 4
     2589788.177     6874622.495     2589245.262     6874544.293
     2580213.774     6871740.284     2570155.794     6864616.186
#Sta/Elev= 30
       0  367.72  664.27  341.29 4886.42  341.27 5036.25  358.35 5134.01  341.39
 7101.49  344.67 7895.14  338.22 7964.34  307.05 8044.15  307.05 8091.33   337.2
 8569.44  340.51 8615.35  353.33 8687.44  339.0211147.39  342.7811938.23  353.93
 14917.9  333.3615544.08  344.4915787.85  348.3215821.34  358.8615854.25  365.51
15944.49  340.7818919.48  341.1719125.61  336.2519219.92  355.1219309.16  337.01
19569.22  340.6919689.88  322.75 19763.6  342.9721122.58  355.1722253.59   442.7
#Mann= 11 ,-1 , 0
       0     .06       0 4886.42     .06       0 7101.49     .15       0
 7895.14    .055       0 8091.33     .15       0 8569.44     .05       0
11147.39      .1       015544.08     .05       015787.85     .15       0
15821.34     .05       018919.48     .15       0
#XS Ineff= 2 , 0
       0    3088     370   20406       0     370
Permanent Ineff=
       F       F
Bank Sta=7895.14,8091.33
XS Rating Curve= 0 ,0
Exp/Cntr=0.3,0.1

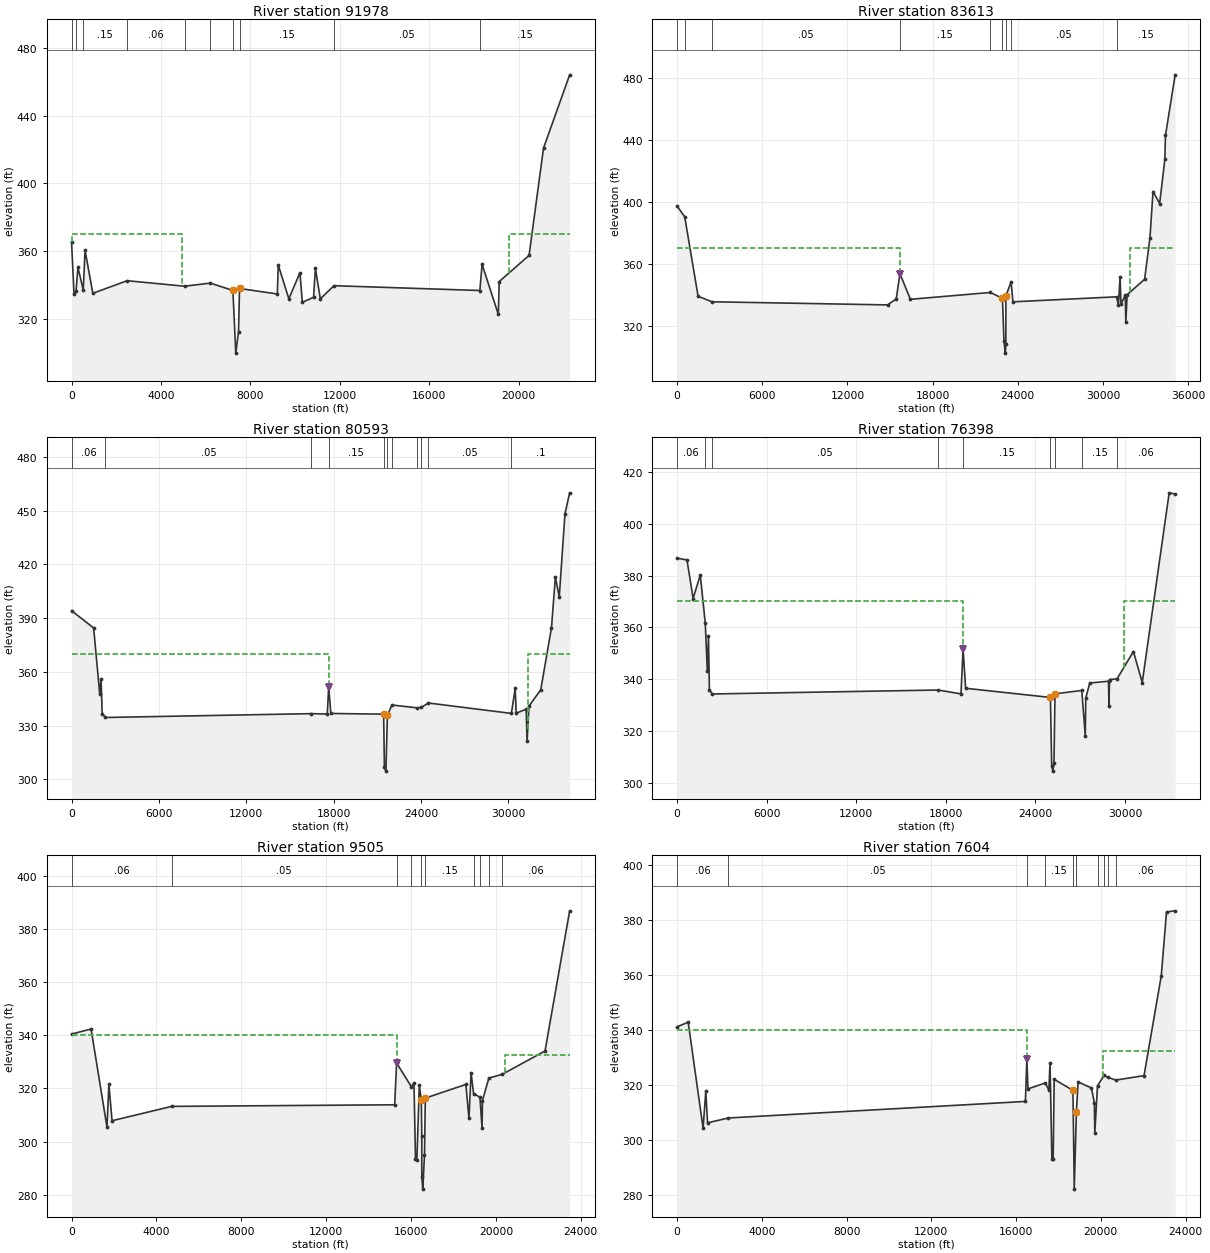
Type RM Length L Ch R = 1 ,91978   ,4138.76,8364.88,1686.69
BEGIN DESCRIPTION:
ROB IFA station 19544: flow contraction due to Ellis LID2 levee downstream
END DESCRIPTION:
XS GIS Cut Line= 4
     2590625.798     6873699.699     2589782.682     6873544.148
     2581579.557      6869985.12     2570937.044     6863505.074
#Sta/Elev= 30
       0  365.13  109.35  334.88  201.58  336.47  284.32  350.34  521.47  336.98
  603.74  360.39  950.43  335.01 2486.36  342.47 5052.56  339.21 6207.56  341.05
 7214.87  336.71  7345.3  299.69 7468.33  312.42 7512.83  337.87 9203.08  334.63
 9244.69  351.73 9718.85   331.810215.64  347.19 10322.3  329.7310824.22  332.64
10907.49  349.7411126.28  331.7611738.14  339.5218262.54  336.6818361.42   352.1
 19088.2  322.63 19127.3  341.9620463.34  357.4121109.56  420.7822278.61  464.08
#Mann= 10 ,-1 , 0
       0      .1       0  201.58     .06       0  521.47     .15       0
 2486.36     .06       0 5052.56     .15       0 6207.56     .15       0
 7214.87    .055       0 7512.83     .15       011738.14     .05       0
18262.54     .15       0
#XS Ineff= 2 , 0
       0    4947     370   19544       0     370
Permanent Ineff=
       F       F
Bank Sta=7214.87,7512.83
XS Rating Curve= 0 ,0
Exp/Cntr=0.3,0.1

Type RM Length L Ch R = 1 ,83613   ,1518.94,3020.05,1285.42
BEGIN DESCRIPTION:
LOB - Kaufman MUD1
ROB IFA station 31889: flow contraction due to Ellis LID2 levee downstream
END DESCRIPTION:
XS GIS Cut Line= 5
 2603730.71705116874962.430372162589554.058159446867922.78274316
2582787.478298336868020.815150572581851.714409446867784.70403946
2571296.158853886863163.17626168
#Sta/Elev= 30
       0  397.32  540.81  390.23 1480.71  339.04 2461.87   335.514828.84  333.48
15435.57  337.3415698.16  353.6316433.92  337.09 22060.2  341.4922918.43  337.78
23023.94  310.1423124.06  302.3723156.99  308.27 23160.3  339.2523528.43  348.36
23656.09  335.47 30958.4   338.7 31086.6  333.2431202.91   351.431269.87  333.96
31565.77  339.7931610.92  322.4731700.83  340.0332932.54  350.0433309.22  376.78
33524.86  406.6433991.07  398.8934357.37  427.3634400.71   442.835083.67  481.91
#Mann= 9 ,-1 , 0
       0     .05       0  540.81     .06       0 2461.87     .05       0
15698.16     .15       0 22060.2     .15       022918.43    .055       0
 23160.3     .15       023528.43     .05       0 30958.4     .15       0
Levee=-1,15698.16,353.63,0,,,,
#XS Ineff= 2 , 0
       015698.94     370   31889       0     370
Permanent Ineff=
       F       F
Bank Sta=22918.43,23160.3
XS Rating Curve= 0 ,0
Exp/Cntr=0.3,0.1

Type RM Length L Ch R = 1 ,80593   ,1304.95,4194.89,2623.31
BEGIN DESCRIPTION:
LOB - Kaufman MUD1
ROB IFA station 31341: flow contraction due to Ellis LID2 levee downstream
END DESCRIPTION:
XS GIS Cut Line= 6
2604850.392977026873169.60629808 2588498.97540486866569.52707184
2584746.024015916866460.15207184 2584447.41290486866460.15207184
2582244.114293696866392.443738512572504.492187216862954.84292834
#Sta/Elev= 30
       0  394.15  1516.1  384.52 1932.41  347.79  2026.7   355.8 2104.64   336.7
 2330.28  334.5816478.23  336.7217568.33  336.5117663.45  351.74 17813.6  336.82
 21439.5  336.4421493.62   306.721595.69  304.6521696.77  335.7322009.81  341.55
23755.07  339.9524019.96  340.2224517.68  342.6630214.87  336.8530477.93  350.79
30547.66  337.0131235.09  339.1931292.71  321.24 31428.5  340.9732233.27  350.02
 32971.5  384.6633237.13  412.85 33505.8  401.8833895.88  448.14 34219.2  459.92
#Mann= 11 ,-1 , 0
       0     .06       0 2330.28     .05       016478.23     .15       0
17663.45     .15       0 21439.5    .055       021696.77     .15       0
22009.81     .06       023755.07     .15       024019.96     .06       0
24517.68     .05       030214.87      .1       0
Levee=-1,17663.45,351.74,0,,,,
#XS Ineff= 2 , 0
       017663.57     370   31341       0     370
Permanent Ineff=
       F       F
Bank Sta=21439.5,21696.77
XS Rating Curve= 0 ,0
Exp/Cntr=0.3,0.1

Type RM Length L Ch R = 1 ,76398   ,1366.66,1790.14,1812.24
BEGIN DESCRIPTION:
LOB - Kaufman MUD1
ROB IFA station 29917: flow contraction due to Ellis LID2 levee downstream
END DESCRIPTION:
XS GIS Cut Line= 4
2606496.303529836870144.903692242582555.794270566864008.95461815
2581795.377603896863650.621284822574149.081307596862047.68147001
#Sta/Elev= 30
       0  386.75  664.16  386.05 1075.59  371.15 1553.77  380.26 1887.39  361.67
 2028.38     343 2102.55  356.67 2165.46  335.77 2369.57  334.26 17484.7  335.79
19019.32  334.2919159.68  351.5219332.29  336.4625011.92  332.9225095.98  306.48
25173.32  304.4425249.32   307.725316.97  334.3127111.45  335.6227346.03  318.15
27381.17  332.7527648.06  338.5128902.27  339.1828930.64  329.4228969.84  339.84
29472.69  340.1130572.04  350.6631162.57  338.6932967.12     41233367.44  411.53
#Mann= 9 ,-1 , 0
       0     .06       0 1887.39      .1       0 2369.57     .05       0
 17484.7     .15       019159.68     .15       025011.92    .055       0
25316.97     .06       027111.45     .15       029472.69     .06       0
Levee=-1,19159.68,351.52,0,,,,
#XS Ineff= 2 , 0
       019160.35     370   29917       0     370
Permanent Ineff=
       F       F
Bank Sta=25011.92,25316.97
XS Rating Curve= 0 ,0
Exp/Cntr=0.3,0.1

Type RM Length L Ch R = 1 ,9505    ,1134.79,1900.98,1032.38
BEGIN DESCRIPTION:
LOB - Kaufman LID1/Henderson LID1
END DESCRIPTION:
XS GIS Cut Line= 4
  2617943.653671  6822780.116724 2602120.2802758  6821643.751677
 2600430.9125433 6821757.1829476 2594525.7712673 6821374.0195375
#Sta/Elev= 30
       0   340.5  919.31  342.41  1668.9  305.46 1758.73  321.51 1908.43  307.85
 4718.92  313.25 15227.5  313.8615319.42  329.5916014.85  320.6716138.72  322.04
16208.93  293.4216274.19  293.01 16389.1  321.1916483.71  315.5916505.97  302.11
16507.06   286.616552.25  282.0816633.09  294.9316672.79  316.3718584.62  321.53
18728.66  308.7218828.48  325.8918946.26  318.0919245.89  316.7119346.87  305.02
19365.78  315.4519666.52   323.920300.58  325.3522314.28  334.1323474.79  386.93
#Mann= 10 ,-1 , 0
       0     .06       0 4718.92     .05       015319.42     .06       0
16014.85     .15       016483.71    .055       016672.79     .15       0
18946.26     .05       019245.89     .15       019666.52     .05       0
20300.58     .06       0
Levee=-1,15319.42,329.59,0,,,,
#XS Ineff= 2 , 0
       015319.21     34020419.34       0   332.5
Permanent Ineff=
       F       F
Bank Sta=16483.71,16672.79
XS Rating Curve= 0 ,0
Exp/Cntr=0.3,0.1

Type RM Length L Ch R = 1 ,7604    ,1109.26,1315.69,1024.77
BEGIN DESCRIPTION:
LOB - Kaufman LID1/Henderson LID1
END DESCRIPTION:
XS GIS Cut Line= 4
  2618706.625802  6821790.315041 2600688.1924188 6820426.8980209
  2599694.164641 6820689.1896876 2595306.2479743 6820253.2869098
#Sta/Elev= 30
       0  341.11  524.17  342.78 1228.28   304.3 1355.65  317.87 1437.33  306.28
 2425.82  308.0316439.61  314.0316509.06  329.6116559.86  318.5717380.66  320.75
17546.34  318.1217601.51  327.9817689.72  293.1217750.21  292.9817797.94  322.06
18683.77  318.0518744.51  282.2118846.83  310.2818926.93   321.119558.28   318.9
19694.32  313.4819714.03  302.4719842.43  319.7220153.77  323.4920349.21  322.72
20704.53  321.7822037.77  323.3922850.49  359.5523099.93   382.823507.45   383.2
#Mann= 10 ,-1 , 0
       0     .06       0 2425.82     .05       016509.06     .06       0
17380.66     .15       018683.77    .055       018846.83     .15       0
19842.43     .05       020153.77     .15       020349.21     .05       0
20704.53     .06       0
Levee=-1,16509.06,329.61,0,,,,
#XS Ineff= 2 , 0
       0   16509     34020091.76       0   332.5
Permanent Ineff=
       F       F
Bank Sta=18683.77,18846.83
XS Rating Curve= 0 ,0
Exp/Cntr=0.3,0.1

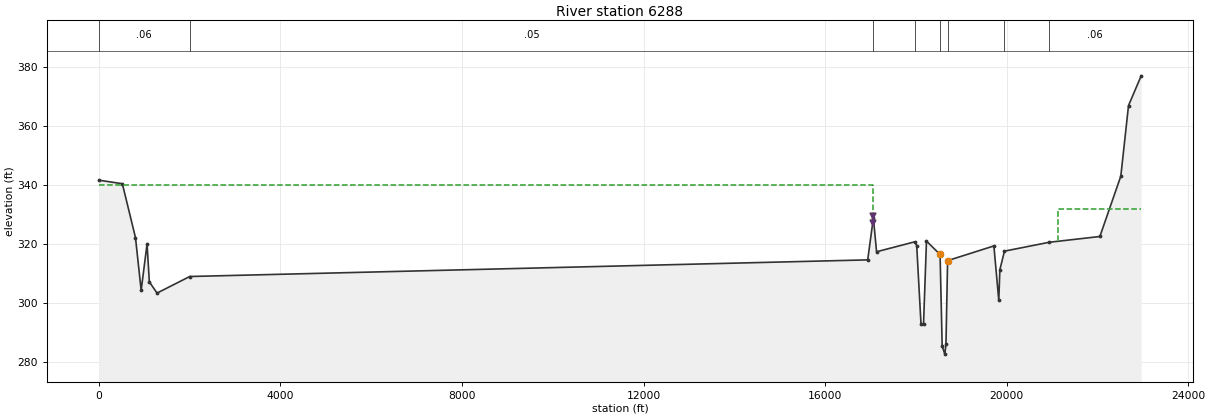
Type RM Length L Ch R = 1 ,6288    ,4777.52,6287.97,5432.52
BEGIN DESCRIPTION:
LOB - Kaufman LID1/Henderson LID1
END DESCRIPTION:
XS GIS Cut Line= 6
2619293.73848072 6820341.02639792618516.223959626819988.94081597
2602318.95386082 6819749.15356592600866.164771656819685.79903381
2600323.704570476819714.953503062596424.624770226819393.00007872
#Sta/Elev= 30
       0  341.78   519.1  340.57   808.6  322.28  933.51  304.43 1063.51  320.15
  1113.5  307.29 1283.49  303.49 2003.45  309.1116938.12  314.7517063.12  328.99
17133.08   317.517972.71  320.8718017.69   319.618112.65  292.8618167.63  292.91
 18232.6  321.1118532.45  316.58 18578.5   285.518636.94  282.7918662.12  286.18
18698.05  314.4919717.65  319.4819825.78  300.99   19849  311.3819950.19  317.71
20936.78  320.7222052.49  322.6822513.65  343.1422683.49  367.0922962.33  377.16
#Mann= 8 ,-1 , 0
       0     .06       0 2003.45     .05       017063.12     .06       0
17972.71     .15       018532.45    .055       018698.05     .15       0
19950.19     .05       020936.78     .06       0
Levee=-1,17048.12,329.68,0,,,,
#XS Ineff= 2 , 0
       017048.58     340   21133       0     332
Permanent Ineff=
       F       F
Bank Sta=18532.45,18698.05
XS Rating Curve= 0 ,0
Exp/Cntr=0.3,0.1
Stream Node=Trinity River   ,                , 0 , 0 ,Upstream end
Stream Node=Trinity River   ,                , 0 , 1 ,Downstream end
LCMann Table=0

--- TR_FEMA.g07 (geometry) ---

Geom Title=Trinity_NV_BoisDArcLevee
Program Version=5.06
BEGIN GEOM DESCRIPTION:
Scenario E
END GEOM DESCRIPTION:

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
River Reach=Trinity River   ,1

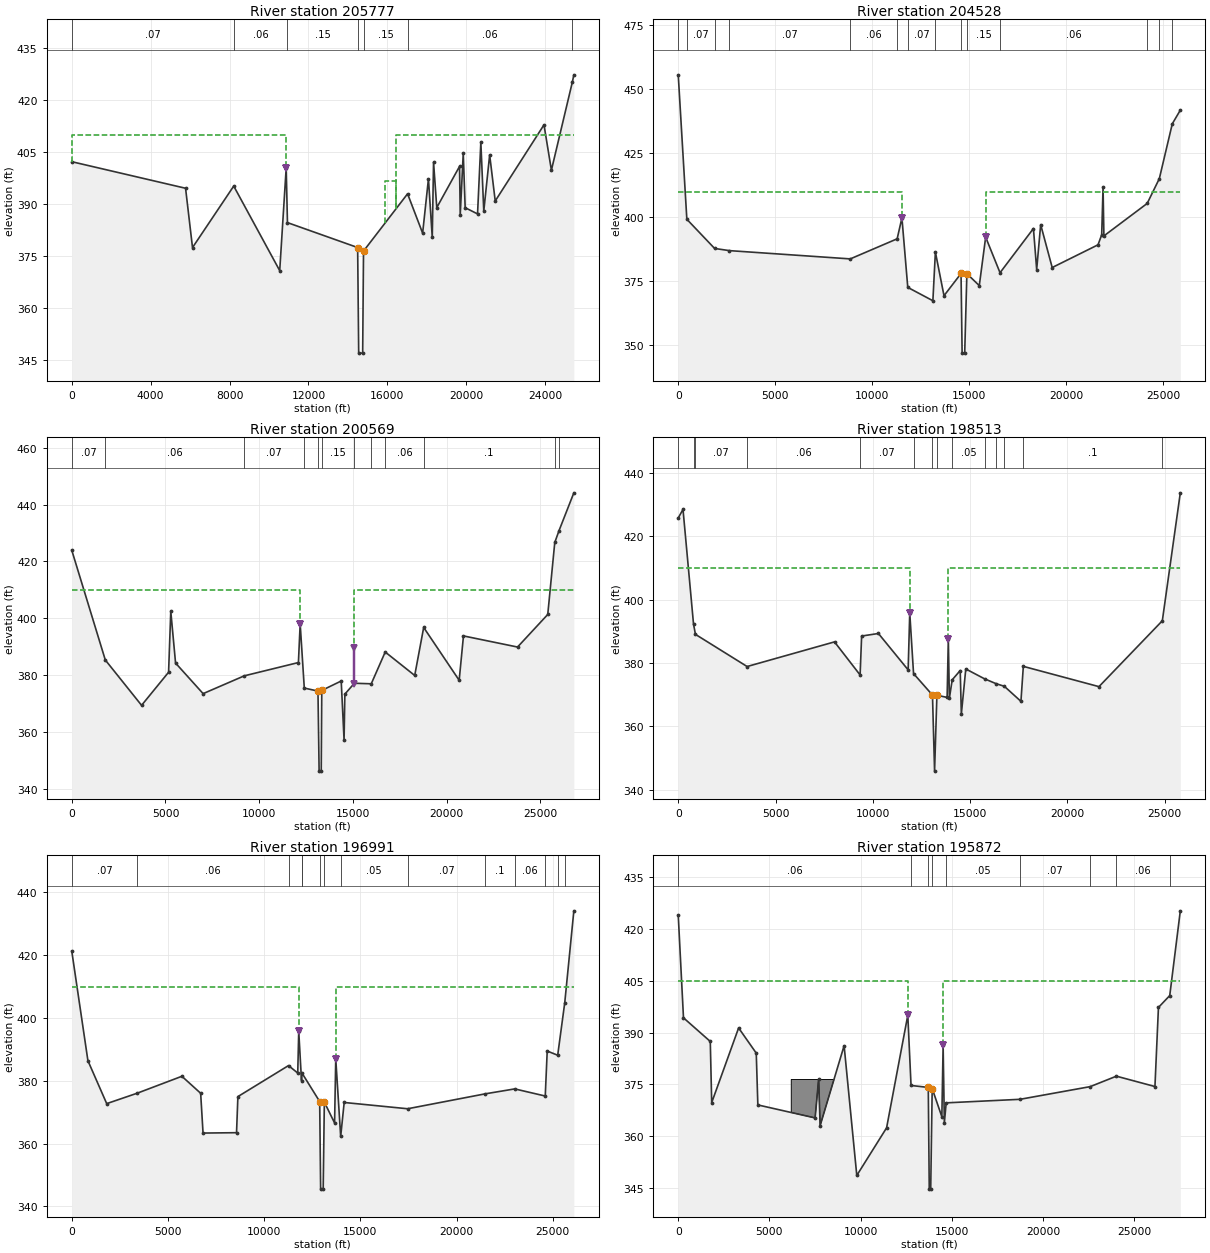
Type RM Length L Ch R = 1 ,205777  ,1262.75,1248.24,1229.51
BEGIN DESCRIPTION:
LOB - Southside WWTP
ROB IFA station 16416: flow contraction due to Dallas LID1/2 levee downstream
END DESCRIPTION:
XS GIS Cut Line= 6
2540980.83019298 6933539.73664742535497.477602626924208.30611411
2533614.000070366920921.000024692533600.635923866920903.28221235
 2529903.70565376914444.53364694 2528203.05241526911525.84775851
#Sta/Elev= 30
       0  402.32 5769.27  394.66 6121.02  377.55 8210.64  395.2910542.62  370.89
10870.96  400.54 10934.7  384.7514493.46  377.5614546.29   347.114748.07   347.1
14791.42  376.5417024.34  393.0617788.14  381.7118082.62  397.3718276.12  380.47
18341.35  402.1718504.74  389.0819659.18  400.9719693.92  387.0319847.13  404.74
19944.42  389.0520572.06  387.2620739.04  407.9220887.76  388.0721186.02  404.29
21468.32  390.9923940.48  412.9624316.52  399.8725381.49  425.37 25454.1  427.38
#Mann= 7 ,-1 , 0
       0     .07       0 8210.64     .06       0 10934.7     .15       0
14493.46    .055       014791.42     .15       017024.34     .06       0
25381.49     .08       0
Levee=-1,10870.96,400.54,0,,,,
#XS Ineff= 3 ,-1
       010870.96     41015871.74   16416  396.63   16416 25454.1     410
Permanent Ineff=
       F       F       F
Bank Sta=14493.46,14791.42
XS Rating Curve= 0 ,0
Exp/Cntr=0.3,0.1

Type RM Length L Ch R = 1 ,204528  ,2887.05,3959.05,2930.12
BEGIN DESCRIPTION:
LOB - Southside WWTP, ROB - Dallas LID1/2
END DESCRIPTION:
XS GIS Cut Line= 2
2542141.897480176933195.790666072529164.466924626910799.95733273
#Sta/Elev= 30
       0  455.63  443.94  399.25 1874.77  387.86 2636.03  387.01 8868.79  383.78
 11286.5  391.6211531.94  399.8111833.59  372.66   13128  367.4513257.32  386.45
13701.35  369.4114580.29  378.0914635.11     34714768.51     34714880.75  378.02
 15520.2  373.3515849.58  392.2716589.78  378.3818311.86  395.6418478.88  379.64
18685.27  397.1519279.01  380.4121641.73  389.2821830.52  393.1621901.42  411.66
21944.71  392.7524176.62  405.4324802.88  415.12 25470.9  436.52 25884.1  441.84
#Mann= 14 ,-1 , 0
       0     .06       0  443.94     .07       0 1874.77     .06       0
 2636.03     .07       0 8868.79     .06       0 11286.5     .07       0
11833.59     .07       013257.32     .15       014580.29    .055       0
14880.75     .15       016589.78     .06       024176.62      .1       0
24802.88     .08       0 25470.9     .06       0
Levee=-1,11531.94,399.81,-1,15849.58,392.27,,
#XS Ineff= 2 ,-1
       011531.94     41015849.58 25884.1     410
Permanent Ineff=
       F       F
Bank Sta=14580.29,14880.75
XS Rating Curve= 0 ,0
Exp/Cntr=0.3,0.1

Type RM Length L Ch R = 1 ,200569  ,2068.54,2056.32,2002.94
BEGIN DESCRIPTION:
LOB - Southside WWTP, ROB - Dallas LID1/2
END DESCRIPTION:
XS GIS Cut Line= 2
2544594.042023046931842.514654862531312.792023046908578.62576596
#Sta/Elev= 30
       0  423.94 1788.99  385.37 3724.12  369.43 5165.31  381.06  5282.7  402.49
 5537.92  384.29 7008.09  373.54 9204.36   379.8 12092.6  384.4712186.52  398.09
12405.92   375.513135.77  374.4413197.04   346.313309.94   346.313339.14  374.67
14376.03  377.98 14528.7  357.2114570.62  373.3715078.25  377.1915978.95     377
16723.98  388.1718297.74  379.9318776.03   396.820669.98  378.2320898.87  393.83
23784.09  389.9225396.01  401.3725770.55  426.6825998.04  430.8526788.13  444.13
#Mann= 12 ,-1 , 0
       0     .07       0 1788.99     .06       0 9204.36     .07       0
12405.92     .15       013135.77    .055       013339.14     .15       0
15078.25     .05       015978.95     .15       016723.98     .06       0
18776.03      .1       025770.55     .06       025998.04      .1       0
Levee=-1,12186.52,398.09,-1,15042.98,389.42,,
#XS Ineff= 2 , 0
       012186.52     41015042.98       0     410
Permanent Ineff=
       F       F
Bank Sta=13135.77,13339.14
XS Rating Curve= 0 ,0
Exp/Cntr=0.3,0.1

Type RM Length L Ch R = 1 ,198513  ,1460.65,1522.21,1546.82
BEGIN DESCRIPTION:
LOB - Southside WWTP, ROB - Dallas LID1/2
END DESCRIPTION:
XS GIS Cut Line= 2
2546593.000356376930554.320210412533259.667023046908470.98687708
#Sta/Elev= 30
       0  425.75  245.08  428.46  785.82  392.24  884.58  389.01 3538.59  378.86
  8028.9  386.64 9344.62  376.19 9422.44  388.4810284.69  389.2911812.69   377.8
11895.24  395.8312090.23  376.6313062.88  369.8413170.69  345.8413290.24  369.79
13815.75  369.1113876.77  387.6313931.21  368.8614077.49  374.6714487.86   377.6
14545.98  363.8614774.24  378.0915737.73  374.9816333.56  373.4416753.99  372.62
17607.92  367.8717730.47  378.9121616.22  372.5124872.14   393.325796.39  433.69
#Mann= 14 ,-1 , 0
       0     .07       0  785.82     .06       0  884.58     .07       0
 3538.59     .06       0 9344.62     .07       012090.23     .15       0
13062.88    .055       013290.24     .15       014077.49     .05       0
15737.73     .15       016333.56     .05       016753.99      .1       0
17730.47      .1       024872.14     .06       0
Levee=-1,11895.24,395.83,-1,13876.77,387.63,,
#XS Ineff= 2 , 0
       011895.24     41013876.77       0     410
Permanent Ineff=
       F       F
Bank Sta=13062.88,13290.24
XS Rating Curve= 0 ,0
Exp/Cntr=0.3,0.1

Type RM Length L Ch R = 1 ,196991  ,1114.91,1119.14,1044.18
BEGIN DESCRIPTION:
LOB - Southside WWTP, ROB - Dallas LID1/2
END DESCRIPTION:
XS GIS Cut Line= 4
2547677.578059796929952.10407455 2541957.4391709 6920324.0658801
2540764.383615346917785.437407882533997.022504236907764.60407454
#Sta/Elev= 30
       0  421.27  839.66  386.38 1815.93  372.72 3409.48  376.06 5723.11  381.43
 6699.35  376.02 6823.04  363.35 8563.77  363.47  8634.5  374.9611265.75  384.84
11744.94  382.4611797.07   395.811940.64  380.0711963.21  382.48 12885.5  373.39
12935.15   345.513068.07   345.513127.74   373.213659.69  366.5713720.65  387.01
13977.28  362.2714158.97  373.0917457.43  371.09 21480.1  375.8323024.23  377.41
24609.89  375.1424711.78  389.4725256.73  388.1325623.98  404.8926096.06  434.11
#Mann= 14 ,-1 , 0
       0     .07       0 3409.48     .06       011265.75     .07       0
11940.64     .06       011963.21     .15       0 12885.5    .055       0
13127.74     .15       013977.28     .05       017457.43     .07       0
 21480.1      .1       023024.23     .06       024609.89      .1       0
25256.73     .06       025623.98     .08       0
Levee=-1,11797.07,395.8,-1,13720.65,387.01,,
#XS Ineff= 2 , 0
       011797.07     41013720.65       0     410
Permanent Ineff=
       F       F
Bank Sta=12885.5,13127.74
XS Rating Curve= 0 ,0
Exp/Cntr=0.3,0.1

Type RM Length L Ch R = 1 ,195872  ,1736.76,1726.95,2123
BEGIN DESCRIPTION:
LOB - Southside WWTP, ROB - Dallas LID1/2
END DESCRIPTION:
XS GIS Cut Line= 4
2550259.667023046929359.875765962543024.453059796920010.14805602
2541811.258615346917361.536944912534173.275757926907095.38516339
#Sta/Elev= 30
       0  423.88  287.75  394.24 1757.09  387.42    1835  369.77 3310.85  391.32
 4278.01  384.05 4365.39   369.1 7505.83  365.35 7698.96  376.54    7781  363.13
 9095.51  386.19 9791.23  348.7511425.27  362.49   12588  394.9912765.73  374.72
13710.48  374.1513764.86   344.813843.92   344.813925.96  373.8214455.32  365.69
14525.15  386.3414592.48  363.9514693.44   369.718740.62  370.7222588.93  374.38
24027.44   377.426140.25  374.4126332.27  397.2426951.71  400.66 27531.3  425.12
#Mann= 9 ,-1 , 0
       0     .06       012765.73     .15       013710.48    .055       0
13925.96     .15       014693.44     .05       018740.62     .07       0
22588.93      .1       024027.44     .06       026951.71     .08       0
Levee=-1,12588,394.99,-1,14525.15,386.34,,
#XS Ineff= 2 , 0
       0   12588     40514525.15       0     405
Permanent Ineff=
       F       F
#Block Obstruct= 1 ,-1
 6197.83 8582.22  376.44
Bank Sta=13710.48,13925.96
XS Rating Curve= 0 ,0
Exp/Cntr=0.3,0.1