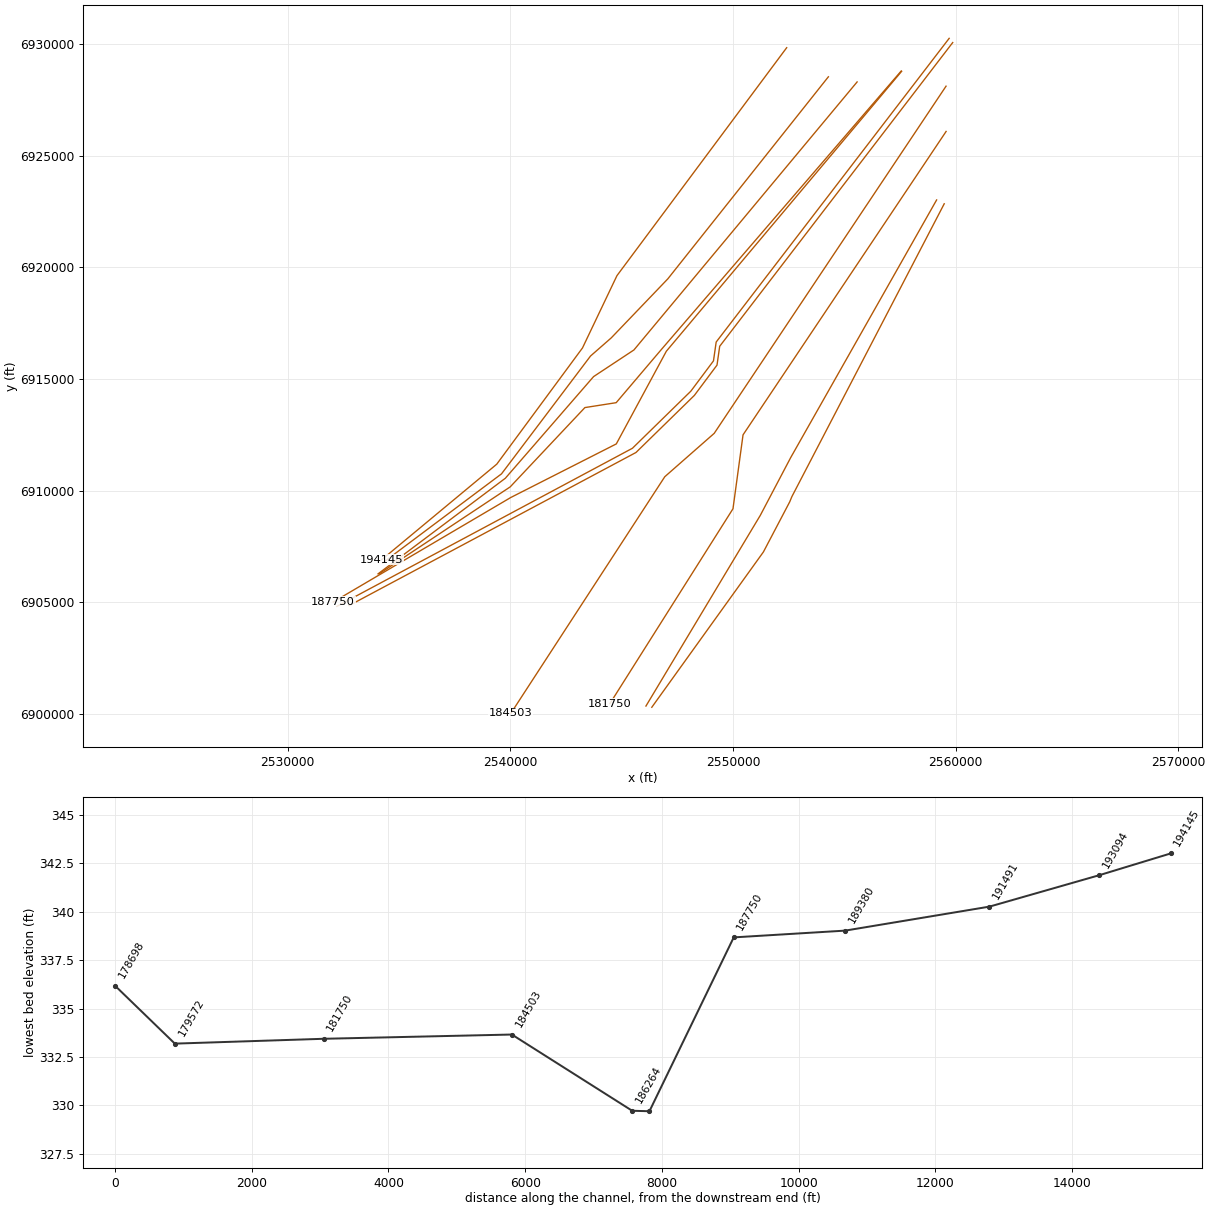
HEC-RAS study TR_FEMA.prj: Trinity_River_FEMA

--- TR_FEMA.g07 (geometry) --- (continued)

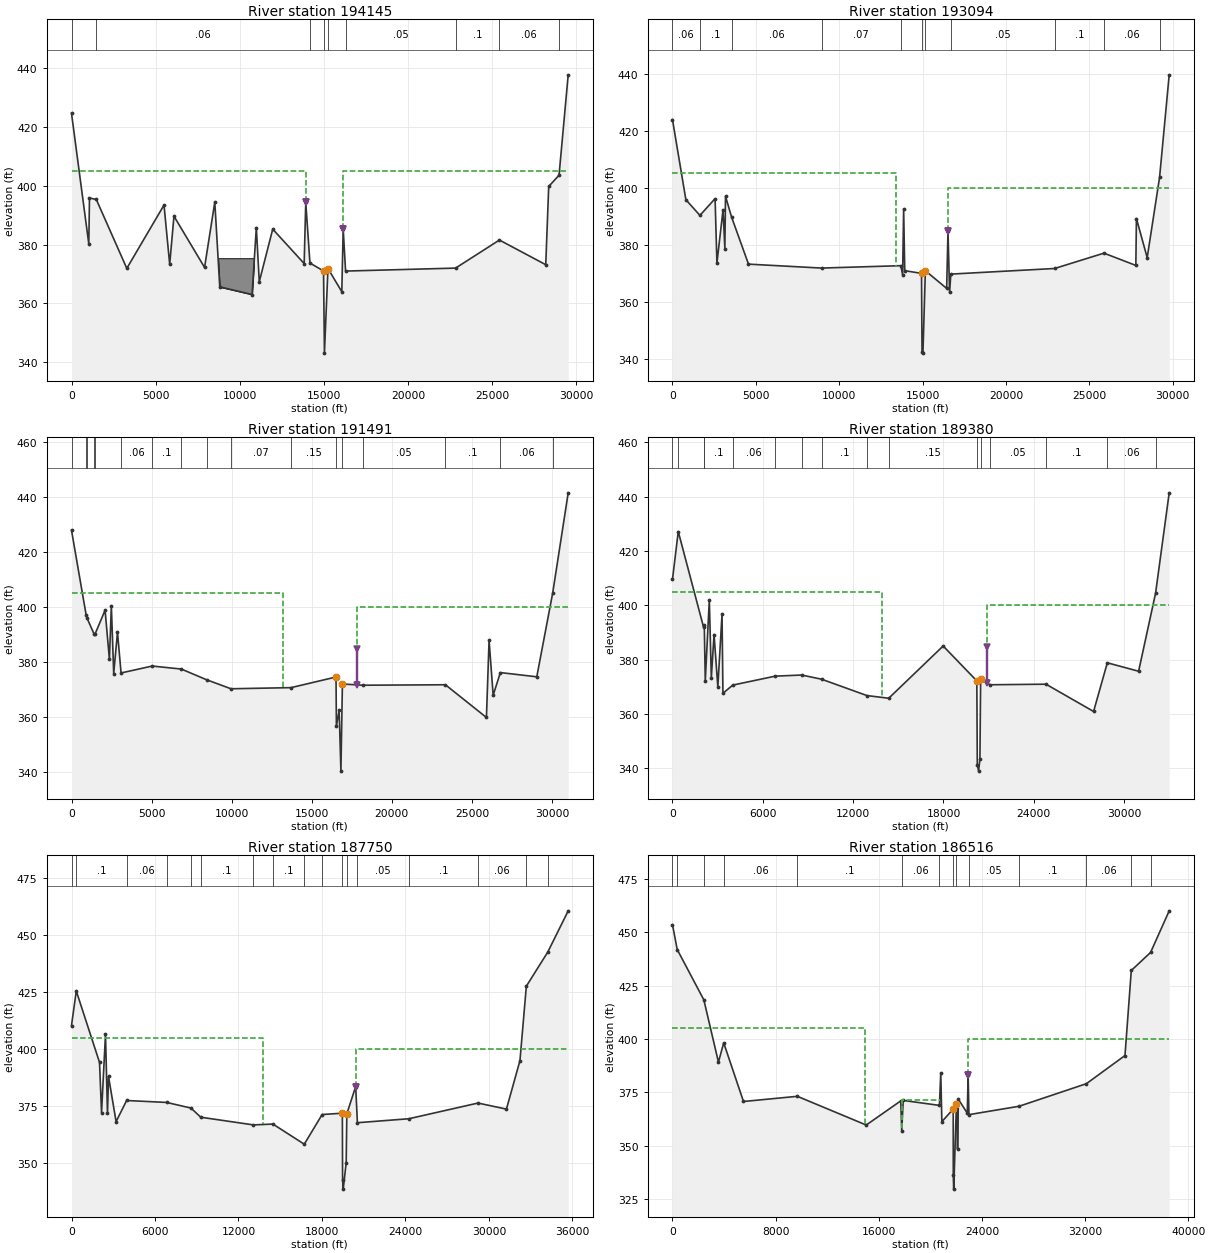
Type RM Length L Ch R = 1 ,194145  ,1483.79,1050.49,556.86
BEGIN DESCRIPTION:
LOB - Southside WWTP, ROB - Dallas LID1/2
END DESCRIPTION:
XS GIS Cut Line= 5
2552414.114273316929855.474110522544790.00861534 6919633.0184264
2543243.394032016916393.348287512539391.885627386911180.48068715
2534234.039646816906904.41294117
#Sta/Elev= 30
       0  424.67 1028.49  380.19 1068.58  395.85 1474.56  395.33 3287.19  371.88
 5499.11  393.44 5836.23  373.24 6089.75  389.65 7909.14   372.2 8517.13  394.42
 8812.55  365.5710733.65  362.9810985.54  385.7711161.06  367.3211960.74  385.24
13829.32  373.5213923.92  394.3114172.83   373.714979.29     37115034.01  343.02
 15243.9  371.8316066.48  363.9316149.17  385.3316290.69  370.9622830.01  371.97
 25434.8  381.53 28189.1  373.1328364.93  399.7628979.39  403.6129523.59  437.78
#Mann= 9 ,-1 , 0
       0     .07       0 1474.56     .06       014172.83     .15       0
14979.29    .055       0 15243.9     .15       016290.69     .05       0
22830.01      .1       0 25434.8     .06       028979.39     .08       0
Levee=-1,13923.92,394.31,-1,16149.17,385.33,,
#XS Ineff= 2 ,-1
       013923.92     40516149.1729523.59     405
Permanent Ineff=
       F       F
#Block Obstruct= 1 ,-1
 8647.3510836.41  375.33
Bank Sta=14979.29,15243.9
XS Rating Curve= 0 ,0
Exp/Cntr=0.3,0.1

Type RM Length L Ch R = 1 ,193094  ,1345.47,1602.93,571.88
BEGIN DESCRIPTION:
ROB - Dallas LID1/2
LOB IFA station 13414: flow expansion due to Southside WWTP levee upstream
END DESCRIPTION:
XS GIS Cut Line= 6
2554287.822272766928551.859861582547075.160235726919489.91541714
2544537.150976466916846.084398622543603.168337566916029.93509307
2539605.679296536910746.672576352534260.081313476906748.16294117
#Sta/Elev= 30
       0  423.87  802.13  395.77 1644.45  390.26 2553.75  396.14  2664.1  373.49
 3030.79  392.22 3140.18  378.62 3179.36  396.96 3542.33  389.68  4557.8  373.14
 8938.06  371.7613693.36   372.613800.43  369.4313862.06  392.4913928.82  370.85
14934.28  369.8914965.13  342.1215019.17  341.8915165.17  370.8216441.82  364.63
16521.31  384.7516617.88  363.1916691.96  369.6422916.42  371.6125874.64     377
27787.39  372.6927822.69  389.1528468.09  375.4129211.55  403.6529787.92  439.62
#Mann= 11 ,-1 , 0
       0     .06       0 1644.45      .1       0 3542.33     .06       0
 8938.06     .07       013693.36     .15       014934.28    .055       0
15165.17     .15       016691.96     .05       022916.42      .1       0
25874.64     .06       029211.55     .08       0
Levee=0,,,-1,16521.31,384.75,,
#XS Ineff= 2 ,-1
       0   13414     40516521.3129787.92     400
Permanent Ineff=
       F       F
Bank Sta=14934.28,15165.17
XS Rating Curve= 0 ,0
Exp/Cntr=0.3,0.1

Type RM Length L Ch R = 1 ,191491  ,988.29,2111.36,567.8
BEGIN DESCRIPTION:
ROB - Dallas LID1/2
LOB IFA station 13181: flow expansion due to Southside WWTP levee upstream
END DESCRIPTION:
XS GIS Cut Line= 5
2555578.266717196928321.341343082545553.422500736916302.54581884
2543740.689258426915107.066156172539778.685944756910550.30158257
 2534060.42853576906262.05183006
#Sta/Elev= 30
       0  427.89   914.4  397.07     958  396.09 1394.34  390.33 1462.77  390.03
 2095.76  398.81 2366.84  380.92 2487.11  400.45 2634.68  375.75  2870.8   390.8
 3094.27  375.98 5041.25   378.5 6856.41   377.4 8429.85  373.52 9956.04  370.23
13701.74  370.6416513.88  374.5116536.92  356.6116709.25  362.4516819.04  340.27
16912.14  371.9718190.28  371.5223342.01  371.6925903.58  359.7926067.98  387.88
26323.71  367.8826773.42  376.1229046.65  374.58 30044.5  405.21 31008.1  441.51
#Mann= 17 ,-1 , 0
       0     .08       0   914.4     .06       0     958     .08       0
 1394.34     .06       0 1462.77      .1       0 3094.27     .06       0
 5041.25      .1       0 6856.41     .06       0 8429.85      .1       0
 9956.04     .07       013701.74     .15       016513.88    .055       0
16912.14     .15       018190.28     .05       023342.01      .1       0
26773.42     .06       0 30044.5     .08       0
Levee=0,,,-1,17812.09,384.81,,
#XS Ineff= 3 ,-1
       0   13181     405                        17812.09 31008.1     400
Permanent Ineff=
       F       F       F
Bank Sta=16513.88,16912.14
XS Rating Curve= 0 ,0
Exp/Cntr=0.3,0.1

Type RM Length L Ch R = 1 ,189380  ,205.4,1630.38,1758.4
BEGIN DESCRIPTION:
ROB - Dallas LID1/2
LOB IFA station 13938: flow expansion due to Southside WWTP levee upstream
END DESCRIPTION:
XS GIS Cut Line= 6
  2557557.278625 6928809.5192494 2546769.9681061 6916304.8598616
  2544756.513245 6913938.4536116 2543350.9576894 6913718.6098616
 2539995.6050314 6910162.3039914 2534109.9081669 6906263.9017463
#Sta/Elev= 30
       0  409.66  382.37  427.22 2066.09  391.96 2111.19  392.75 2177.07  372.26
 2445.48  401.93 2579.32  373.42 2759.69   389.3 3011.42  370.03 3290.06  396.77
 3350.78  367.69 4004.94   370.7 6821.75  373.99 8574.54   374.4 9904.93  372.86
12916.52  366.8414364.36  365.8617978.65  385.0920215.37  372.2420245.75  341.42
20332.55  339.0320420.69  343.5120468.97   372.921083.89  370.8224809.52  371.03
27970.71  360.9928882.99   378.9   30962   375.832088.22  404.51 32993.3  441.47
#Mann= 16 ,-1 , 0
       0     .07       0  382.37      .1       0 2066.09     .08       0
 2111.19      .1       0 4004.94     .06       0 6821.75      .1       0
 8574.54     .06       0 9904.93      .1       012916.52     .07       0
14364.36     .15       020215.37    .055       020468.97     .15       0
21083.89     .05       024809.52      .1       028882.99     .06       0
32088.22     .08       0
Levee=0,,,-1,20921.35,384.68,,
#XS Ineff= 2 ,-1
       0   13938     40520921.35 32993.3     400
Permanent Ineff=
       F       F
Bank Sta=20215.37,20468.97
XS Rating Curve= 0 ,0
Exp/Cntr=0.3,0.1

Type RM Length L Ch R = 1 ,187750  ,1654.61,1233.35,710.34
BEGIN DESCRIPTION:
ROB - Dallas LID1/2
LOB IFA station 13773: flow expansion due to Southside WWTP levee upstream
END DESCRIPTION:
XS GIS Cut Line= 5
2557577.386206416928797.378293492547009.279724936916245.27181201
2544761.617613766912088.929152132540023.244450286909687.41087415
2532045.813894736904999.91087415
#Sta/Elev= 30
       0  410.26  342.82  425.39 2013.52  394.14 2158.93  372.18 2443.22  406.42
 2586.02  371.87 2660.15  387.99    3205  368.22  3962.1  377.46 6839.49  376.61
 8585.85  374.15  9293.2  370.1413071.24  366.7814477.86  367.14 16729.9  358.34
18015.08  371.3319466.71   371.919483.08  342.7219528.79  338.6819742.26  350.26
19786.89  371.6320423.79  383.5520548.26  367.7424238.57  369.4729214.57  376.34
31259.22  373.6932231.63  394.9232689.61  427.4734227.79  442.3835698.68  460.45
#Mann= 17 ,-1 , 0
       0     .07       0  342.82      .1       0  3962.1     .06       0
 6839.49      .1       0 8585.85     .06       0  9293.2      .1       0
13071.24     .07       014477.86      .1       0 16729.9     .06       0
18015.08     .15       019466.71    .055       019786.89     .15       0
20548.26     .05       024238.57      .1       029214.57     .06       0
32689.61     .08       034227.79     .06       0
Levee=0,,,-1,20423.79,383.55,,
#XS Ineff= 2 ,-1
       0   13773     40520423.7935698.68     400
Permanent Ineff=
       F       F
Bank Sta=19466.71,19786.89
XS Rating Curve= 0 ,0
Exp/Cntr=0.5,0.3

Type RM Length L Ch R = 1 ,186516  ,201.27,252.24,272.65
BEGIN DESCRIPTION:
US Bridge
ROB - Dallas LID1/2
LOB IFA station 14940: flow expansion due to Southside WWTP levee upstream
END DESCRIPTION:
XS GIS Cut Line= 6
2559712.908234356930276.007165022549247.630456586916657.95160946
2549126.428199636915812.501667332548110.369171856914455.29680621
2545486.671255186911894.532917332532205.312748246904802.37435251
#Sta/Elev= 30
       0  453.62  365.68  442.01 2431.77   418.4 3564.01  389.22 3972.03  398.26
 5505.96  370.77 9682.73   373.215027.22  359.7417703.92  371.05 17779.5  357.05
17897.26  371.2820703.97  368.9420807.66  383.9220893.23  361.3121773.35  367.22
21778.85 336.09421812.34 329.69622024.35  369.6822072.81  370.4222108.38  348.51
22174.81  371.7922863.36  365.3422930.59  383.1422993.09  364.61   26878  368.53
32104.46  379.1235096.33  392.3235586.17  432.1837082.52  440.6438526.05  460.14
#Mann= 14 ,-1 , 0
       0     .08       0  365.68     .07       0 2431.77      .1       0
 3972.03     .06       0 9682.73      .1       0 17779.5     .06       0
20703.97     .15       021773.35    .055       022024.35     .15       0
22993.09     .05       0   26878      .1       032104.46     .06       0
35586.17     .08       037082.52     .06       0
Levee=0,,,-1,22930.59,383.14,,
#XS Ineff= 3 ,-1
       0   14940     40517789.62 20742.7  371.6522930.5938526.05     400
Permanent Ineff=
       F       F       F
Bank Sta=21773.35,22024.35
XS Rating Curve= 0 ,0
Exp/Cntr=0.5,0.3

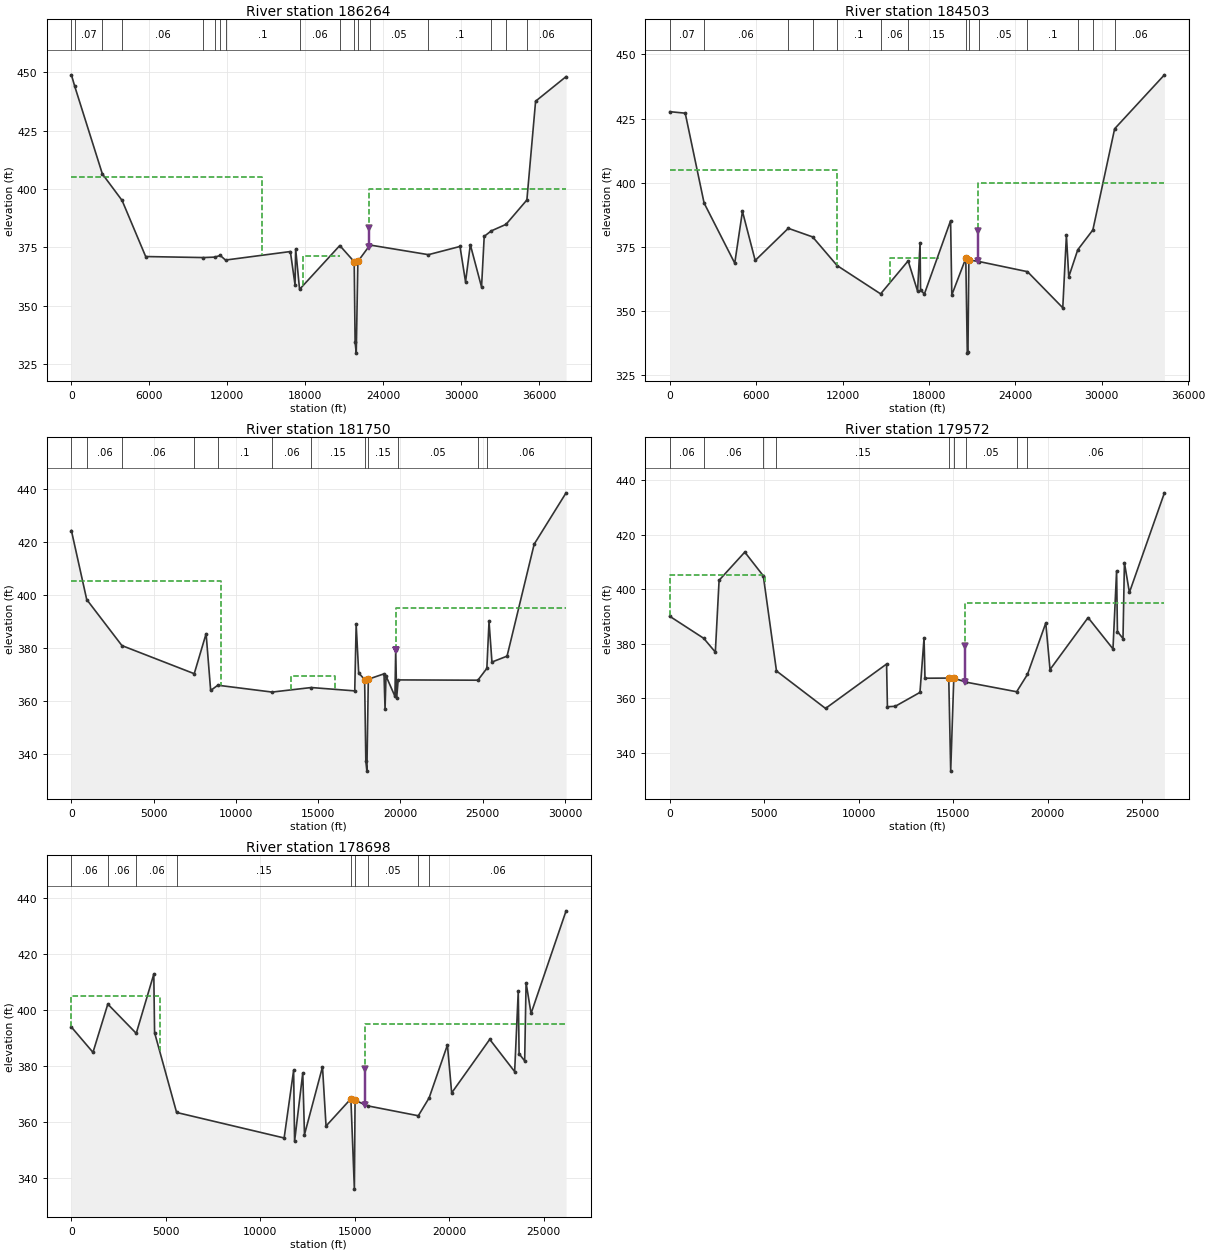
Type RM Length L Ch R = 1 ,186264  ,1855.44,1760.58,2233.35
BEGIN DESCRIPTION:
DS Bridge
ROB - Dallas LID1/2
LOB IFA station 14659: flow expansion due to Southside WWTP levee upstream
END DESCRIPTION:
XS GIS Cut Line= 6
2559871.226754126930085.983048982549405.948976346916467.92749342
2549284.746719396915622.477551292548268.687691616914265.27269018
2545644.989774956911704.508801292532761.29377277 6904841.7347546
#Sta/Elev= 30
       0  448.92  256.68     444 2382.59  406.47 3900.85  395.11  5715.6  371.09
10141.44  370.6511031.58  370.8411457.67  371.5511859.16  369.5816849.34  373.23
17208.86  358.9817256.36  374.3717558.05  357.03 20653.4   375.821761.57  368.87
21831.52 334.34321919.58  329.7222043.92  368.9822975.62  376.0227475.03  371.89
29902.81  375.4130329.89  360.2330698.82  376.1531561.26  358.0231766.54  379.73
32307.07  382.0733443.98  384.8735049.96  395.3135720.62  437.6238066.94  448.16
#Mann= 17 ,-1 , 0
       0     .08       0  256.68     .07       0 2382.59      .1       0
 3900.85     .06       010141.44      .1       011031.58     .06       0
11457.67     .06       011859.16      .1       017558.05     .06       0
 20653.4     .15       021761.57    .055       022043.92     .15       0
22975.62     .05       027475.03      .1       032307.07     .06       0
33443.98     .05       035049.96     .06       0
Levee=0,,,-1,22865.83,383.32,,
#XS Ineff= 3 ,-1
       0   14659     40517816.8720696.25   371.422865.8338066.94     400
Permanent Ineff=
       F       F       F
Bank Sta=21761.57,22043.92
XS Rating Curve= 0 ,0
Exp/Cntr=0.5,0.3

Type RM Length L Ch R = 1 ,184503  ,1141.76,2752.93,3502.22
BEGIN DESCRIPTION:
ROB - Dallas LID1/2
LOB IFA station 11625: flow expansion due to Southside WWTP levee upstream
END DESCRIPTION:
XS GIS Cut Line= 4
2559572.852699236928131.371101242549158.807805166912562.74643566
2546939.363360716910618.301991212540024.241588126900006.37110124
#Sta/Elev= 30
       0  427.72 1075.28  427.13 2384.82  392.14 4513.55   368.7 5048.05  388.89
 5933.32  369.75 8231.53  382.28 9920.58  378.9311625.88  367.7514641.38  356.74
16553.76   369.617207.45   357.8 17381.7  376.6117415.02  358.4217676.22  356.63
19500.41  385.2519585.37  356.3320555.35  370.5920659.95  333.6620707.16  334.17
20767.44  369.9621487.21  369.3324838.63  365.3927289.81  351.3227541.37  379.56
27706.21  363.3828329.32  373.9129377.92  381.64 30890.8  421.0634347.37  442.07
#Mann= 14 ,-1 , 0
       0     .07       0 2384.82     .06       0 8231.53     .06       0
 9920.58     .06       011625.88      .1       014641.38     .06       0
16553.76     .15       020555.35    .055       020767.44     .15       0
21487.21     .05       024838.63      .1       028329.32     .06       0
29377.92     .05       0 30890.8     .06       0
Levee=0,,,-1,21379.67,381.19,,
#XS Ineff= 3 ,-1
       0   11625     40515299.4518690.47   370.721379.6734347.37     400
Permanent Ineff=
       F       F       F
Bank Sta=20555.35,20767.44
XS Rating Curve= 0 ,0
Exp/Cntr=0.3,0.1

Type RM Length L Ch R = 1 ,181750  ,2178.07,2178.36,1237.92
BEGIN DESCRIPTION:
ROB - Dallas LID1/2
LOB IFA station 9113: flow expansion due to Southside WWTP levee upstream
END DESCRIPTION:
XS GIS Cut Line= 4
2559575.33418071 6926100.72295312550454.46752738 6912496.2533801
2550002.664865346909181.624907882544471.167514056900441.00073088
#Sta/Elev= 30
       0  424.22  930.84  398.19 3070.86  380.81 7466.12   370.2 8187.52   385.3
 8464.59  363.87 8900.14  365.8512198.84  363.2714578.21  364.9817222.38  363.72
 17308.4  388.8417461.85  370.4717822.88  368.0117896.15  337.1317960.37  333.44
18047.38  368.1219001.08  370.1519063.98   356.819122.93  369.3519665.02  361.68
19711.52  379.2819771.51  361.0919861.27  367.8624706.16  367.7525251.92  372.21
25384.35  389.9225562.23   374.626480.27  376.8328128.73  419.0830068.09  438.45
#Mann= 12 ,-1 , 0
       0     .07       0  930.84     .06       0 3070.86     .06       0
 7466.12     .06       0 8900.14      .1       012198.84     .06       0
14578.21     .15       017822.88    .055       018047.38     .15       0
19861.27     .05       024706.16      .1       025251.92     .06       0
Levee=0,,,-1,19711.52,379.28,,
#XS Ineff= 3 ,-1
       0    9113     40513322.3216016.37   369.419711.5230068.09     395
Permanent Ineff=
       F       F       F
Bank Sta=17822.88,18047.38
XS Rating Curve= 0 ,0
Exp/Cntr=0.3,0.1

Type RM Length L Ch R = 1 ,179572  ,766.97,874.08,934.72
BEGIN DESCRIPTION:
ROB - Dallas LID1/2
LOB IFA station 5017: flow expansion due to Southside WWTP levee upstream
END DESCRIPTION:
XS GIS Cut Line= 4
2559148.762421456923029.18128644 2552593.20686596911473.62573088
2551232.095754796908890.29239755 2546093.20686596900334.73684199
#Sta/Elev= 30
       0  390.02 1798.58  381.93 2413.01  376.87 2611.82  403.22  3971.5  413.57
 4951.44  404.86 5649.14  369.95 8245.78   356.211476.02  372.4911520.72  356.82
 11935.7  356.9813243.16  362.0813460.08  382.12 13508.2  367.2814767.13  367.34
14869.71  333.1915033.64  367.3215676.41  365.8518360.13  362.3218932.91  368.69
19901.66  387.5420125.82  370.4622140.59  389.5323458.89  378.0423649.71  406.69
23694.22  384.41   23989  381.8524063.88   409.724327.84  398.75 26181.2  435.32
#Mann= 9 ,-1 , 0
       0     .06       0 1798.58     .06       0 4951.44     .06       0
 5649.14     .15       014767.13    .055       015033.64     .15       0
15676.41     .05       018360.13      .1       018932.91     .06       0
Levee=0,,,-1,15617.55,378.97,,
#XS Ineff= 2 ,-1
       0    5017     40515617.55 26181.2     395
Permanent Ineff=
       F       F
Bank Sta=14767.13,15033.64
XS Rating Curve= 0 ,0
Exp/Cntr=0.3,0.1

Type RM Length L Ch R = 1 ,178698  ,1580.48,2677.02,409.08
BEGIN DESCRIPTION:
ROB - Dallas LID1/2
LOB IFA station 4672: flow expansion due to Southside WWTP levee upstream
END DESCRIPTION:
XS GIS Cut Line= 5
2559490.928754236922857.666574542552647.425477186909725.03967755
2552552.475919656909494.523410582551369.969250626907246.30085465
2546356.22769924  6900280.049342
#Sta/Elev= 30
       0  393.92 1141.95   384.9 1926.79  402.09 3431.82  391.67 4360.95  412.76
 4402.37  391.92 5567.51  363.4911258.94   354.411761.14   378.511812.03  353.22
12245.06  377.5412336.06   355.613289.19  379.7313476.76  358.6514791.64  368.36
 14976.7  336.1815012.84  367.8315676.41  365.8518360.13  362.3218932.91  368.69
19901.66  387.5420125.82  370.4622140.59  389.5323458.89  378.0423649.71  406.69
23694.22  384.41   23989  381.8524063.88   409.724327.84  398.75 26181.2  435.32
#Mann= 9 ,-1 , 0
       0     .06       0 1926.79     .06       0 3431.82     .06       0
 5567.51     .15       014791.64    .055       015012.84     .15       0
15676.41     .05       018360.13      .1       018932.91     .06       0
Levee=0,,,-1,15534.78,379,,
#XS Ineff= 2 ,-1
       0    4672     40515534.56 26181.2     395
Permanent Ineff=
       F       F
Bank Sta=14791.64,15012.84
XS Rating Curve= 0 ,0
Exp/Cntr=0.3,0.1