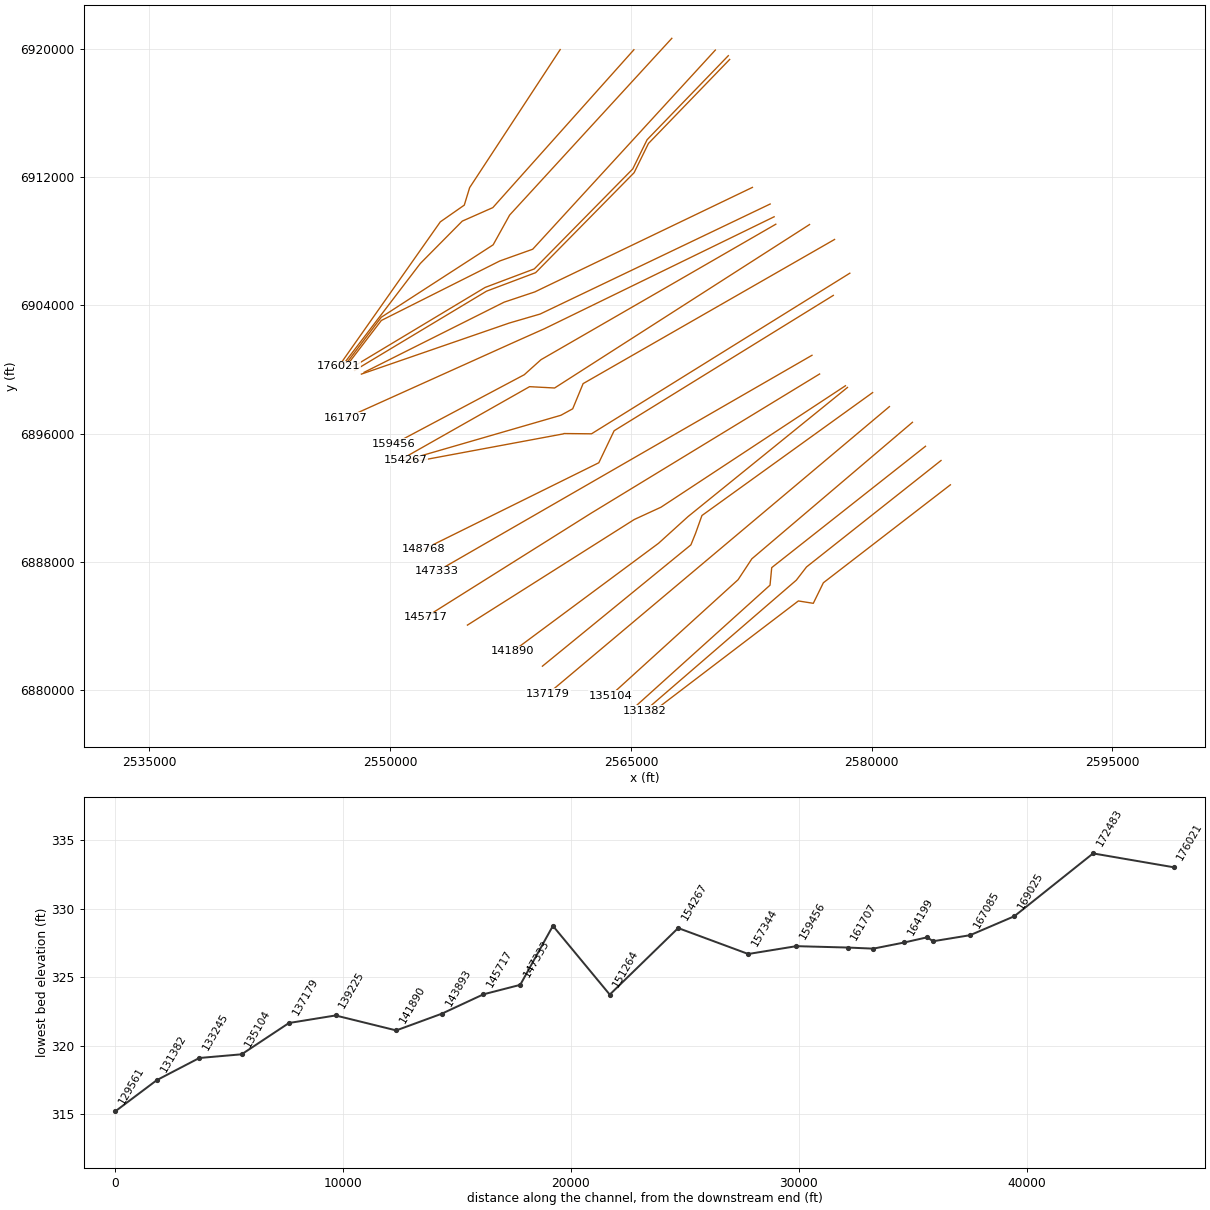
HEC-RAS study TR_FEMA.prj: Trinity_River_FEMA

--- TR_FEMA.g07 (geometry) --- (continued)

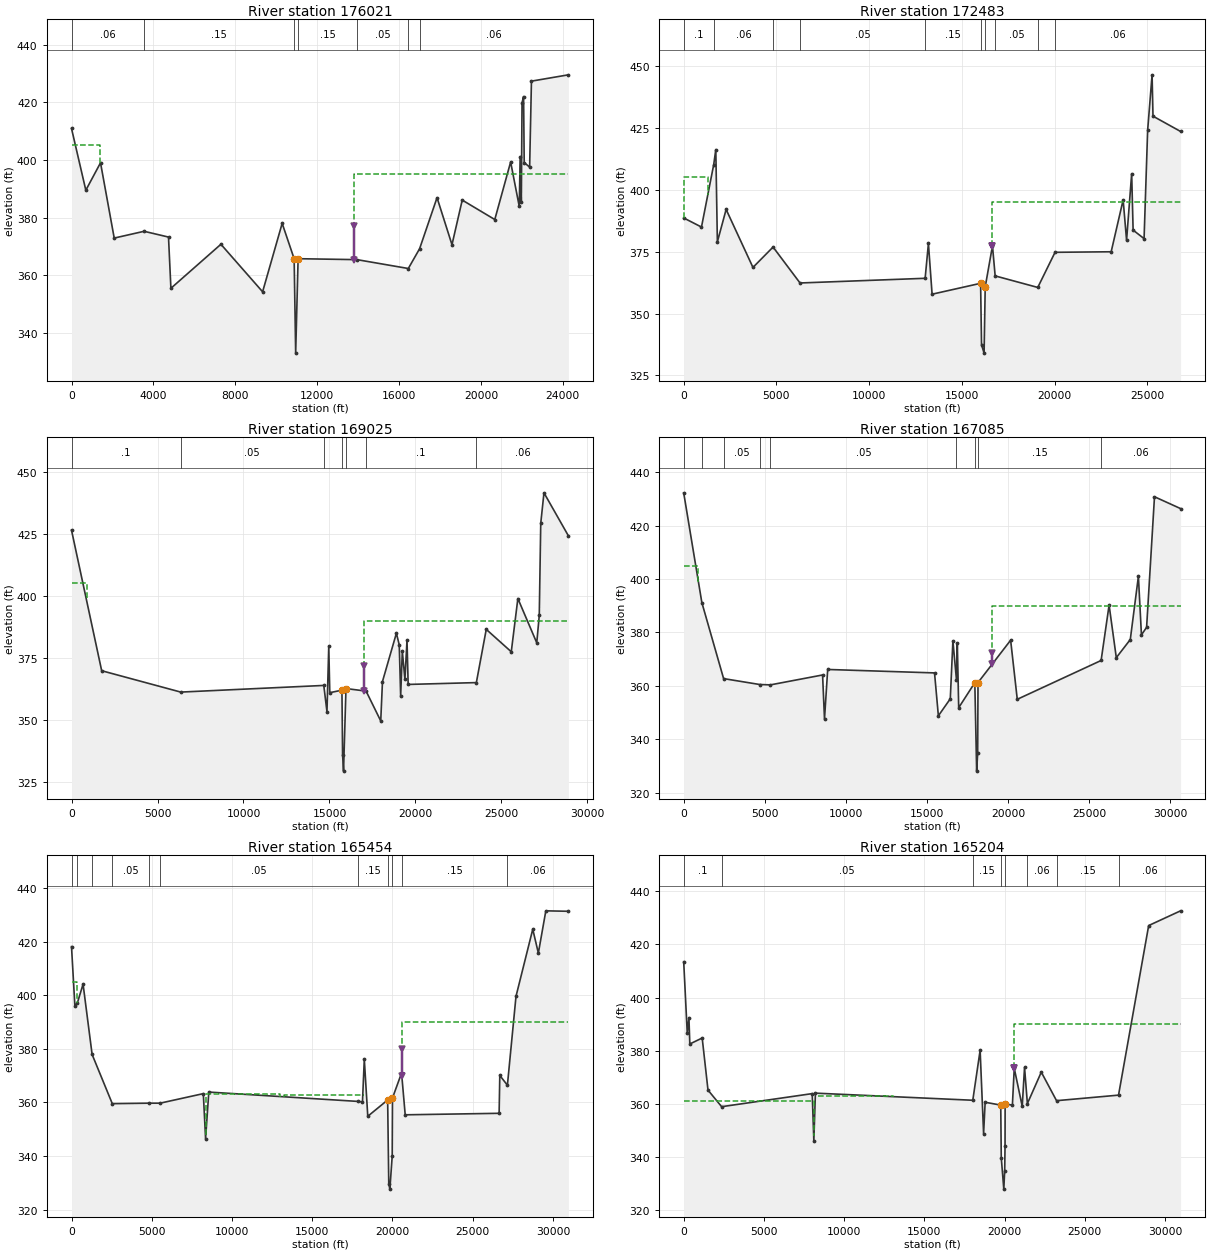
Type RM Length L Ch R = 1 ,176021  ,2531.23,3537.5,700.82
BEGIN DESCRIPTION:
ROB - Dallas LID1/2
LOB IFA station 1405: flow expansion due to Southside WWTP levee upstream
END DESCRIPTION:
XS GIS Cut Line= 5
2560588.416356656919955.471795722554947.803754236911347.82861158
2554613.081532016910254.773056032553119.24968998 6909210.7495735
2546787.65131034 6900195.8479531
#Sta/Elev= 30
       0   410.9   699.4  389.49 1417.12     399 2086.31   372.9 3545.85  375.25
 4738.33  373.25 4855.57  355.49 7298.32  370.75 9335.43  354.28 10291.1     378
10875.75  365.7410950.68  333.0111069.77  365.7513947.64  365.4216453.32  362.35
17004.74  369.21 17856.7  386.9118586.62   370.619087.61  386.0720677.71  379.33
21452.25  399.2821873.21  383.8621917.79  401.1421974.12  385.3622008.61  419.78
22084.37  421.9722114.88  399.0922380.36   397.522468.47  427.3124273.08   429.5
#Mann= 7 ,-1 , 0
       0     .06       0 3545.85     .15       010875.75    .055       0
11069.77     .15       013947.64     .05       016453.32      .1       0
17004.74     .06       0
Levee=0,,,-1,13805.69,376.97,,
#XS Ineff= 2 ,-1
       0    1405     40513805.6924273.08     395
Permanent Ineff=
       F       F
Bank Sta=10875.75,11069.77
XS Rating Curve= 0 ,0
Exp/Cntr=0.3,0.1

Type RM Length L Ch R = 1 ,172483  ,1181.15,3458.81,1936.55
BEGIN DESCRIPTION:
ROB - Dallas LID1/2
LOB IFA station 1297: flow expansion due to Southside WWTP levee upstream
END DESCRIPTION:
XS GIS Cut Line= 5
2565182.616588126919946.716008662556391.389458526910099.22201427
2554487.454273346909257.208125382551870.984643686906612.51461977
2547148.762421456900418.07017533
#Sta/Elev= 30
       0  388.58  959.04   384.9 1619.23  410.13  1731.1  416.16 1815.83  378.93
 2287.92  392.01 3734.32  368.61 4818.85  376.83 6272.44  362.33 13018.8  364.22
13195.63  378.2713393.67   357.8 16009.4   362.216059.69  337.3716197.71  334.02
16257.81  360.7516649.41  377.3216794.36  365.1919091.59  360.5320022.87  374.71
23050.08  374.9323695.19  395.8623880.43  379.5724155.03  406.4524233.05  383.67
24823.93  380.2325016.31  423.9125255.74  446.3425304.65  429.6626791.89  423.49
#Mann= 10 ,-1 , 0
       0      .1       0 1619.23     .06       0 4818.85      .1       0
 6272.44     .05       0 13018.8     .15       0 16009.4    .055       0
16257.81     .15       016794.36     .05       019091.59      .1       0
20022.87     .06       0
Levee=0,,,-1,16649.41,377.32,,
#XS Ineff= 2 ,-1
       0    1297     40516649.4126791.89     395
Permanent Ineff=
       F       F
Bank Sta=16009.4,16257.81
XS Rating Curve= 0 ,0
Exp/Cntr=0.3,0.1

Type RM Length L Ch R = 1 ,169025  ,2540.16,1939.9,813.21
BEGIN DESCRIPTION:
ROB - Dallas LID1/2
LOB IFA station 872: flow expansion due to Southside WWTP levee upstream
END DESCRIPTION:
XS GIS Cut Line= 5
2567543.277467766920656.860684622557438.775976456909634.40268566
2556412.387087566907779.541574552549440.672143686903262.27156422
2547322.616588126900463.66045311
#Sta/Elev= 30
       0  426.44 1754.32  369.86 6351.27  361.2614668.24  363.9414853.24  353.36
14957.67  379.6315017.11  361.02 15723.6  362.0415760.87  336.0915816.71  329.44
 15958.5  362.68 17127.3  361.6617979.41  349.6518080.67  365.5218889.65  384.95
19055.78  380.2919138.18  359.6719233.91  377.7519385.28  366.4119506.69  382.12
19574.07  364.3423539.21  365.0824114.59  386.5125569.27  377.4925952.78  398.93
27051.51  381.0927197.13  392.1327283.32  429.2327470.32  441.4828889.98  424.18
#Mann= 7 ,-1 , 0
       0      .1       0 6351.27     .05       014668.24     .15       0
 15723.6    .055       0 15958.5     .15       0 17127.3      .1       0
23539.21     .06       0
Levee=0,,,-1,17013.93,371.76,,
#XS Ineff= 3 ,-1
       0     872     405    4761    5806  361.7117013.9328889.98     390
Permanent Ineff=
       F       F       F
Bank Sta=15723.6,15958.5
XS Rating Curve= 0 ,0
Exp/Cntr=0.3,0.1

Type RM Length L Ch R = 1 ,167085  ,1087.43,1630.75,1236.82
BEGIN DESCRIPTION:
ROB - Dallas LID1/2
LOB IFA station 910: flow expansion due to Southside WWTP levee upstream
END DESCRIPTION:
XS GIS Cut Line= 5
2570255.574362936919925.554734122558876.389719376907504.55343791
2556828.766274576906773.46139785 2549444.14436596903060.88267533
 2547409.58254826900405.39565756
#Sta/Elev= 30
       0  432.25 1118.92  391.17 2460.13   362.7 4683.68  360.49 5344.28  360.35
 8561.69  364.06 8679.91  347.56 8876.83  366.1215463.17  364.8315699.37  348.77
16434.24  355.1416595.36  376.8116816.95  362.1816867.19  375.9816952.58  351.81
17946.58  361.1718059.61  328.0618122.12  334.7618143.76  361.2220154.42  377.07
20563.17  354.9525732.03  369.4826224.28  390.22 26668.4  370.5427530.81  377.32
28030.26  400.9828217.71  379.07 28536.5  381.8929022.37  430.7830630.34  426.35
#Mann= 9 ,-1 , 0
       0     .07       0 1118.92      .1       0 2460.13     .05       0
 4683.68      .1       0 5344.28     .05       016816.95     .15       0
17946.58    .055       018143.76     .15       025732.03     .06       0
Levee=0,,,-1,19010.01,372.34,,
#XS Ineff= 5 ,-1
       0     910     405     910    7664  361.71   11240   11612  363.24
   13962   14874     36319010.0130630.34     390
Permanent Ineff=
       F       F       F       F       F
Bank Sta=17946.58,18143.76
XS Rating Curve= 0 ,0
Exp/Cntr=0.5,0.3

Type RM Length L Ch R = 1 ,165454  ,224.76,250.22,261.43
BEGIN DESCRIPTION:
US Bridge
ROB - Dallas LID1/2
LOB IFA station 370: flow expansion due to Southside WWTP levee upstream
END DESCRIPTION:
XS GIS Cut Line= 6
2571064.517439086919575.161277432566003.753550186914334.01544409
2565110.003550176912511.793221862558975.281327946906277.24461073
2555912.086883486905121.68905517 2547692.46882796900176.72377738
#Sta/Elev= 30
       0  418.17  211.42  395.93  370.27  397.26  720.46  404.15 1284.49  377.89
 2541.58  359.53 4832.33  359.715517.479  359.718214.539  363.28 8355.23  346.47
 8555.71  363.8617874.37  360.36 18132.3  360.19 18246.3  376.0918463.09  354.82
19701.56   360.9 19770.9 329.645 19839.7 327.61719985.68  340.0420003.09  361.65
20568.99  370.9820795.05  355.3726647.99  355.9326690.77  370.0627164.25  366.42
   27700  399.6128744.54  424.6729092.81  415.7529559.32  431.5430964.49  431.37
#Mann= 11 ,-1 , 0
       0      .1       0  370.27     .07       0 1284.49      .1       0
 2541.58     .05       0 4832.33      .1       05517.479     .05       0
17874.37     .15       019701.56    .055       020003.09     .15       0
20568.99     .15       027164.25     .06       0
Levee=0,,,-1,20585.91,380,,
#XS Ineff= 5 ,-1
       0     370     405     370    8090  361.71    8371   13020  363.24
   13221   18234  362.8420585.9130964.49     390
Permanent Ineff=
       F       F       F       F       F
Bank Sta=19701.56,20003.09
XS Rating Curve= 0 ,0
Exp/Cntr=0.5,0.3

Type RM Length L Ch R = 1 ,165204  ,2833.82,1004.45,1013.94
BEGIN DESCRIPTION:
DS Bridge
 ROB - Dallas LID1/2
END DESCRIPTION:
XS GIS Cut Line= 6
2571148.471632786919340.467399712566087.707743886914099.32156637
2565193.957743886912277.099344142559059.235521646906042.55073301
2555996.041077196904886.995177452547776.423021616899942.02989966
#Sta/Elev= 30
       0  413.48  221.23  386.66  325.28  392.45  381.49  382.53 1152.41  384.78
 1514.88  365.17 2364.41  358.93 8009.12  363.85 8110.32  346.16 8208.18  364.03
18015.71  361.3518473.14  380.1618689.36  348.7918785.87   360.619757.48  359.53
19790.41   339.7 19948.8 327.90720003.44 334.86320025.39  344.1720031.36  359.91
20484.38  359.5520599.72  373.3721096.56  359.0721240.92  373.6921417.91   360.1
   22285  371.9423235.21  361.1927098.06  363.2828976.79   427.1 30964.4  432.64
#Mann= 8 ,-1 , 0
       0      .1       0 2364.41     .05       018015.71     .15       0
19757.48    .055       020031.36     .15       021417.91     .06       0
23235.21     .15       027098.06     .06       0
Levee=0,,,-1,20599.72,373.37,,
#XS Ineff= 5 ,-1
                               0    8101     361    8353   13046     363
   13205   18374   362.520599.72 30964.4     390
Permanent Ineff=
       F       F       F       F       F
Bank Sta=19757.48,20031.36
XS Rating Curve= 0 ,0
Exp/Cntr=0.5,0.3

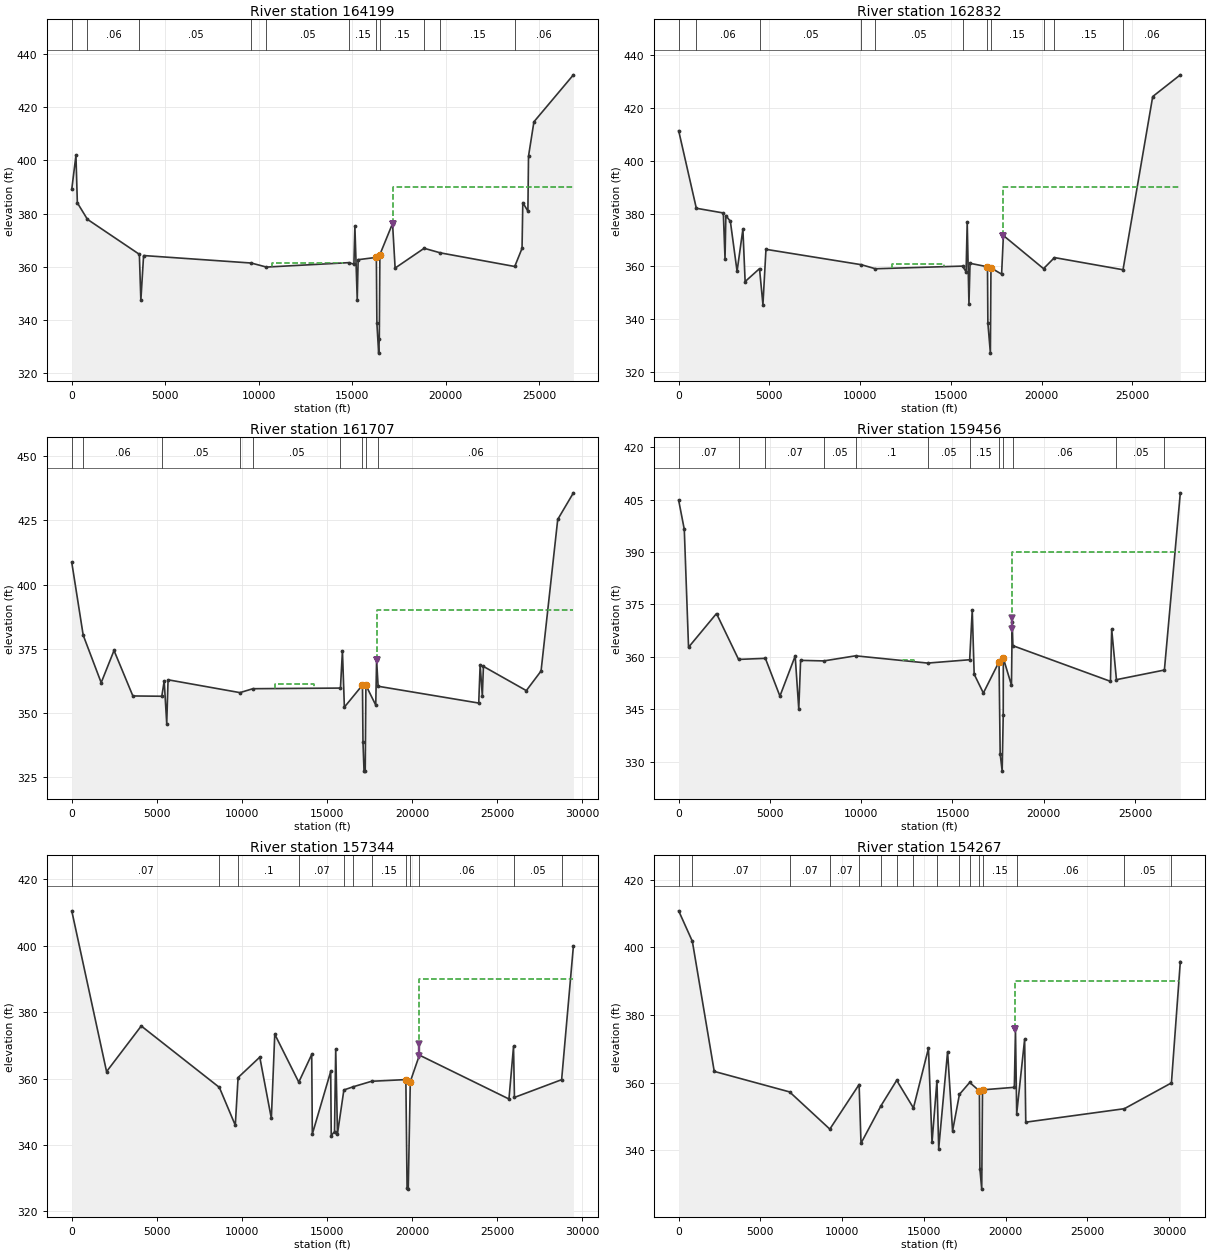
Type RM Length L Ch R = 1 ,164199  ,1428.2,1367.21,1058.58
BEGIN DESCRIPTION:
ROB - Dallas LID1/2
END DESCRIPTION:
XS GIS Cut Line= 4
2572565.59443196 6911360.62073692559008.077070836904842.65198688
2557098.354848616904203.763097992548372.084459926899827.39656934
#Sta/Elev= 30
       0  389.12  224.44  401.91   299.2  384.07  838.45  377.86 3614.19   364.7
 3694.54   347.4 3840.79  364.24 9599.25  361.4210407.14   359.914797.07  361.56
15084.37     36115135.94  375.3115261.81  347.5815310.66  362.6816284.31  363.55
16312.96  338.6816407.93  327.5316441.75  332.9916473.03  364.6117150.04  376.29
17287.03  359.5318838.98  366.9719705.71  365.2523681.46  360.1224072.29  366.94
24113.22  384.1624385.24  380.9324418.55  401.6124708.18  414.55 26818.9  432.22
#Mann= 11 ,-1 , 0
       0     .07       0  838.45     .06       0 3614.19     .05       0
 9599.25      .1       010407.14     .05       014797.07     .15       0
16284.31    .055       016473.03     .15       018838.98     .06       0
19705.71     .15       023681.46     .06       0
Levee=0,,,-1,17150.04,376.29,,
#XS Ineff= 3 ,-1
    5484    8088     362   10730   14485   361.517150.04 26818.9     390
Permanent Ineff=
       F       F       F
Bank Sta=16284.31,16473.03
XS Rating Curve= 0 ,0
Exp/Cntr=0.3,0.1

Type RM Length L Ch R = 1 ,162832  ,930.2,1125.12,1407.97
BEGIN DESCRIPTION:
ROB - Dallas LID1/2
END DESCRIPTION:
XS GIS Cut Line= 4
2573672.057226476910324.489491232559342.144032026903463.29157455
2557416.102365356902900.791574552548203.307226456899716.85060233
#Sta/Elev= 30
       0  411.45  972.85  382.03 2460.75  380.24 2553.94  362.85 2600.63  379.25
 2848.45  377.07 3218.18  358.12 3539.16   374.1 3661.86  354.22 4454.66  359.13
 4643.12  345.45 4809.96  366.4510064.97  360.6210841.67  359.0815640.54  360.09
 15836.7  357.9115899.03  376.7915994.62  345.6716055.16  361.1517016.16  359.83
17037.44  338.4917175.73  327.0817207.69  359.4217793.92  357.0317892.38  371.69
20104.77  359.1220707.46  363.3224483.67   358.726120.06   424.427641.74  432.64
#Mann= 11 ,-1 , 0
       0     .07       0  972.85     .06       0 4454.66     .05       0
10064.97      .1       010841.67     .05       015640.54     .15       0
17016.16    .055       017207.69     .15       020104.77     .06       0
20707.46     .15       024483.67     .06       0
Levee=0,,,-1,17892.38,371.69,,
#XS Ineff= 3 ,-1
    7382    7795   361.5   11742   14636     36117892.3827641.74     390
Permanent Ineff=
       F       F       F
Bank Sta=17016.16,17207.69
XS Rating Curve= 0 ,0
Exp/Cntr=0.3,0.1

Type RM Length L Ch R = 1 ,161707  ,1287.44,2251.17,2226.65
BEGIN DESCRIPTION:
ROB - Dallas LID1/2
END DESCRIPTION:
XS GIS Cut Line= 4
 2573919.27944876909528.308935682559622.057226476902553.30893567
2557775.182226466901729.35060234 2547235.25167096896976.22560234
#Sta/Elev= 30
       0  408.66  673.33  380.22 1730.72  361.68 2484.87  374.25 3593.53   356.5
  5294.1  356.39 5435.28  362.36 5583.78  345.73 5662.01  362.81 9889.96   357.8
10646.13  359.3315796.61  359.5815913.21  374.1116027.77  352.1317091.24  360.75
17121.09  338.5217183.35  327.1617253.35  327.1617293.04  360.6817871.87  352.93
17921.79  370.6318010.71  360.2923925.79  353.7324009.32  368.6724137.73  356.47
24200.98  368.0426724.05  358.5927590.31  366.2428570.23  425.41 29492.4  435.79
#Mann= 9 ,-1 , 0
       0     .07       0  673.33     .06       0  5294.1     .05       0
 9889.96      .1       010646.13     .05       015796.61     .15       0
17091.24    .055       017293.04     .15       018010.71     .06       0
Levee=0,,,-1,17921.79,370.63,,
#XS Ineff= 2 ,-1
   11923   14223     36117921.79 29492.4     390
Permanent Ineff=
       F       F
Bank Sta=17091.24,17293.04
XS Rating Curve= 0 ,0
Exp/Cntr=0.3,0.1

Type RM Length L Ch R = 1 ,159456  ,1796.97,2111.7,856.13
BEGIN DESCRIPTION:
ROB - Dallas LID1/2
END DESCRIPTION:
XS GIS Cut Line= 4
2574022.578059816909063.899213462559391.791022766900614.24643568
2558348.966948696899676.746435672550237.855837576895365.98254678
#Sta/Elev= 30
       0  404.85   307.8  396.52  540.76  362.74 2072.69   372.4  3282.1  359.26
 4750.08  359.57  5546.9  348.75 6383.02  360.23 6580.04  345.05  6680.2  358.99
  7953.6  358.83 9688.69  360.2913642.18  358.2115942.82  359.1716083.73  373.43
16189.08  355.0216691.93  349.6317550.99  358.5817613.52  332.1917722.64  327.26
17780.74  343.2917786.32  359.6118232.31  351.8818272.77  369.9518310.25  363.19
23654.16  352.9823722.66  367.87 23983.2  353.4626610.13  356.2227483.23  406.98
#Mann= 12 ,-1 , 0
       0     .07       0  3282.1     .06       0 4750.08     .07       0
  7953.6     .05       0 9688.69      .1       013642.18     .05       0
15942.82     .15       017550.99    .055       017786.32     .15       0
18310.25     .06       0 23983.2     .05       026610.13     .06       0
Levee=0,,,-1,18283.99,371.07,,
#XS Ineff= 2 ,-1
   12289   12883     35918283.9927483.23     390
Permanent Ineff=
       F       F
Bank Sta=17550.99,17786.32
XS Rating Curve= 0 ,0
Exp/Cntr=0.3,0.1

Type RM Length L Ch R = 1 ,157344  ,948.05,3077.14,2486.59
BEGIN DESCRIPTION:
ROB - Dallas LID1/2
END DESCRIPTION:
XS GIS Cut Line= 4
2576124.256300566909043.413102352560240.402133886898849.66310234
2558682.068800546898932.996435672550808.120060356894467.16161053
#Sta/Elev= 30
       0  410.53 2046.93  362.09 4085.18  375.84 8675.15  357.34 9612.65  345.92
 9776.27   360.311051.82  366.4511732.16  347.9811932.42  373.3613343.42  358.91
14104.43  367.2614140.35  343.2815220.16  362.1415252.47  342.7815444.82  344.04
   15515   368.915619.05  343.3915994.19  356.5616544.95  357.5317624.69  359.18
19638.15  359.6919708.99  327.0119777.38  326.6919898.87  359.0920434.58  367.06
 25698.6  353.8425966.05  369.68 26020.1  354.3228793.51  359.66 29486.2  399.98
#Mann= 12 ,-1 , 0
       0     .07       0 8675.15     .07       0 9776.27      .1       0
13343.42     .07       015994.19     .05       016544.95     .07       0
17624.69     .15       019638.15    .055       019898.87     .15       0
20434.58     .06       0 26020.1     .05       028793.51     .06       0
Levee=0,,,-1,20414.93,370.51,,
#XS Ineff= 2 ,-1
       0 4085.18  375.8420414.93 29486.2     390
Permanent Ineff=
       F       F
Bank Sta=19638.15,19898.87
XS Rating Curve= 0 ,0
Exp/Cntr=0.3,0.1

Type RM Length L Ch R = 1 ,154267  ,2928.63,3003.32,1020.6
BEGIN DESCRIPTION:
ROB - Dallas LID1/2
END DESCRIPTION:
XS GIS Cut Line= 5
2577683.119930486908112.994882482562017.311695226899122.99645831
2561369.395340146897553.204650392560632.806918296897148.53059098
2550948.498531046894340.13036789
#Sta/Elev= 30
       0   410.8  837.14  401.79 2176.36  363.36 6785.31   357.3 9245.48  346.31
11036.79  359.4911152.87  342.1312375.82  353.2213335.26  360.7214359.38  352.55
15278.67  370.1915496.36  342.3815796.75  360.5815905.35  340.5616448.28  369.19
 16753.2  345.7617172.32  356.5717799.81   360.118394.04  357.59 18423.7  334.59
18536.48  328.5818584.13  357.9120530.15  358.6620600.43  375.7620675.41  350.89
21160.32  372.8521230.31  348.3627259.18  352.3430138.64  359.9630683.54  395.82
#Mann= 16 ,-1 , 0
       0     .07       0  837.14     .07       0 6785.31     .07       0
 9245.48     .07       011036.79      .1       012375.82     .07       0
13335.26      .1       014359.38     .07       015796.75      .1       0
17172.32     .07       017799.81     .15       018394.04    .055       0
18584.13     .15       020675.41     .06       027259.18     .05       0
30138.64     .06       0
Levee=0,,,-1,20600.43,375.76,,
#XS Ineff= 2 ,-1
                        20600.4330683.54     390
Permanent Ineff=
       F       F
Bank Sta=18394.04,18584.13
XS Rating Curve= 0 ,0
Exp/Cntr=0.3,0.1

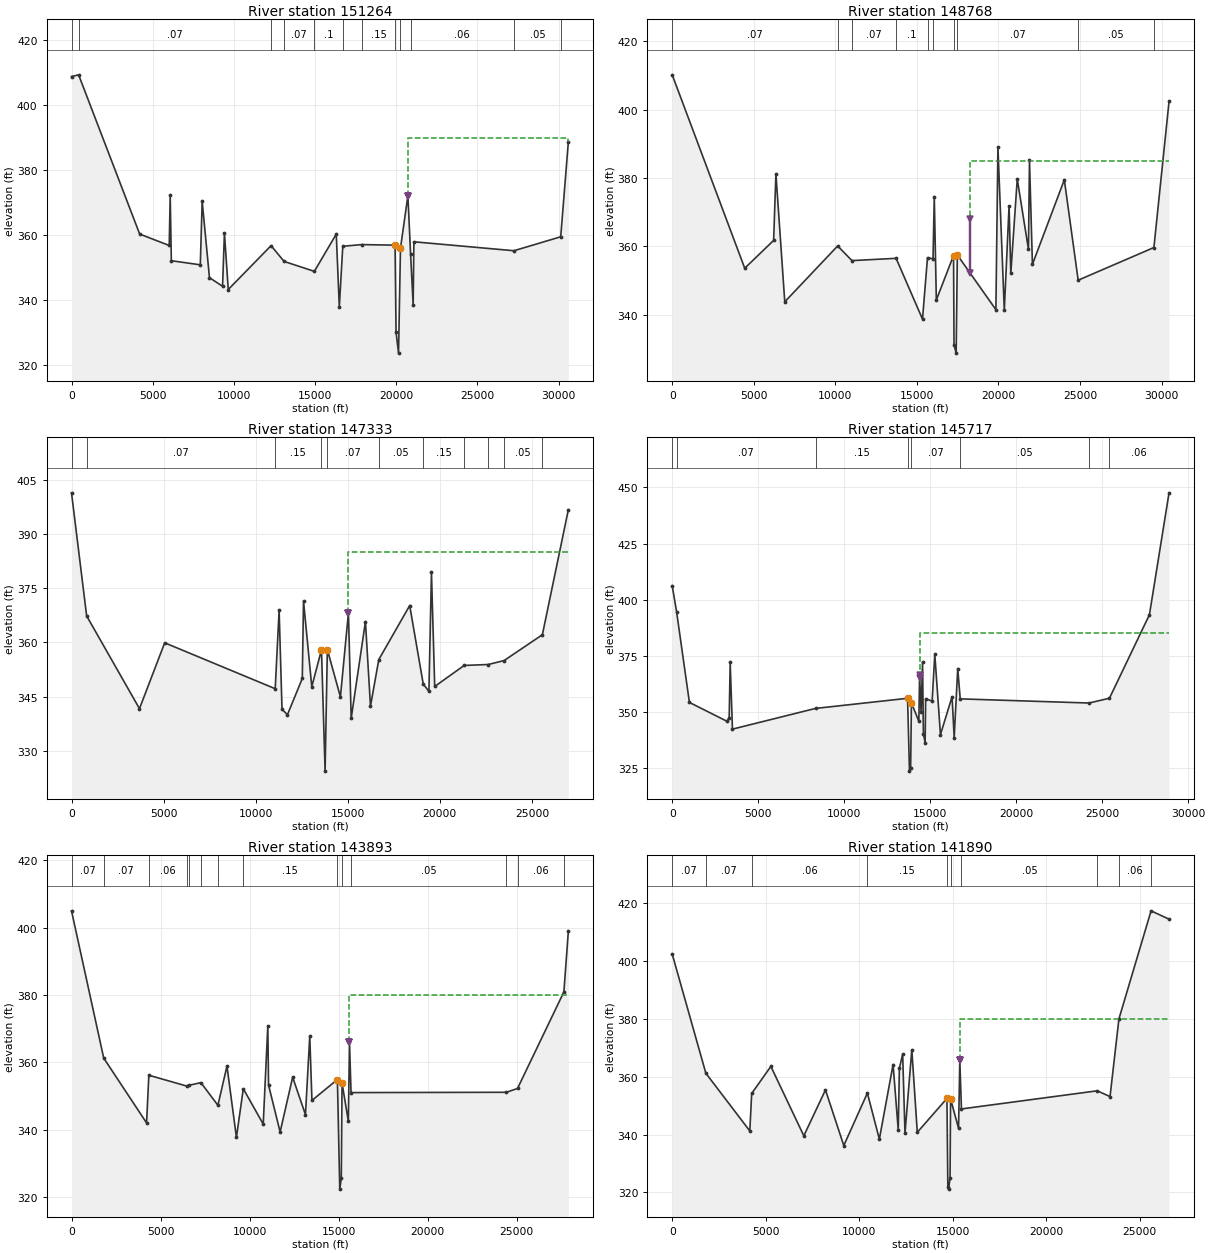
Type RM Length L Ch R = 1 ,151264  ,621.55,2495.98,3306.68
BEGIN DESCRIPTION:
ROB - Dallas LID1/2
END DESCRIPTION:
XS GIS Cut Line= 5
 2578634.50910386906008.828159062562540.853627156895992.51026523
2560824.186784896896009.176898552560782.641592386895987.49255873
2551073.515013316894178.02144015
#Sta/Elev= 30
       0  408.76  437.28  409.29 4197.57  360.34 6017.73  356.82 6077.77   372.2
 6148.51  352.14 7931.23  350.88 8046.75  370.36 8495.57  346.93  9301.6  344.28
 9417.25  360.68 9653.25  343.2912288.91  356.7713090.76  351.9214954.12  348.87
16304.17  360.3216491.45  337.9316705.35  356.5817869.34   357.119925.13  356.92
19985.24  330.1520138.63  323.7320258.42  355.9620714.75  372.1520879.38  354.32
21039.31  338.5921084.29  357.9627246.89  355.2130125.76   359.530595.58  388.68
#Mann= 12 ,-1 , 0
       0     .07       0  437.28     .07       012288.91      .1       0
13090.76     .07       014954.12      .1       016705.35     .07       0
17869.34     .15       019925.13    .055       020258.42     .15       0
20879.38     .06       027246.89     .05       030125.76     .06       0
Levee=0,,,-1,20714.75,372.15,,
#XS Ineff= 2 ,-1
                        20714.7530595.58     390
Permanent Ineff=
       F       F
Bank Sta=19925.13,20258.42
XS Rating Curve= 0 ,0
Exp/Cntr=0.3,0.1

Type RM Length L Ch R = 1 ,148768  ,2180.3,1434.55,1008.26
BEGIN DESCRIPTION:
ROB - Dallas LID14/Ellis LID3
END DESCRIPTION:
XS GIS Cut Line= 4
2577606.524819086904625.264954192563948.885930186896182.44088012
 2562996.10815246894187.996435672552068.006300556888778.94550974
#Sta/Elev= 30
       0   410.2 4445.82  353.59 6217.95  361.73 6357.72  381.24 6900.93  343.76
10144.33  360.1111018.73  355.8213727.42  356.4915344.99  338.6915651.79  356.69
15990.23  356.33 16066.7  374.5416193.44   344.317248.37  357.3117277.84  331.16
17408.81  328.7417480.52  357.4719844.38  341.4719969.15     38920360.09  341.27
 20652.3  371.7820758.15  352.0521154.15  379.7221840.75  359.1421903.79  385.29
22083.69  354.7224039.39  379.4624889.55  350.0929531.82  359.6530460.41  402.43
#Mann= 10 ,-1 , 0
       0     .07       010144.33      .1       011018.73     .07       0
13727.42      .1       015651.79     .07       015990.23     .15       0
17248.37    .055       017480.52     .07       024889.55     .05       0
29531.82     .06       0
Levee=0,,,-1,18258.25,368.05,,
#XS Ineff= 2 ,-1
                        18258.2530460.41     385
Permanent Ineff=
       F       F
Bank Sta=17248.37,17480.52
XS Rating Curve= 0 ,0
Exp/Cntr=0.3,0.1

Type RM Length L Ch R = 1 ,147333  ,1522.48,1615.72,1708.82
BEGIN DESCRIPTION:
ROB - Dallas LID14/Ellis LID3
END DESCRIPTION:
XS GIS Cut Line= 2
2576276.933184796900889.164637482552908.284078336887410.88995419
#Sta/Elev= 30
       0  401.37  822.29  367.34 3690.28  341.71  5060.3  359.9111061.22  347.22
11272.42  368.9211430.28  341.5411723.82  340.0312531.27  350.0512596.91  371.45
13046.23  347.7713573.14  357.9713769.15  324.44 13891.7  358.0314601.28  344.96
15036.43  368.2115185.93  339.0415959.54  365.7716234.04   342.416684.98  355.28
18363.08  370.2119098.34  348.5219406.18  346.4919544.29  379.3819721.06  347.84
21322.53  353.6622624.37  353.9123487.85     35525566.94  362.1426977.04  396.71
#Mann= 11 ,-1 , 0
       0     .07       0  822.29     .07       011061.22     .15       0
13573.14    .055       0 13891.7     .07       016684.98     .05       0
19098.34     .15       021322.53     .05       022624.37     .08       0
23487.85     .05       025566.94     .06       0
Levee=0,,,-1,15036.43,368.21,,
#XS Ineff= 2 , 0
       0                15036.43       0     385
Permanent Ineff=
       F       F
Bank Sta=13573.14,13891.7
XS Rating Curve= 0 ,0
Exp/Cntr=0.3,0.1

Type RM Length L Ch R = 1 ,145717  ,2352.85,1824.58,1766.13
BEGIN DESCRIPTION:
ROB - Dallas LID14/Ellis LID3
END DESCRIPTION:
XS GIS Cut Line= 3
2576750.617863126899723.127008332562501.812617966891032.92161155
2552179.679563736884538.09631899
#Sta/Elev= 30
       0   406.2  255.83  394.59  999.97  354.31 3176.04  345.95 3312.42  347.44
 3370.76  372.11 3501.63  342.43 8331.41  351.6413682.74  356.1513794.34  323.75
13862.02  325.09 13907.7  354.1414338.01  345.9414382.71   366.314470.26  349.86
14554.33  372.1914603.38  340.3214704.13  336.4414734.37   355.9 15112.4  354.91
15266.05  375.7215595.33  339.9916270.53  356.8516393.24  338.6316600.02  369.38
16744.27  355.8924236.03  354.0425420.18  356.1827744.78  393.3128885.25  447.54
#Mann= 8 ,-1 , 0
       0     .07       0  255.83     .07       0 8331.41     .15       0
13682.74    .055       0 13907.7     .07       016744.27     .05       0
24236.03     .15       025420.18     .06       0
Levee=0,,,-1,14387.71,366.38,,
#XS Ineff= 2 , 0
       0                14387.71       0     385
Permanent Ineff=
       F       F
Bank Sta=13682.74,13907.7
XS Rating Curve= 0 ,0
Exp/Cntr=0.3,0.1

Type RM Length L Ch R = 1 ,143893  ,1386.21,2002.89,2192.25
BEGIN DESCRIPTION:
ROB - Dallas LID14/Ellis LID3
END DESCRIPTION:
XS GIS Cut Line= 4
2578362.103522786898989.489491232566872.207689446891416.57282456
2565204.464633896890648.517269012554808.631300566884061.71171345
#Sta/Elev= 30
       0  405.02  1809.1  361.27 4215.91  342.01 4343.07  356.18 6490.13  352.93
 6578.34  353.16 7266.71  353.98 8222.76  347.25 8731.12   358.9 9262.43  337.71
 9648.58  352.1610767.26  341.6611025.21  370.8311066.73  353.24 11716.3  339.32
12420.42  355.5813139.14  344.4713381.12  367.8213503.12  348.69   14933   354.9
15066.51  322.34 15152.1  325.5115195.09  353.8415548.36  342.5115611.78  366.16
15700.22  351.0224423.11  351.1125048.71  352.2427653.42  380.9327904.03  398.92
#Mann= 14 ,-1 , 0
       0     .07       0  1809.1     .07       0 4343.07     .06       0
 6490.13     .07       0 6578.34     .06       0 7266.71     .07       0
 8222.76     .06       0 9648.58     .15       0   14933    .055       0
15195.09     .15       015700.22     .05       024423.11      .1       0
25048.71     .06       027653.42     .06       0
Levee=0,,,-1,15611.78,366.16,,
#XS Ineff= 2 , 0
       0                15611.78       0     380
Permanent Ineff=
       F       F
Bank Sta=14933,15195.09
XS Rating Curve= 0 ,0
Exp/Cntr=0.3,0.1

Type RM Length L Ch R = 1 ,141890  ,652.55,2664.82,1441.16
BEGIN DESCRIPTION:
ROB - Dallas LID14/Ellis LID3
END DESCRIPTION:
XS GIS Cut Line= 4
2578488.353522786898883.58671344 2568553.35641636890829.58063706
2566718.041022786889165.878380122557641.131300556882425.25338011
#Sta/Elev= 30
       0  402.43 1800.06   361.2 4150.41  341.24 4251.12   354.2  5275.6  363.58
 7039.13  339.56 8196.75  355.43 9176.52  336.19 10438.1  354.3411079.09   338.4
11813.32  364.2312088.64  341.5712149.99  362.9412325.52  367.7812449.91  340.47
12814.72  369.3113108.45  340.7814693.74  352.4914741.93  321.7114782.41  321.12
14860.21  325.1114888.41  352.25   15314  342.1715382.57  365.6215468.64  348.86
22731.81  355.1323416.95  353.1423891.33  379.9925611.27  417.39 26572.7   414.5
#Mann= 10 ,-1 , 0
       0     .07       0 1800.06     .07       0 4251.12     .06       0
 10438.1     .15       014693.74    .055       014888.41     .15       0
15468.64     .05       022731.81     .06       023891.33     .06       0
25611.27     .06       0
Levee=0,,,-1,15382.57,365.62,,
#XS Ineff= 2 , 0
       0                15382.57       0     380
Permanent Ineff=
       F       F
Bank Sta=14693.74,14888.41
XS Rating Curve= 0 ,0
Exp/Cntr=0.3,0.1

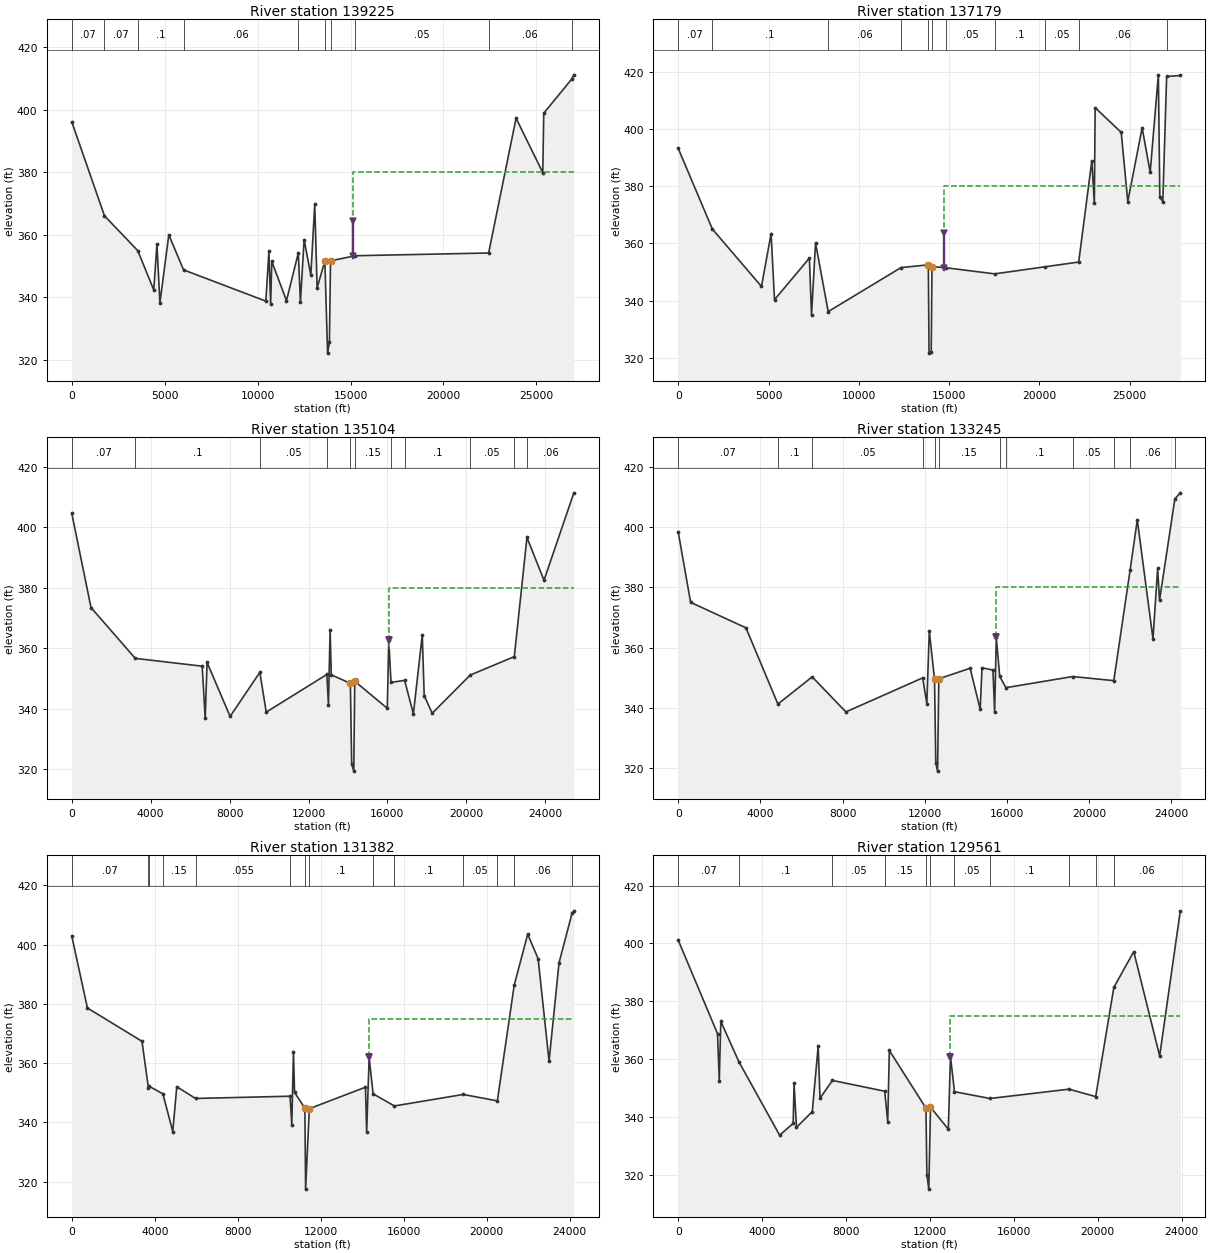
Type RM Length L Ch R = 1 ,139225  ,2176.74,2045.8,1473.69
BEGIN DESCRIPTION:
ROB - Dallas LID14/Ellis LID3
END DESCRIPTION:
XS GIS Cut Line= 5
2580054.216385846898561.619567212569420.297967226890896.57282456
2569022.728522786889783.725602332568733.911971856889067.08063706
2559482.337673346881500.95068294
#Sta/Elev= 30
       0  396.08 1759.93  366.06 3551.36  354.94 4412.54  342.38  4582.4  356.97
 4742.74  338.24 5221.17  360.01 6013.33  348.8110441.95  338.8210607.14   354.7
10700.41  337.8110761.86  351.4911552.72  338.9912190.13  354.2212301.86  338.47
 12501.8  358.4812862.34   347.113073.38  369.7213201.59  343.0413618.32  351.66
13764.12  322.2113861.47  325.6113921.57  351.6915260.04  353.3222429.54  354.19
23905.14  397.2425342.24  379.8825395.36  398.8526903.19  409.7527014.43   411.1
#Mann= 10 ,-1 , 0
       0     .07       0 1759.93     .07       0 3551.36      .1       0
 6013.33     .06       012190.13     .15       013618.32    .055       0
13921.57     .15       015260.04     .05       022429.54     .06       0
26903.19     .05       0
Levee=0,,,-1,15128.06,364.44,,
#XS Ineff= 2 , 0
       0                15128.06       0     380
Permanent Ineff=
       F       F
Bank Sta=13618.32,13921.57
XS Rating Curve= 0 ,0
Exp/Cntr=0.3,0.1

Type RM Length L Ch R = 1 ,137179  ,1988.3,2074.85,2404.85
BEGIN DESCRIPTION:
ROB - Dallas LID14/Ellis LID3
END DESCRIPTION:
XS GIS Cut Line= 2
2581101.955804856897688.613708642559828.689956316879779.65028662
#Sta/Elev= 30
       0  393.14 1885.94  365.03  4609.3  344.95 5143.27   363.4 5331.64  340.32
  7263.9  354.84 7382.41  334.95 7604.47  360.17 8305.71  336.1612339.54  351.54
13851.67  352.4913891.11  321.66 14010.4  322.04 14055.2   351.914829.02  351.47
17529.78  349.3420308.99  351.8122180.46  353.4722907.18  388.8323046.43  374.04
23091.54  407.3724534.58  398.7724898.53  374.5825694.94  400.35 26138.2   384.8
26591.84  418.8526673.43  376.2526837.38  374.5127051.21  418.2727807.95  418.62
#Mann= 11 ,-1 , 0
       0     .07       0 1885.94      .1       0 8305.71     .06       0
12339.54     .15       013851.67    .055       0 14055.2     .15       0
14829.02     .05       017529.78      .1       020308.99     .05       0
22180.46     .06       027051.21     .05       0
Levee=0,,,-1,14714.5,363.6,,
#XS Ineff= 2 , 0
       0                 14714.5       0     380
Permanent Ineff=
       F       F
Bank Sta=13851.67,14055.2
XS Rating Curve= 0 ,0
Exp/Cntr=0.3,0.1

Type RM Length L Ch R = 1 ,135104  ,1573.64,1859.49,1698.1
BEGIN DESCRIPTION:
ROB - Dallas LID14/Ellis LID3
END DESCRIPTION:
XS GIS Cut Line= 4
 2582536.83044336896710.411491352572529.409657046888196.18943335
2571674.374934826886894.974155572563718.53002741 6879660.5412852
#Sta/Elev= 30
       0  404.66  975.72  373.49 3219.69  356.68 6611.98   354.1 6763.34  336.82
 6858.08  355.34 8025.49  337.48 9533.62  352.06 9856.99   338.912929.63  351.36
13010.82  341.3113094.66  366.0913154.63  351.2414122.17  348.4214187.93  321.73
14293.16  319.3814345.25  349.1115992.55  340.1716070.54   362.716182.41  348.74
16871.52   349.417316.75  338.3417766.38  364.4717864.29  344.3418269.85  338.52
20196.52  351.1622432.12  357.2623072.47   396.723936.33   382.525449.53  411.45
#Mann= 11 ,-1 , 0
       0     .07       0 3219.69      .1       0 9533.62     .05       0
12929.63     .15       014122.17    .055       014345.25     .15       0
16182.41     .05       016871.52      .1       020196.52     .05       0
22432.12     .06       023072.47     .06       0
Levee=0,,,-1,16070.54,362.7,,
#XS Ineff= 2 , 0
       0                16060.55       0     380
Permanent Ineff=
       F       F
Bank Sta=14122.17,14345.25
XS Rating Curve= 0 ,0
Exp/Cntr=0.3,0.1

Type RM Length L Ch R = 1 ,133245  ,1421.06,1862.89,859.67
BEGIN DESCRIPTION:
ROB - Dallas LID14/Ellis LID3
END DESCRIPTION:
XS GIS Cut Line= 4
2583349.971217766895215.749990182573768.877249636887647.78086853
2573663.182805196886553.753090752565391.637884436879090.74999018
#Sta/Elev= 30
       0  398.35   602.8  375.05  3297.8   366.6 4852.94  341.34 6522.78  350.35
  8164.1  338.7311903.46  350.0212105.59  341.4712224.68  365.5512480.25  349.65
12541.74  321.7812628.18  319.1112690.26  349.7114214.83  353.2114704.48  339.59
14791.81  353.3615326.07  352.62 15406.5  338.6415488.41  363.4615653.89  350.54
15958.05  346.7719208.68  350.4621210.16   349.122006.64  385.8322354.15  402.38
 23118.1  362.9723345.48   386.323437.44  375.7524184.88  409.3824449.29  411.35
#Mann= 12 ,-1 , 0
       0     .07       0 4852.94      .1       0 6522.78     .05       0
11903.46     .15       012480.25    .055       012690.26     .15       0
15653.89     .05       015958.05      .1       019208.68     .05       0
21210.16      .1       022006.64     .06       024184.88     .05       0
Levee=0,,,-1,15488.41,363.46,,
#XS Ineff= 2 , 0
       0                15488.41       0     380
Permanent Ineff=
       F       F
Bank Sta=12480.25,12690.26
XS Rating Curve= 0 ,0
Exp/Cntr=0.3,0.1

Type RM Length L Ch R = 1 ,131382  ,1497.01,1820.98,1004.37
BEGIN DESCRIPTION:
ROB - Dallas LID14/Ellis LID3
END DESCRIPTION:
XS GIS Cut Line= 4
2584317.349471856894327.364201862575937.488360746887689.86420186
2575304.155027416886867.64197964 2565867.59982616878713.40774316
#Sta/Elev= 30
       0  402.91  754.96  378.64 3384.72   367.4 3691.95   351.8 3726.55  352.24
 4392.35  349.66 4867.98  336.94  5061.3  352.06 5964.83  348.11 10522.3  348.86
 10605.5  339.1910685.22  363.9510738.01  350.1611235.91  344.8311269.98   317.5
11450.27  344.6514155.48  351.91 14213.2  336.8814333.52  361.9514524.14  349.67
15552.36  345.57 18867.2  349.4620512.32  347.2921326.36  386.3821975.55  403.56
22477.45  395.2823005.03  360.7223485.15  393.8724110.71  410.5624199.55  411.44
#Mann= 14 ,-1 , 0
       0     .07       0 3691.95      .1       0 3726.55     .07       0
 4392.35     .15       0 5964.83    .055       0 10522.3     .15       0
11235.91    .055       011450.27      .1       014524.14     .05       0
15552.36      .1       0 18867.2     .05       020512.32      .1       0
21326.36     .06       024110.71     .05       0
Levee=0,,,-1,14333.52,361.95,,
#XS Ineff= 2 , 0
       0                14333.52       0     375
Permanent Ineff=
       F       F
Bank Sta=11235.91,11450.27
XS Rating Curve= 0 ,0
Exp/Cntr=0.3,0.1

Type RM Length L Ch R = 1 ,129561  ,712.19,2450.97,1729.68
BEGIN DESCRIPTION:
ROB - Dallas LID14/Ellis LID3
END DESCRIPTION:
XS GIS Cut Line= 5
2584901.377249636892811.391979632576986.909657046886702.86188705
2576359.13187926 6885420.91744262575429.270768156885568.83410927
2566232.183159436878557.15774316
#Sta/Elev= 30
       0  401.13 1872.04  368.87 1955.56  352.69 2028.68  373.11 2893.87  359.14
 4832.74  333.84 5479.59  337.92 5519.86  351.82 5635.94  336.55  6389.1  341.98
 6670.49  364.54 6757.04   346.6  7350.2  352.74 9841.16  349.02 9985.82  338.51
10062.62  363.0711808.27  343.1711852.09  320.22 11943.3  315.23 12024.1  343.53
12874.15  335.8912976.12  360.9713167.68  348.8514860.51  346.5118624.95  349.72
19897.79  347.1620764.35  384.8521712.11  397.1922946.95  361.2223931.62  411.27
#Mann= 11 ,-1 , 0
       0     .07       0 2893.87      .1       0  7350.2     .05       0
 9841.16     .15       011808.27    .055       0 12024.1     .15       0
13167.68     .05       014860.51      .1       018624.95     .05       0
19897.79      .1       020764.35     .06       0
Levee=0,,,-1,12976.12,360.97,,
#XS Ineff= 2 , 0
       0                12976.12       0     375
Permanent Ineff=
       F       F
Bank Sta=11808.27,12024.1
XS Rating Curve= 0 ,0
Exp/Cntr=0.3,0.1