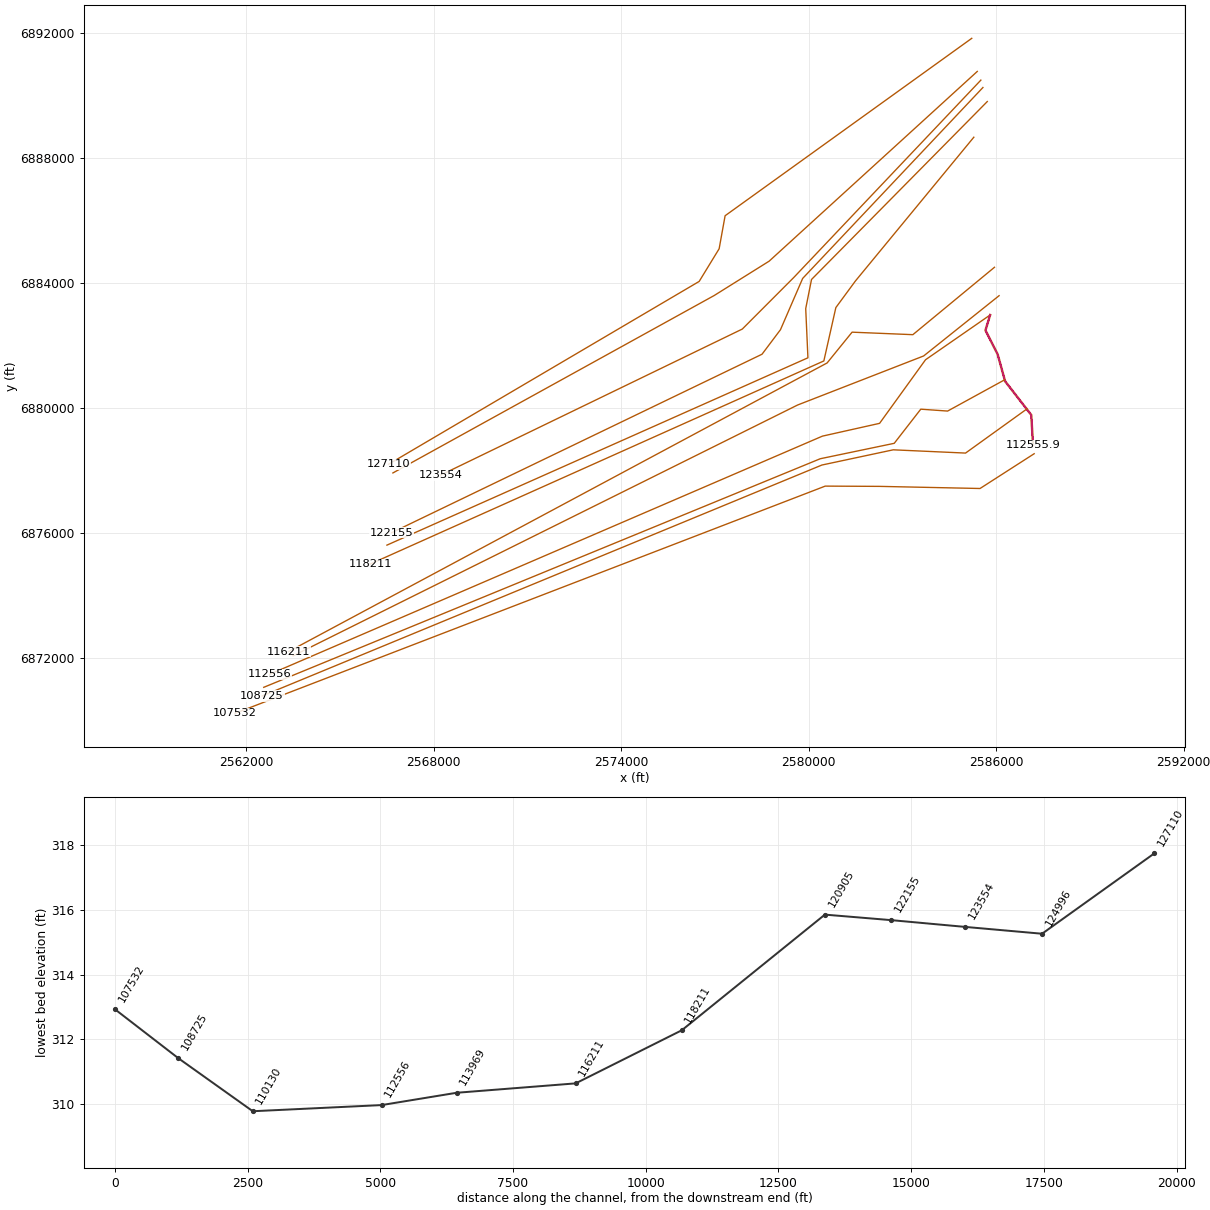
HEC-RAS study TR_FEMA.prj: Trinity_River_FEMA

--- TR_FEMA.g07 (geometry) --- (continued)

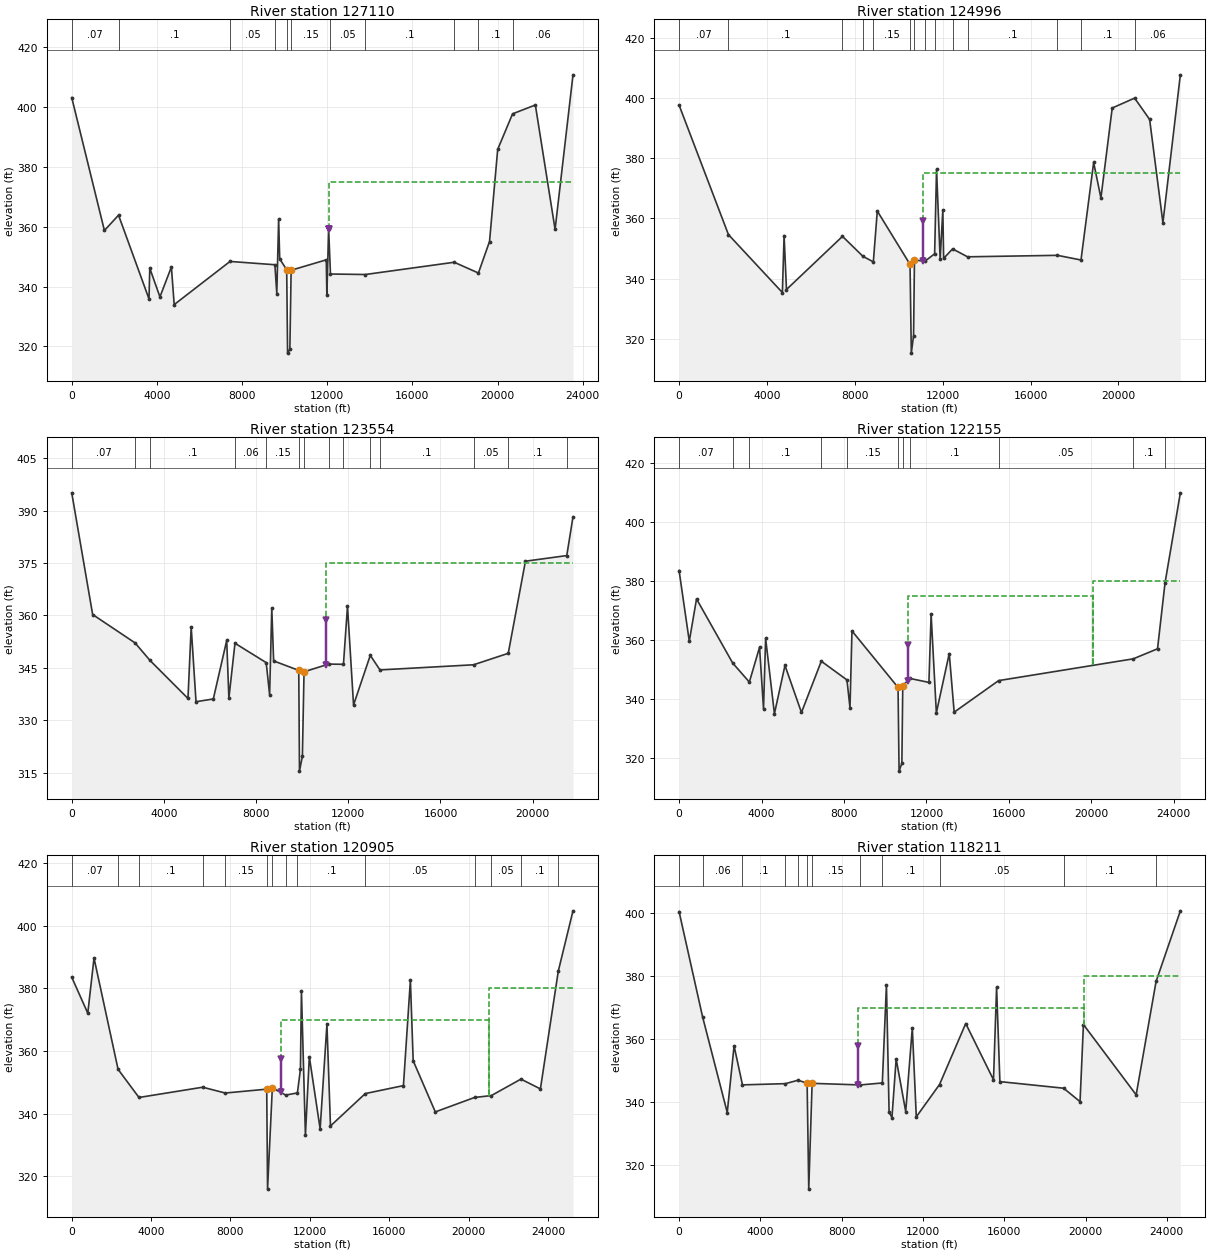
Type RM Length L Ch R = 1 ,127110  ,1790.05,2113.72,648.82
BEGIN DESCRIPTION:
ROB - Dallas LID14/Ellis LID3
END DESCRIPTION:
XS GIS Cut Line= 5
2585217.20479592 6891834.55748892577327.50572185 6886159.7600352
2577136.649240376885103.446377792576497.76035148 6884058.3074889
2566562.044270546878209.93552094
#Sta/Elev= 30
       0  403.21 1534.94  358.75 2198.55  363.88 3630.38  335.86 3665.79  346.14
 4143.58  336.54 4681.18  346.55 4813.25  333.97 7434.72   348.4 9542.72   347.3
  9632.6  337.64 9718.61  362.54 9769.52  349.2510098.13  345.6210139.04  317.74
10246.55  318.9810305.39  345.4611956.64  348.9411983.88   337.112068.25  359.18
12153.81   344.213789.35  344.0317966.64  348.1319103.62  344.5319625.18  355.07
20009.36  385.8920708.11  397.7721777.79  400.7222704.35  359.1223546.05  410.81
#Mann= 11 ,-1 , 0
       0     .07       0 2198.55      .1       0 7434.72     .05       0
 9542.72     .15       010098.13    .055       010305.39     .15       0
12153.81     .05       013789.35      .1       017966.64     .05       0
19103.62      .1       020708.11     .06       0
Levee=0,,,-1,12068.25,359.18,,
#XS Ineff= 2 , 0
       0                12068.25       0     375
Permanent Ineff=
       F       F
Bank Sta=10098.13,10305.39
XS Rating Curve= 0 ,0
Exp/Cntr=0.3,0.1

Type RM Length L Ch R = 1 ,124996  ,778.22,1442.73,1331.79
BEGIN DESCRIPTION:
ROB - Dallas LID14/Ellis LID3
END DESCRIPTION:
XS GIS Cut Line= 4
2585394.264981116890775.946377792578735.931647786884706.50193334
2576979.681647776883608.585266682566700.933159436877932.15774316
#Sta/Elev= 30
       0  397.63 2246.66  354.63 4703.32  335.38 4780.89  354.32 4889.73  336.39
 7439.97  354.04 8370.86  347.41 8843.92  345.57 9024.18  362.4510515.38  344.73
10573.38  315.2610675.89  321.0910716.75  346.2511183.85  345.72 11635.3  348.25
11722.04  376.3411886.44  346.5212008.34  362.7912045.16  346.7412453.64  349.88
13134.25  347.2517225.42  347.7418299.05  346.1918875.03  378.5919205.62   366.8
19720.69  396.6720740.13  399.9621423.72  392.8822028.93  358.5722822.69  407.69
#Mann= 14 ,-1 , 0
       0     .07       0 2246.66      .1       0 7439.97     .06       0
 8370.86     .05       0 8843.92     .15       010515.38    .055       0
10716.75     .15       011183.85     .05       0 11635.3      .1       0
12453.64     .05       013134.25      .1       017225.42     .05       0
18299.05      .1       020740.13     .06       0
Levee=0,,,-1,11083.76,359.07,,
#XS Ineff= 2 , 0
       0                11083.76       0     375
Permanent Ineff=
       F       F
Bank Sta=10515.38,10716.75
XS Rating Curve= 0 ,0
Exp/Cntr=0.3,0.1

Type RM Length L Ch R = 1 ,123554  ,223.62,1398.9,1040.15
BEGIN DESCRIPTION:
ROB - Dallas LID14/Ellis LID3
END DESCRIPTION:
XS GIS Cut Line= 4
2585509.000037216890498.497733262579526.932805186884187.75193334
2577877.627249636882534.974155562568228.710937216877862.71329872
#Sta/Elev= 30
       0  395.08  907.75  360.27 2748.21  352.15 3397.43  347.13 5044.32  336.26
 5183.41   356.7 5393.26  335.33  6143.7  336.11 6724.73  352.85 6819.31  336.34
 7083.41  352.05 8438.49  346.51 8586.94   337.3 8680.47  362.07 8760.93     347
 9851.44  344.29  9882.4  315.4710008.54   319.710079.93  343.8811146.16  346.09
11790.33  346.0311965.99  362.6212228.57   334.412954.43  348.5813375.61  344.42
17435.15  345.8918941.52  349.1719687.33  375.5221480.53  377.1321750.92  388.22
#Mann= 14 ,-1 , 0
       0     .07       0 2748.21     .06       0 3397.43      .1       0
 7083.41     .06       0 8438.49     .15       0 9851.44    .055       0
10079.93     .15       011146.16     .05       011790.33      .1       0
12954.43     .05       013375.61      .1       017435.15     .05       0
18941.52      .1       021480.53     .06       0
Levee=0,,,-1,11041.08,358.82,,
#XS Ineff= 2 , 0
       0                11041.08       0     375
Permanent Ineff=
       F       F
Bank Sta=9851.44,10079.93
XS Rating Curve= 0 ,0
Exp/Cntr=0.3,0.1

Type RM Length L Ch R = 1 ,122155  ,264.7,1249.35,675.81
BEGIN DESCRIPTION:
ROB - Dallas LID14/Ellis LID3
ROB IFA station 20096: flow expansion due to natural high ground upstream
END DESCRIPTION:
XS GIS Cut Line= 5
2585574.994147786890261.849155572579808.489518156884154.81211854
2579098.767295936882514.534340762578508.489518156881729.81211854
2566666.210937216876022.43552094
#Sta/Elev= 30
       0  383.65  494.88  359.71  846.43  374.04 2600.82  352.31 3408.26  345.86
 3903.21  357.65 4095.35  336.83 4197.44  360.67  4624.4  335.14  5136.3   351.5
 5935.95  335.55 6898.27  352.93 8142.87  346.59 8289.74  337.15 8385.98  363.19
10621.02  344.0510670.96  315.6810806.46  318.3410849.79   344.711204.51  347.08
12118.58  345.7512224.99  368.7712479.21  335.4413104.59  355.5413343.22  335.66
15499.24  346.3622031.38  353.7423207.33  357.14 23572.3  379.5424314.35     410
#Mann= 11 ,-1 , 0
       0     .07       0 2600.82     .06       0 3408.26      .1       0
 6898.27     .06       0 8142.87     .15       010621.02    .055       0
10849.79     .15       011204.51      .1       015499.24     .05       0
22031.38      .1       0 23572.3     .06       0
Levee=0,,,-1,11095.25,358.45,,
#XS Ineff= 3 ,-1
                        11095.25   20096     375   2009624314.35     380
Permanent Ineff=
       F       F       F
Bank Sta=10621.02,10849.79
XS Rating Curve= 0 ,0
Exp/Cntr=0.3,0.1

Type RM Length L Ch R = 1 ,120905  ,976.82,2694.7,313.19
BEGIN DESCRIPTION:
ROB - Dallas LID14/Ellis LID3
ROB IFA station 21033: flow expansion due to natural high ground upstream
END DESCRIPTION:
XS GIS Cut Line= 5
2585714.392295936889812.555174092580091.614518156884120.88850743
2579906.058962596883189.013507422579976.886508896881615.51235001
2566509.960937216875623.12996538
#Sta/Elev= 30
       0  383.56  808.93  372.05 1123.59  389.67 2336.29  354.12 3389.41  345.13
 6601.08  348.41 7738.89  346.55 9828.58  347.79 9870.55  315.8510110.79   348.2
10786.36  345.8911374.55  346.5911527.09   354.111578.13  379.0811778.86  333.04
11975.94  358.1412520.65  335.1112863.31  368.5313041.78  336.0314797.73  346.38
16718.92  348.9217069.88  382.5617210.52  356.8618325.61  340.5220301.79  345.13
 21151.2  345.7422641.51     35123623.41  347.87 24524.3  385.4925265.88  404.76
#Mann= 14 ,-1 , 0
       0     .07       0 2336.29     .06       0 3389.41      .1       0
 6601.08     .06       0 7738.89     .15       0 9828.58    .055       0
10110.79     .15       010786.36     .05       011374.55      .1       0
14797.73     .05       020301.79      .1       0 21151.2     .05       0
22641.51      .1       0 24524.3     .06       0
Levee=0,,,-1,10526.72,357.49,,
#XS Ineff= 3 ,-1
                        10526.72   21033     370   2103325265.88     380
Permanent Ineff=
       F       F       F
Bank Sta=9828.58,10110.79
XS Rating Curve= 0 ,0
Exp/Cntr=0.3,0.1

Type RM Length L Ch R = 1 ,118211  ,2761.13,1999.76,334.75
BEGIN DESCRIPTION:
ROB - Dallas LID14/Ellis LID3
ROB IFA station 19915: flow expansion due to natural high ground upstream
END DESCRIPTION:
XS GIS Cut Line= 5
2585283.489518156888671.588738912581496.568221856884073.32485001
2580869.947851486883221.472998162580486.151555196881514.99151668
2565971.766492776875015.49107649
#Sta/Elev= 30
       0  400.54 1155.44   367.1 2369.85  336.65 2705.98  357.83 3119.07  345.44
  5232.5  345.83    5850  346.91 6300.75  345.99 6380.81  312.28 6546.02  345.93
 8921.03  345.42 10001.1  346.0510203.83  377.2710334.41  336.7610474.72  335.05
10681.82   353.711152.35  336.9611476.65  363.5511672.77  335.2712815.94  345.55
14105.39  364.9615471.42  347.0615624.14  376.4715786.65  346.4818921.67  344.38
19730.73  340.11 19897.3  364.6322492.53  342.2723472.56  378.3424666.69   400.8
#Mann= 12 ,-1 , 0
       0     .07       0 1155.44     .06       0 3119.07      .1       0
  5232.5     .06       0    5850     .15       0 6300.75    .055       0
 6546.02     .15       0 8921.03     .05       0 10001.1      .1       0
12815.94     .05       018921.67      .1       023472.56     .06       0
Levee=0,,,-1,8803.29,357.77,,
#XS Ineff= 3 ,-1
                         8803.29   19915     370   1991524666.69     380
Permanent Ineff=
       F       F       F
Bank Sta=6300.75,6546.02
XS Rating Curve= 0 ,0
Exp/Cntr=0.3,0.1

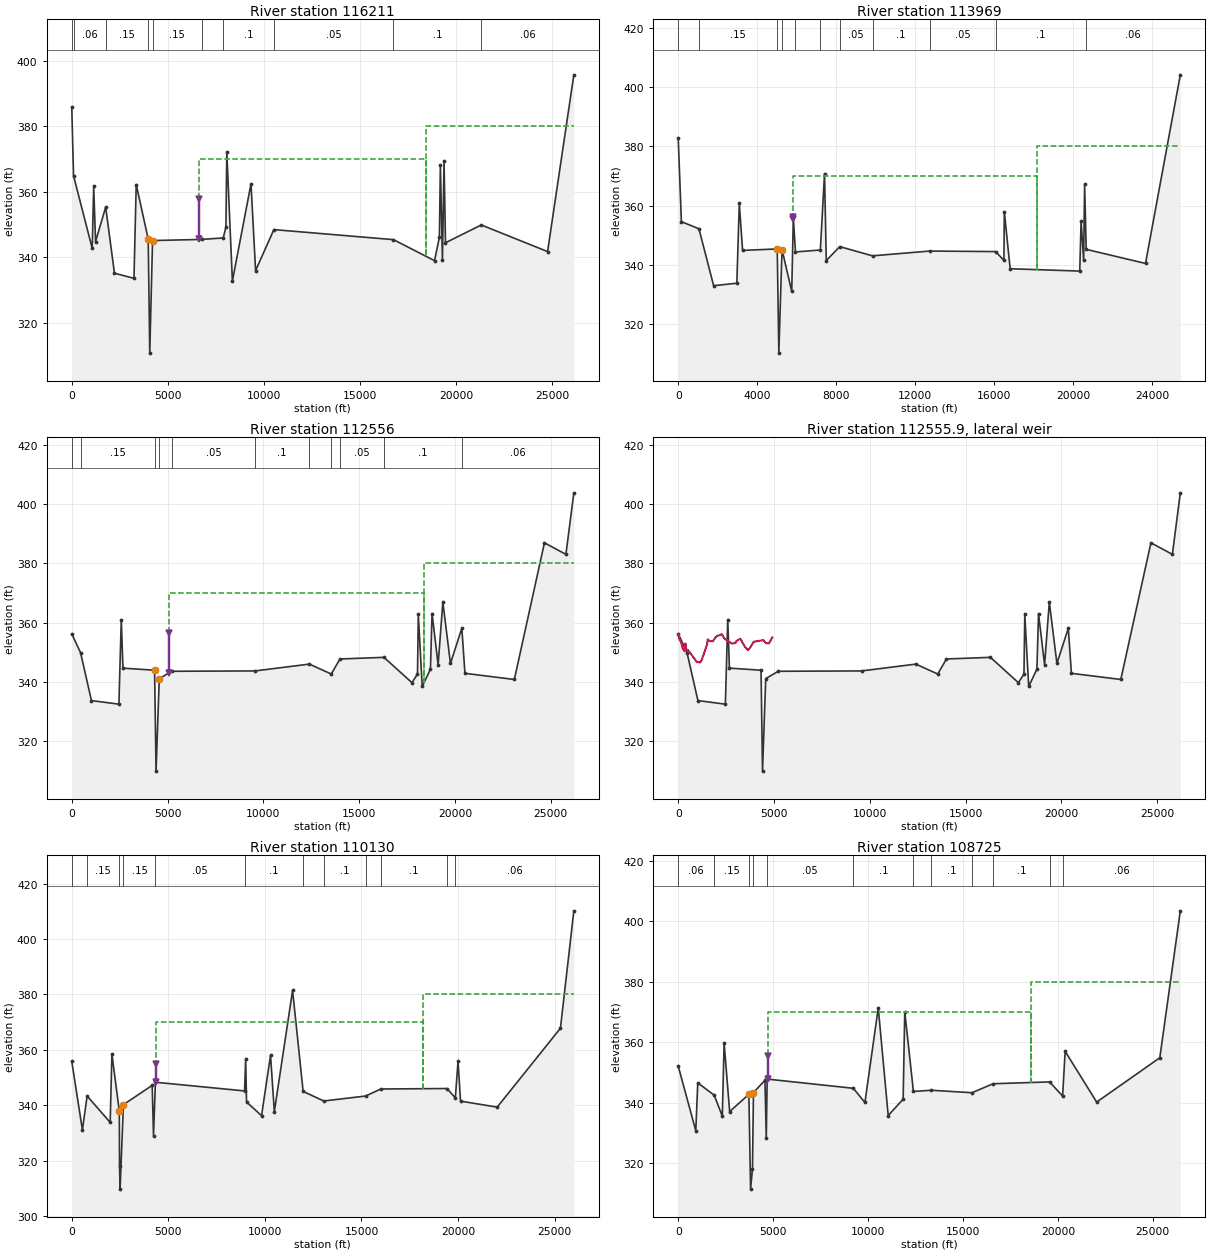
Type RM Length L Ch R = 1 ,116211  ,785.21,2241.73,739.29
BEGIN DESCRIPTION:
ROB - Dallas LID14/Ellis LID3
ROB IFA station 18461: flow expansion due to natural high ground upstream
END DESCRIPTION:
XS GIS Cut Line= 5
     2585944.032     6884510.862     2583333.374     6882355.269
     2581389.228     6882435.162     2580590.329     6881450.457
       2563367.6     6872220.352
#Sta/Elev= 30
       0  385.96   91.21  364.89 1065.04  342.66 1141.18  361.61 1238.75  344.76
 1766.31   355.3 2221.93  335.08 3238.73  333.51  3355.6  362.19 3980.32  345.52
 4060.59  310.64 4205.73  345.06    6757  345.41  7887.7  345.86 8025.89  349.25
 8071.31  372.13 8363.02   332.7 9331.79   362.4 9570.76  335.8810522.81  348.41
   16749  345.3418887.42  338.9119140.57   346.119191.16  368.1219299.06  339.21
19381.64  369.3819457.52  344.3921321.25  349.8324773.52  341.6926140.52  395.74
#Mann= 10 ,-1 , 0
       0     .06       0   91.21     .06       0 1766.31     .15       0
 3980.32    .055       0 4205.73     .15       0    6757     .05       0
  7887.7      .1       010522.81     .05       0   16749      .1       0
21321.25     .06       0
Levee=0,,,-1,6627.08,357.69,,
#XS Ineff= 3 ,-1
                         6627.09   18461     370   1846126140.52     380
Permanent Ineff=
       F       F       F
Bank Sta=3980.32,4205.73
XS Rating Curve= 0 ,0
Exp/Cntr=0.3,0.1

Type RM Length L Ch R = 1 ,113969  ,147.93,1413.33,1346.26
BEGIN DESCRIPTION:
ROB - Dallas LID14/Ellis LID3
ROB IFA station 18189: flow expansion due to natural high ground upstream
END DESCRIPTION:
XS GIS Cut Line= 4
     2586091.755     6883602.693      2583678.94     6881674.698
     2579642.858     6880103.664     2563506.489     6872081.463
#Sta/Elev= 30
       0  382.66   159.6  354.63  1048.5  352.24 1794.21  333.06 2969.13   333.9
  3093.5  360.77 3261.33  344.94 5016.81  345.45 5096.83  310.35 5258.88  345.24
 5750.62  331.14 5831.83  356.07  5940.4  344.43 7201.38  345.08 7412.86  370.84
 7501.14  341.52 8182.78  346.22 9844.37  343.1212740.14  344.7316078.38  344.55
16502.85   341.616522.41  358.0216819.29  338.7720344.84  337.9920413.57  354.79
 20542.7   341.620591.31  367.2820672.55   345.323676.91  340.5625440.86  404.09
#Mann= 11 ,-1 , 0
       0     .06       0  1048.5     .15       0 5016.81    .055       0
 5258.88     .15       0  5940.4     .05       0 7201.38      .1       0
 8182.78     .05       0 9844.37      .1       012740.14     .05       0
16078.38      .1       020672.55     .06       0
Levee=0,,,-1,5836.82,356.19,,
#XS Ineff= 3 ,-1
                         5837.07   18189     370   1818925440.86     380
Permanent Ineff=
       F       F       F
Bank Sta=5016.81,5258.88
XS Rating Curve= 0 ,0
Exp/Cntr=0.3,0.1

Type RM Length L Ch R = 1 ,112556  ,1808.05,2425.98,739.38
BEGIN DESCRIPTION:
ROB - Dallas LID14/Ellis LID3
ROB IFA station 18373: flow expansion due to natural high ground upstream
END DESCRIPTION:
XS GIS Cut Line= 5
       2585804.9     6882984.953     2583737.924     6881552.473
     2582268.896     6879518.792     2580440.598     6879109.695
     2562759.961     6871491.186
#Sta/Elev= 30
       0  356.27   458.5  349.92 1027.81  333.76 2459.89  332.55 2584.82  361.08
 2671.59   344.7 4322.59     344 4399.32  309.97 4567.55  341.17 5218.84  343.64
 9568.96  343.7612403.64  346.0613546.54  342.7214001.42  347.7916296.95  348.34
17757.01   339.818047.48  342.6918090.18  362.7918294.91  338.5318723.42  344.35
18807.48  363.1219124.28  345.8519370.51  366.9519768.17  346.2920362.28  358.15
20523.92  342.9523102.89  340.8824674.92  386.9625794.75  383.0726209.19  403.82
#Mann= 11 ,-1 , 0
       0     .06       0   458.5     .15       0 4322.59    .055       0
 4567.55     .15       0 5218.84     .05       0 9568.96      .1       0
12403.64     .05       013546.54      .1       014001.42     .05       0
16296.95      .1       020362.28     .06       0
Levee=0,,,-1,5083.59,356.56,,
#XS Ineff= 3 ,-1
                         5083.57   18373     370   1837326209.19     380
Permanent Ineff=
       F       F       F
Bank Sta=4322.59,4567.55
XS Rating Curve= 0 ,0
Exp/Cntr=0.3,0.1

Type RM Length L Ch R = 6 ,112555.9,,,
BEGIN DESCRIPTION:
Spill to East Fork
END DESCRIPTION:
Lateral Weir Pos= 0
Lateral Weir End=Trinity River   ,1               ,83613   ,
Lateral Weir Distance=0
Lateral Weir TW Multiple XS=0
Lateral Weir WD=20
Lateral Weir Coef=0.5
LW OverFlow Method 2D=0
LW OverFlow Use Velocity Into 2D=0
Lateral Weir WSCriteria=-1
Lateral Weir Flap Gates= 0
Lateral Weir Hagers EQN= 0 ,,,,,
Lateral Weir SS=0.05,0.05,
Lateral Weir Type= 0
Lateral Weir Connection Pos and Dist= 0 ,
Lateral Weir SE= 30
       0  356.25   76.92  354.18  155.25  353.52  226.46   351.4  332.53  350.37
   371.6  353.03  417.47  350.98  519.04  350.74  981.32   346.7 1150.58  346.62
 1221.44  347.35 1506.54  352.73 1537.82  354.43 1642.26  353.83 1794.16  353.75
 2009.41   355.5 2270.43  356.13 2432.29  354.55 2811.64  352.95 2979.16  353.19
 3034.07  353.86 3240.91  354.64 3472.64  351.98  3631.1  350.78 3789.52  351.93
 3930.46  353.58 4437.52  354.13 4582.53  353.13 4733.05  353.04 4910.31  355.06
Lateral Weir Centerline= 6
2585804.899634426882984.953209122585655.685231036882495.31366737
2586044.505398846881730.24132939 2586284.37446716880864.81887567
2587120.401659916879788.410963742587178.127354356878821.61408874
LW Div RC= 0 ,False,,

Type RM Length L Ch R = 1 ,110130  ,1466.65,1404.73,264.23
BEGIN DESCRIPTION:
ROB - Dallas LID14/Ellis LID3
ROB IFA station 18172: flow expansion due to natural high ground upstream
END DESCRIPTION:
XS GIS Cut Line= 6
     2586262.889     6880907.974     2584444.605     6879911.516
     2583586.604     6879971.917     2582737.646     6878879.903
      2580370.91       6878386.5     2562568.989     6871074.519
#Sta/Elev= 30
       0  355.84  550.58  331.14  795.01  343.36 1988.81  333.85 2078.42   358.5
 2462.45  337.85 2472.91  318.02 2501.58  309.78 2673.18  340.25 4162.76   347.2
 4231.97   329.1 4330.13  348.34 8947.24   345.2 9003.47  356.86 9048.75  341.22
 9825.57  336.2710290.49  358.0610487.69  337.7411432.32  381.4411979.33  345.02
13046.22  341.5715210.35  343.3616001.13   345.919427.69  346.0719858.94  342.69
19999.03  355.9420127.81  341.5222026.83  339.3625299.58  367.8125994.54  410.17
#Mann= 12 ,-1 , 0
       0     .06       0  795.01     .15       0 2462.45    .055       0
 2673.18     .15       0 4330.13     .05       0 8947.24      .1       0
11979.33     .05       013046.22      .1       015210.35     .05       0
16001.13      .1       019427.69     .05       019858.94     .06       0
Levee=0,,,-1,4345.46,354.96,,
#XS Ineff= 3 ,-1
                         4345.07   18172     370   1817225994.54     380
Permanent Ineff=
       F       F       F
Bank Sta=2462.45,2673.18
XS Rating Curve= 0 ,0
Exp/Cntr=0.3,0.1

Type RM Length L Ch R = 1 ,108725  ,1186.89,1193.33,695.83
BEGIN DESCRIPTION:
ROB - Dallas LID14/Ellis LID3
ROB IFA station 18591: flow expansion due to natural high ground upstream
END DESCRIPTION:
XS GIS Cut Line= 5
     2586988.651     6879984.728     2585018.827      6878567.75
     2582706.327     6878671.917     2580424.382     6878185.459
     2562516.905     6870796.741
#Sta/Elev= 30
       0  352.13  924.84  330.74 1028.29  346.59 1893.33  342.52    2322  335.58
 2416.54  359.83  2708.8  337.08 3721.05  342.79  3811.2  311.42 3911.73  318.19
 3962.76  343.37 4569.42  347.46 4637.55  328.23 4684.98  347.84 9222.72  344.79
 9834.86   340.110537.58  371.4111061.39  335.7811848.95  341.1911932.97  370.14
 12390.1  343.7413336.15  344.1415477.19  343.3216586.04   346.319563.45   346.9
20250.32  342.2220382.85  357.0322043.72  340.2225369.97   354.926449.92  403.52
#Mann= 12 ,-1 , 0
       0     .06       0 1893.33     .15       0 3721.05    .055       0
 3962.76     .15       0 4684.98     .05       0 9222.72      .1       0
 12390.1     .05       013336.15      .1       015477.19     .05       0
16586.04      .1       019563.45     .05       020250.32     .06       0
Levee=0,,,-1,4719.96,355.32,,
#XS Ineff= 3 ,-1
                         4720.04   18591     370   1859126449.92     380
Permanent Ineff=
       F       F       F
Bank Sta=3721.05,3962.76
XS Rating Curve= 0 ,0
Exp/Cntr=0.3,0.1

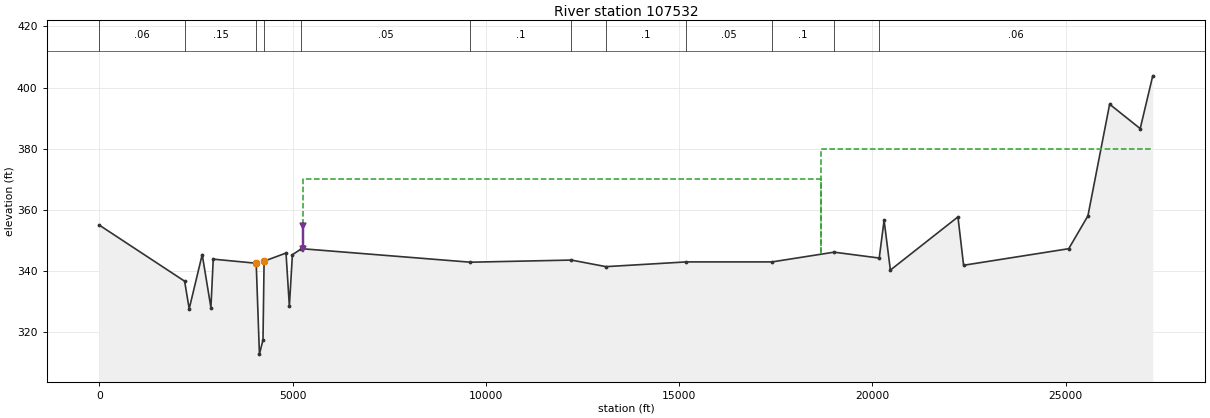
Type RM Length L Ch R = 1 ,107532  ,1037.27,3183.75,659.24
BEGIN DESCRIPTION:
ROB - Dallas LID14/Ellis LID3
ROB IFA station 18676: flow expansion due to natural high ground upstream
END DESCRIPTION:
XS GIS Cut Line= 5
     2587214.015     6878546.995     2585482.484     6877434.648
     2582272.183     6877502.519     2580529.243     6877510.806
      2561648.85     6870241.186
#Sta/Elev= 30
       0  355.06  2206.6  336.75 2324.95  327.73 2661.98  345.45 2886.92  328.11
 2946.88  343.95 4058.67  342.61 4141.97  312.93 4234.63  317.57 4262.58  343.29
 4830.06  345.94 4916.76   328.6  4995.3  345.38 5229.58  347.37 9602.06  342.95
12212.69  343.6513108.48   341.515191.19  343.0517405.58  343.05 19010.2  346.23
20178.41  344.3120304.07  356.6320466.76  340.3822215.42  357.75 22361.1  341.95
25081.37  347.3625577.96  358.0826139.72  394.5526930.64  386.5827255.17  403.82
#Mann= 12 ,-1 , 0
       0     .06       0  2206.6     .15       0 4058.67    .055       0
 4262.58     .15       0 5229.58     .05       0 9602.06      .1       0
12212.69     .05       013108.48      .1       015191.19     .05       0
17405.58      .1       0 19010.2     .05       020178.41     .06       0
Levee=0,,,-1,5263.36,354.63,,
#XS Ineff= 3 ,-1
                         5263.37   18676     370   1867627255.17     380
Permanent Ineff=
       F       F       F
Bank Sta=4058.67,4262.58
XS Rating Curve= 0 ,0
Exp/Cntr=0.3,0.1