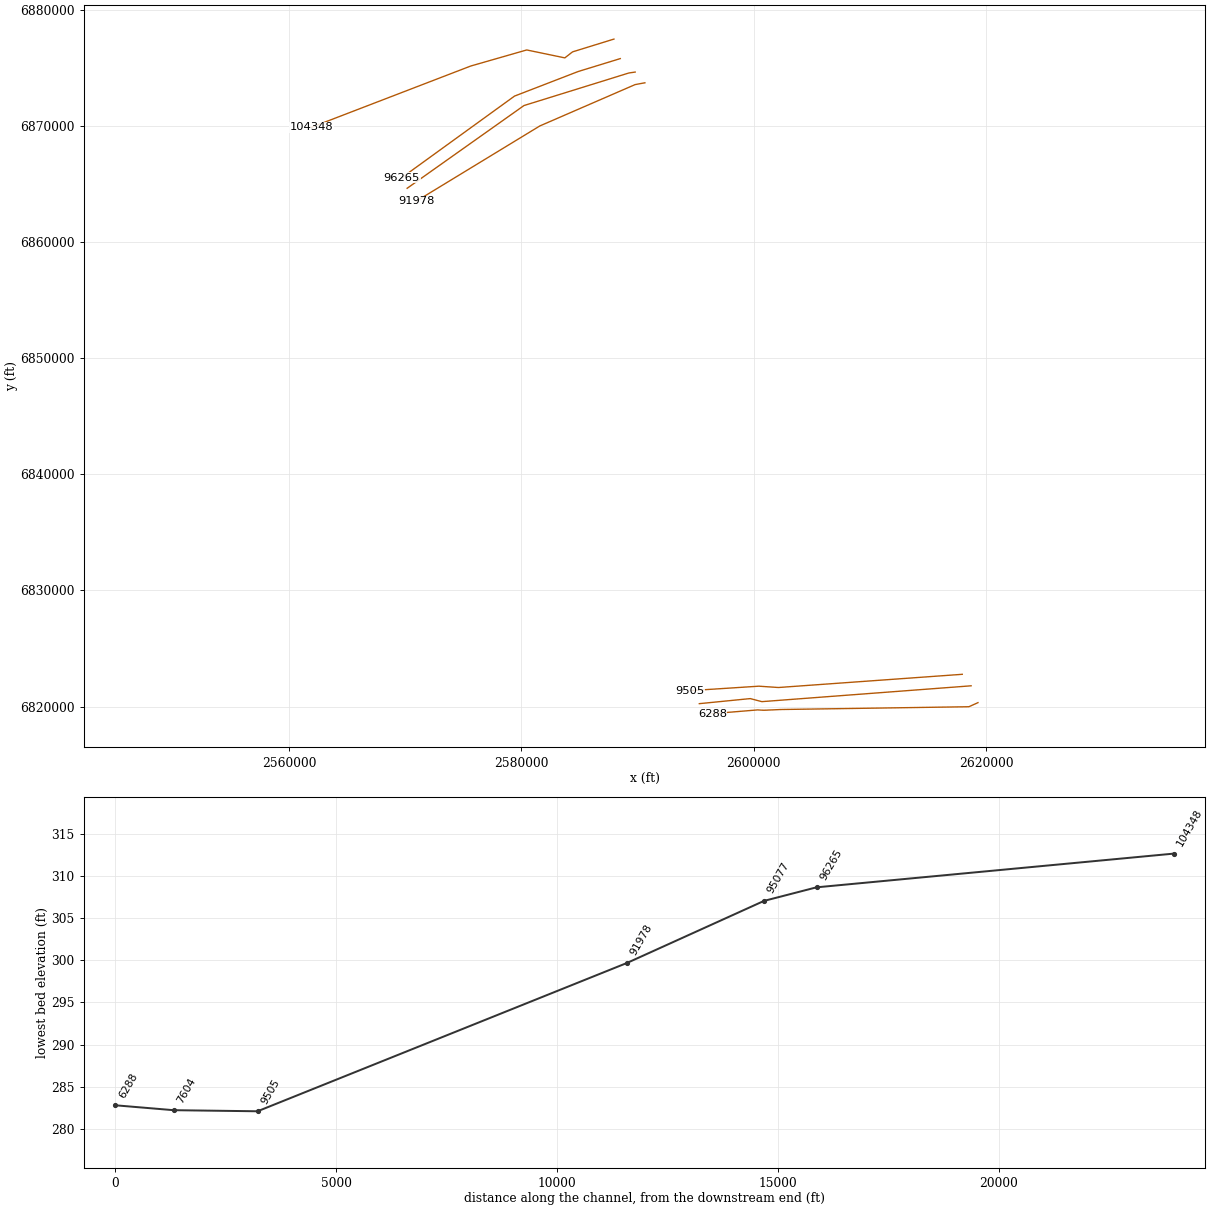
HEC-RAS study TR_FEMA.prj: Trinity_River_FEMA

--- TR_FEMA.g07 (geometry) --- (continued)

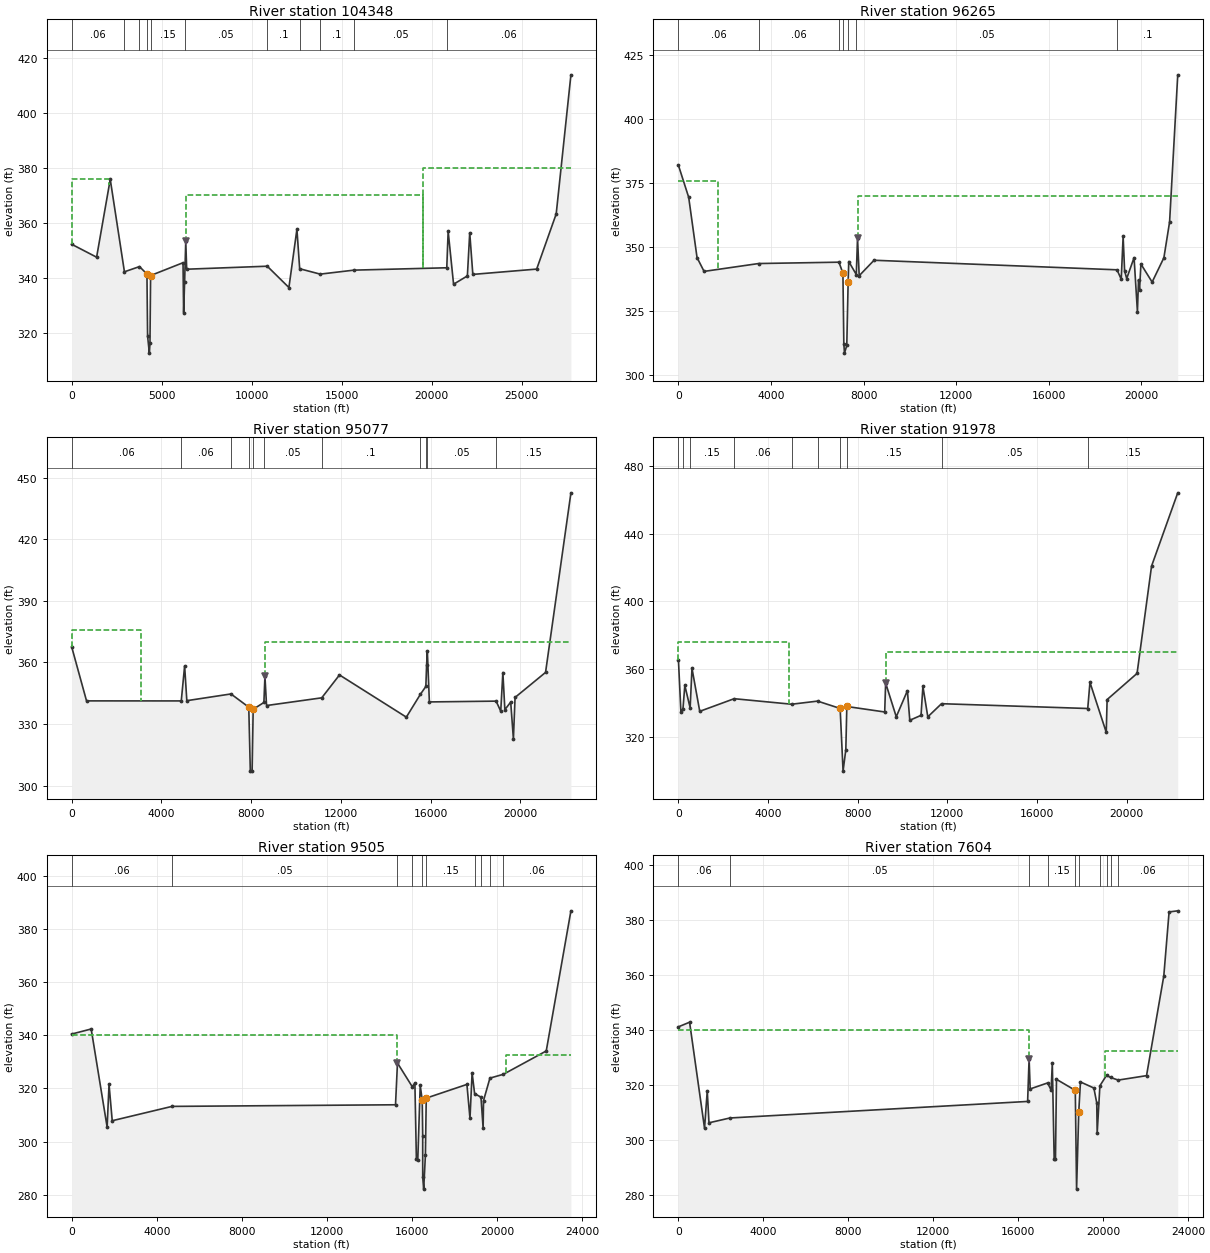
Type RM Length L Ch R = 1 ,104348  ,1720.81,8083.46,4276.21
BEGIN DESCRIPTION:
ROB - Dallas LID14/Ellis LID3
LOB IFA station 2091: flow blocked at natural high ground
ROB IFA station 19491: flow expansion due to natural high ground upstream
END DESCRIPTION:
XS GIS Cut Line= 6
     2587959.751      6877462.12     2584395.378     6876361.093
      2583731.07     6875844.172     2580450.933     6876525.908
      2575638.85     6875144.808     2561891.905     6869859.241
#Sta/Elev= 30
       0  352.26 1387.58  347.55 2144.66  375.87 2932.52  342.24 3769.51  344.13
  4183.4  341.42 4218.77  318.86 4317.71  312.66 4351.15  316.23 4386.78  340.88
 6187.54  345.54 6220.33  327.42 6275.76  338.64 6339.09  353.48 6389.68  343.18
 10865.3  344.2712068.66  336.5212513.24   357.712666.27  343.3513806.08  341.39
15676.84  342.8420836.46   343.720913.16  356.9821214.51  337.7221981.43  340.74
22111.55  356.4622284.05  341.2925829.78  343.2226914.69  363.28 27732.7  413.87
#Mann= 11 ,-1 , 0
       0     .06       0 2932.52     .06       0 3769.51     .15       0
  4183.4    .055       0 4386.78     .15       0 6275.76     .05       0
 10865.3      .1       012666.27     .05       013806.08      .1       0
15676.84     .05       020836.46     .06       0
Levee=0,,,-1,6339.09,353.48,,
#XS Ineff= 3 ,-1
       0    2091  375.87 6338.03   19491     370   19491 27732.7     380
Permanent Ineff=
       F       F       F
Bank Sta=4183.4,4386.78
XS Rating Curve= 0 ,0
Exp/Cntr=0.3,0.1

Type RM Length L Ch R = 1 ,96265   ,1483.83,1188.02,1196.23
BEGIN DESCRIPTION:
ROB - Dallas LID14/Ellis LID3
LOB IFA station 1717: flow expansion due to natural high ground upstream
END DESCRIPTION:
XS GIS Cut Line= 4
     2588505.007     6875781.772     2584879.573     6874669.972
     2579399.972     6872554.087     2569704.405     6865536.324
#Sta/Elev= 30
       0  381.97  442.56   369.5  803.83  345.96 1107.88  340.57 3464.47  343.64
 6936.88  344.17  7109.5  339.88 7148.95  312.28 7177.18  308.66 7276.27  311.65
 7335.69  336.59  7361.7  344.42 7687.49  339.35 7740.77  353.59  7812.9  338.89
 8454.78  344.9218958.26  341.1919139.77  337.5119221.88   354.219285.88  340.82
19375.95  337.7819694.72  345.9419839.85  324.8419888.09  337.3519931.03  333.18
19991.59  343.4320475.66   336.420983.95   345.921230.28  359.8721582.92  417.32
#Mann= 7 ,-1 , 0
       0     .06       0 3464.47     .06       0 6936.88     .15       0
  7109.5    .055       0 7335.69     .15       0 7687.49     .05       0
18958.26      .1       0
Levee=0,,,-1,7740.77,353.59,,
#XS Ineff= 2 , 0
       0    1717  375.87 7740.21       0     370
Permanent Ineff=
       F       F
Bank Sta=7109.5,7335.69
XS Rating Curve= 0 ,0
Exp/Cntr=0.3,0.1

Type RM Length L Ch R = 1 ,95077   ,1759.01,3098.93,2125.14
BEGIN DESCRIPTION:
ROB - Dallas LID14/Ellis LID3
LOB IFA station 3088: flow expansion due to natural high ground upstream
END DESCRIPTION:
XS GIS Cut Line= 4
     2589788.177     6874622.495     2589245.262     6874544.293
     2580213.774     6871740.284     2570155.794     6864616.186
#Sta/Elev= 30
       0  367.72  664.27  341.29 4886.42  341.27 5036.25  358.35 5134.01  341.39
 7101.49  344.67 7895.14  338.22 7964.34  307.05 8044.15  307.05 8091.33   337.2
 8569.44  340.51 8615.35  353.33 8687.44  339.0211147.39  342.7811938.23  353.93
 14917.9  333.3615544.08  344.4915787.85  348.3215821.34  358.8615854.25  365.51
15944.49  340.7818919.48  341.1719125.61  336.2519219.92  355.1219309.16  337.01
19569.22  340.6919689.88  322.75 19763.6  342.9721122.58  355.1722253.59   442.7
#Mann= 11 ,-1 , 0
       0     .06       0 4886.42     .06       0 7101.49     .15       0
 7895.14    .055       0 8091.33     .15       0 8569.44     .05       0
11147.39      .1       015544.08     .05       015787.85     .15       0
15821.34     .05       018919.48     .15       0
Levee=0,,,-1,8615.35,353.33,,
#XS Ineff= 2 , 0
       0    3088  375.87 8614.84       0     370
Permanent Ineff=
       F       F
Bank Sta=7895.14,8091.33
XS Rating Curve= 0 ,0
Exp/Cntr=0.3,0.1

Type RM Length L Ch R = 1 ,91978   ,4138.76,8364.88,1686.69
BEGIN DESCRIPTION:
ROB - Dallas LID14/Ellis LID3
LOB IFA station 3088: flow expansion due to natural high ground upstream
END DESCRIPTION:
XS GIS Cut Line= 4
     2590625.798     6873699.699     2589782.682     6873544.148
     2581579.557      6869985.12     2570937.044     6863505.074
#Sta/Elev= 30
       0  365.13  109.35  334.88  201.58  336.47  284.32  350.34  521.47  336.98
  603.74  360.39  950.43  335.01 2486.36  342.47 5052.56  339.21 6207.56  341.05
 7214.87  336.71  7345.3  299.69 7468.33  312.42 7512.83  337.87 9203.08  334.63
 9244.69  351.73 9718.85   331.810215.64  347.19 10322.3  329.7310824.22  332.64
10907.49  349.7411126.28  331.7611738.14  339.5218262.54  336.6818361.42   352.1
 19088.2  322.63 19127.3  341.9620463.34  357.4121109.56  420.7822278.61  464.08
#Mann= 10 ,-1 , 0
       0      .1       0  201.58     .06       0  521.47     .15       0
 2486.36     .06       0 5052.56     .15       0 6207.56     .15       0
 7214.87    .055       0 7512.83     .15       011738.14     .05       0
18262.54     .15       0
Levee=0,,,-1,9244.69,351.73,,
#XS Ineff= 2 , 0
       0    4947  375.87 9245.09       0     370
Permanent Ineff=
       F       F
Bank Sta=7214.87,7512.83
XS Rating Curve= 0 ,0
Exp/Cntr=0.3,0.1

Type RM Length L Ch R = 1 ,9505    ,1134.79,1900.98,1032.38
BEGIN DESCRIPTION:
LOB - Kaufman LID1/Henderson LID1
END DESCRIPTION:
XS GIS Cut Line= 4
  2617943.653671  6822780.116724 2602120.2802758  6821643.751677
 2600430.9125433 6821757.1829476 2594525.7712673 6821374.0195375
#Sta/Elev= 30
       0   340.5  919.31  342.41  1668.9  305.46 1758.73  321.51 1908.43  307.85
 4718.92  313.25 15227.5  313.8615319.42  329.5916014.85  320.6716138.72  322.04
16208.93  293.4216274.19  293.01 16389.1  321.1916483.71  315.5916505.97  302.11
16507.06   286.616552.25  282.0816633.09  294.9316672.79  316.3718584.62  321.53
18728.66  308.7218828.48  325.8918946.26  318.0919245.89  316.7119346.87  305.02
19365.78  315.4519666.52   323.920300.58  325.3522314.28  334.1323474.79  386.93
#Mann= 10 ,-1 , 0
       0     .06       0 4718.92     .05       015319.42     .06       0
16014.85     .15       016483.71    .055       016672.79     .15       0
18946.26     .05       019245.89     .15       019666.52     .05       0
20300.58     .06       0
Levee=-1,15319.42,329.59,0,,,,
#XS Ineff= 2 , 0
       015319.21     34020419.34       0   332.5
Permanent Ineff=
       F       F
Bank Sta=16483.71,16672.79
XS Rating Curve= 0 ,0
Exp/Cntr=0.3,0.1

Type RM Length L Ch R = 1 ,7604    ,1109.26,1315.69,1024.77
BEGIN DESCRIPTION:
LOB - Kaufman LID1/Henderson LID1
END DESCRIPTION:
XS GIS Cut Line= 4
  2618706.625802  6821790.315041 2600688.1924188 6820426.8980209
  2599694.164641 6820689.1896876 2595306.2479743 6820253.2869098
#Sta/Elev= 30
       0  341.11  524.17  342.78 1228.28   304.3 1355.65  317.87 1437.33  306.28
 2425.82  308.0316439.61  314.0316509.06  329.6116559.86  318.5717380.66  320.75
17546.34  318.1217601.51  327.9817689.72  293.1217750.21  292.9817797.94  322.06
18683.77  318.0518744.51  282.2118846.83  310.2818926.93   321.119558.28   318.9
19694.32  313.4819714.03  302.4719842.43  319.7220153.77  323.4920349.21  322.72
20704.53  321.7822037.77  323.3922850.49  359.5523099.93   382.823507.45   383.2
#Mann= 10 ,-1 , 0
       0     .06       0 2425.82     .05       016509.06     .06       0
17380.66     .15       018683.77    .055       018846.83     .15       0
19842.43     .05       020153.77     .15       020349.21     .05       0
20704.53     .06       0
Levee=-1,16509.06,329.61,0,,,,
#XS Ineff= 2 , 0
       0   16509     34020091.76       0   332.5
Permanent Ineff=
       F       F
Bank Sta=18683.77,18846.83
XS Rating Curve= 0 ,0
Exp/Cntr=0.3,0.1

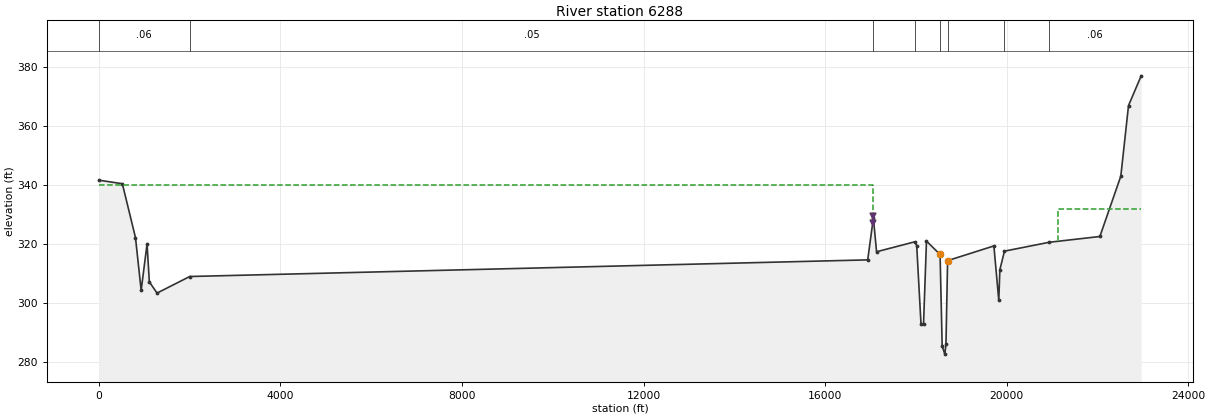
Type RM Length L Ch R = 1 ,6288    ,4777.52,6287.97,5432.52
BEGIN DESCRIPTION:
LOB - Kaufman LID1/Henderson LID1
END DESCRIPTION:
XS GIS Cut Line= 6
2619293.73848072 6820341.02639792618516.223959626819988.94081597
2602318.95386082 6819749.15356592600866.164771656819685.79903381
2600323.704570476819714.953503062596424.624770226819393.00007872
#Sta/Elev= 30
       0  341.78   519.1  340.57   808.6  322.28  933.51  304.43 1063.51  320.15
  1113.5  307.29 1283.49  303.49 2003.45  309.1116938.12  314.7517063.12  328.99
17133.08   317.517972.71  320.8718017.69   319.618112.65  292.8618167.63  292.91
 18232.6  321.1118532.45  316.58 18578.5   285.518636.94  282.7918662.12  286.18
18698.05  314.4919717.65  319.4819825.78  300.99   19849  311.3819950.19  317.71
20936.78  320.7222052.49  322.6822513.65  343.1422683.49  367.0922962.33  377.16
#Mann= 8 ,-1 , 0
       0     .06       0 2003.45     .05       017063.12     .06       0
17972.71     .15       018532.45    .055       018698.05     .15       0
19950.19     .05       020936.78     .06       0
Levee=-1,17048.12,329.68,0,,,,
#XS Ineff= 2 , 0
       017048.58     340   21133       0     332
Permanent Ineff=
       F       F
Bank Sta=18532.45,18698.05
XS Rating Curve= 0 ,0
Exp/Cntr=0.3,0.1
Stream Node=Trinity River   ,                , 0 , 0 ,Upstream end
Stream Node=Trinity River   ,                , 0 , 1 ,Downstream end
LCMann Table=0